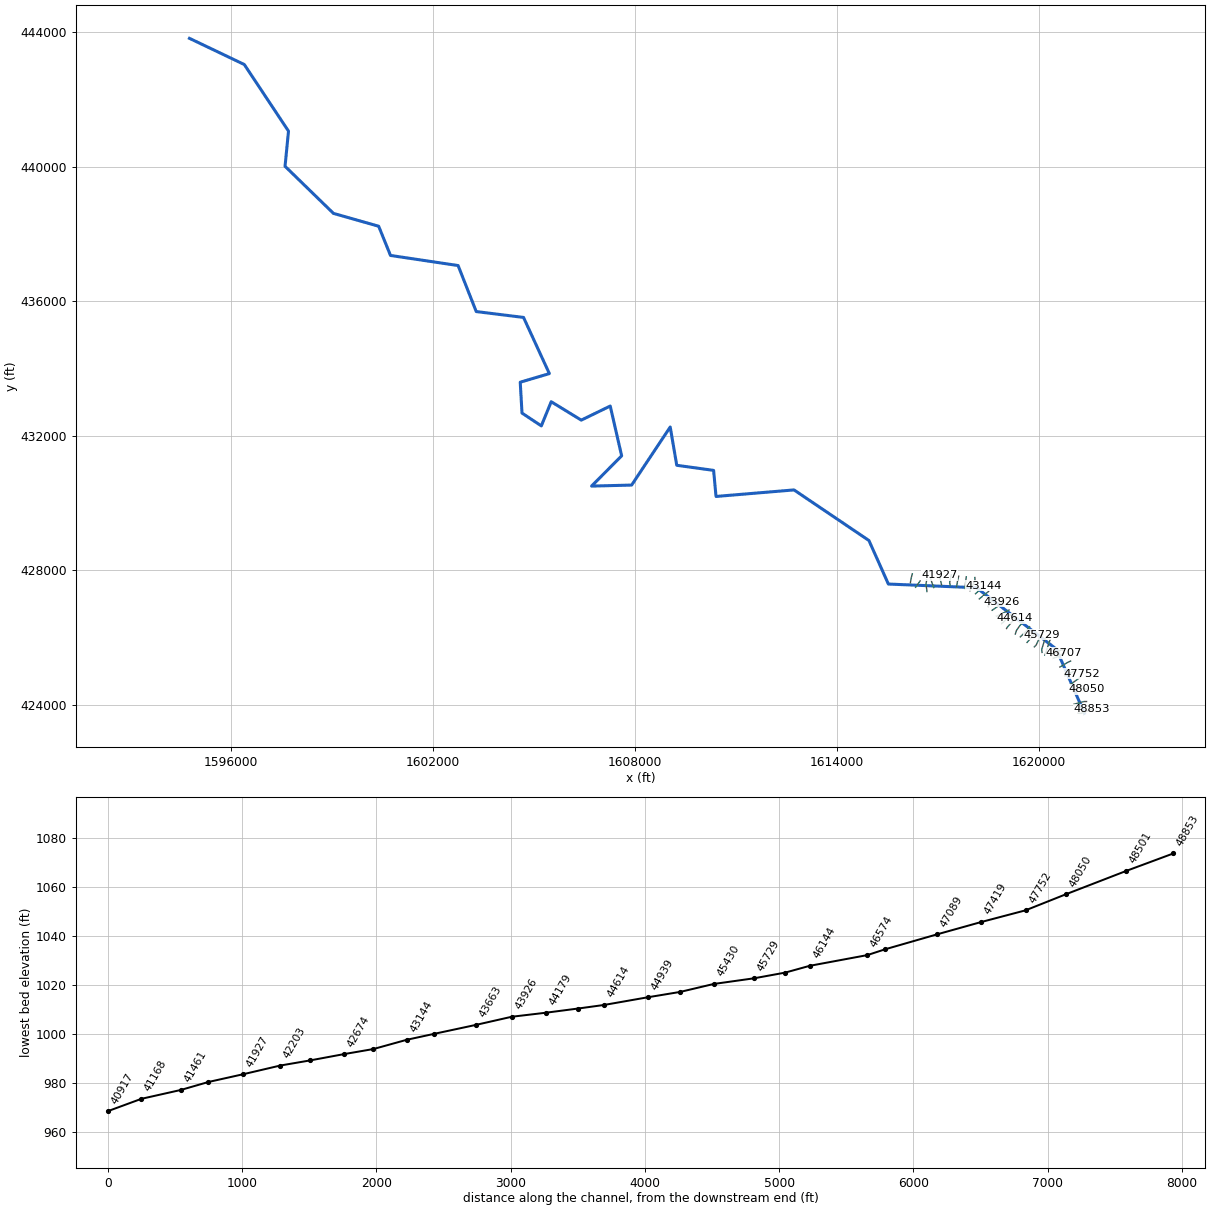
--- PROCTRCK.prj (project) ---

Proj Title=PROCTRCK
Current Plan=p01
Default Exp/Contr=0,0
English Units
Geom File=g01
Flow File=f01
Plan File=p01
BEGIN DESCRIPTION:
---------- MODELED AS PART OF WVEMD CTP PROGRAM, 2023----------
Stream Name: Proctor Creek
Flood Zone:  AFH
Wetzel County, WV
HEC-RAS Version: RAS 6.3
Vertical Datum: NAVD88
Projection: NAD 1983 StatePlane West Virginia S FIPS 4702 (US Feet)
Terrain: 1-meter West Virginia FEMA R3 South Central (collected 2018-2020)
Land Use: 2019 NLCD
Hydrologic Method:
WV SIR2010-5033 regression equations
Additional Model Notes:
None
END DESCRIPTION:
DSS Export Rating Curves= 0
DSS Export Rating Curve Sorted= 0
DSS Export Volume Flow Curves= 0
DXF OffsetX= 0
DXF OffsetY= 0
DXF ScaleX= 0
DXF ScaleY= 0

--- PROCTRCK.p01 (plan) ---

Plan Title=Floodplain
Program Version=6.30
Short Identifier=Floodplain
Geom File=g01
Flow File=f01
Subcritical Flow
K Sum by GR= 0
Std Step Tol= 0.01
Critical Tol= 0.01
Num of Std Step Trials= 20
Max Error Tol= 0.3
Flow Tol Ratio= 0.001
Split Flow NTrial= 30
Split Flow Tol= 0.02
Split Flow Ratio= 0.02
Log Output Level= 0
Friction Slope Method= 1
Unsteady Friction Slope Method= 2
Unsteady Bridges Friction Slope Method= 1
Parabolic Critical Depth
Global Vel Dist= 0 , 0 , 0
Global Log Level= 0
CheckData=False
Encroach Param=-1 ,0,0, 0
Mapping Interval=1HOUR
Computation Time Step Use Courant=        0
Computation Time Step Use Time Series=    0
Computation Time Step Count To Double=0
Computation Time Step Max Doubling=0
Computation Time Step Max Halving=0
Computation Time Step Residence Courant=0
Run HTab= 0
Run UNet= 0
Run Sediment= 0
Run PostProcess= 0
Run WQNet= 0
Run RASMapper=-1
UNET Theta= 0
UNET Theta Warmup= 0
UNET ZTol= 0
UNET ZSATol= 0
UNET MxIter= 0
UNET Max Iter WO Improvement= 0
UNET MaxInSteps= 0
UNET DtIC= 0
UNET DtMin= 0
UNET MaxCRTS= 0
UNET WFStab= 0
UNET SFStab= 0
UNET WFX= 1
UNET SFX= 1
UNET Gravity=32.17405
UNET 1D Methodology=Finite Difference
UNET DSS MLevel= 1
UNET Pardiso=0
UNET DZMax Abort= 0
UNET Use Existing IB Tables= 0
UNET Froude Reduction=False
UNET Froude Limit= 0
UNET Froude Power= 0
UNET D1 Cores= 0
UNET WindReference=Eulerian
UNET WindDragFormulation=Hsu (1988)
UNET D2 Coriolis=0
UNET D2 Cores= 0
UNET D2 Theta= 1
UNET D2 Theta Warmup= 1
UNET D2 Z Tol= 0.01
UNET D2 Volume Tol= 0.01
UNET D2 Max Iterations= 20
UNET D2 Equation= 0
UNET D2 RampUpFraction=0.1
UNET D2 TimeSlices= 1
UNET D2 Turbulence Formulation=Non-Conservative (original)
UNET D2 Eddy Viscosity=0.3
UNET D2 Transverse Eddy Viscosity=0.1
UNET D2 Smagorinsky Mixing=0
UNET D2 BCVolumeCheck=0
UNET D2 Cores=0
UNET D2 SolverType=PARDISO (Direct)
UNET D2 Minimum Iterations= 3
UNET D2 Maximum Iterations= 30
UNET D2 Restart Number= 10
UNET D2 Relaxation Coeff=1.3
UNET D2 SOR Precondition Iterations= 10
UNET D2 ILUT Maximum Fill= 8
UNET D2 ILUT Tolerance=1E-08
UNET D2 Convergence Tolerance=0.00001
UNET D1D2 MaxIter= 0
UNET D1D2 ZTol=0.01
UNET D1D2 QTol=0.1
UNET D1D2 MinQTol=1
Write IC File= 0
Write IC File at Fixed DateTime=0
Write IC File at Sim End=0
Echo Input=False
Echo Parameters=False
Echo Output=False
Write Detailed= 0
HDF Write Warmup=0
HDF Write Time Slices=0
HDF Flush=0
HDF Compression= 1
HDF Chunk Size= 1
HDF Spatial Parts= 1
HDF Use Max Rows=0
HDF Fixed Rows= 1
Calibration Method= 0
Calibration Iterations= 20
Calibration Max Change=0.05
Calibration Tolerance=0.2
Calibration Maximum=1.5
Calibration Minimum=0.5
Calibration Optimization Method= 1
WQ AD Non Conservative
WQ ULTIMATE=-1
WQ Max Comp Step=1HOUR
WQ Output Interval=15MIN
WQ Output Selected Increments= 0
WQ Output face flow=0
WQ Output face velocity=0
WQ Output face area=0
WQ Output face dispersion=0
WQ Output cell volume=0
WQ Output cell surface area=0
WQ Output cell continuity=0
WQ Output cumulative cell continuity=0
WQ Output face conc=0
WQ Output face dconc_dx=0
WQ Output face courant=0
WQ Output face peclet=0
WQ Output face adv mass=0
WQ Output face disp mass=0
WQ Output cell mass=0
WQ Output cell source sink temp=0
WQ Output nsm pathways=0
WQ Output nsm derived pathways=0
WQ Create Restart=0
WQ Fixed Restart=0
WQ System Summary=0
WQ Write To DSS=0
Sorting and Armoring Iterations= 10
XS Update Threshold= 0.02
Bed Roughness Predictor= 0
Hydraulics Update Threshold= 0.02
Energy Slope Method= 1
Volume Change Method= 1
Sediment Retention Method= 0
Sediment TS Multiplier= 1
Warm Up Method= 0
XS Weighting Method= 0
Number of US Weighted Cross Sections= 1
Number of DS Weighted Cross Sections= 1
Upstream XS Weight=0
Main XS Weight=1
Downstream XS Weight=0
Number of DS XS's Weighted with US Boundary= 1
Upstream Boundary Weight= 1
Weight of XSs Associated with US Boundary= 0
Number of US XS's Weighted with DS Boundary= 1
Downstream Boundary Weight= 0.5
Weight of XSs Associated with DS Boundary= 0.5
Percentile Method= 0
Sediment Output Level= 3
Mass or Volume Output= 0
Output Increment Type= 1
Profile and TS Output Increment= 1
Transport Output Increment 1
XS Output Flag= 0
XS Output Increment= 10
Read HDF5 Sediment Hotstart= 0
Sediment Hotstart Type= 0
Write Gradation File= 0
Read Gradation Hotstart= 0
Write HDF5 File= 1
Write Binary Output= 1
Write DSS Sediment File= 0
DSS Sediment Output Type= 1
SV Curve= 0
Specific Gage Flag= 0
Subcell Erosion Methods= 0
Subcell Deposition Methods= 0
Advection Scheme= 1
Matrix Solver= 0
Implicit Weighting Factor= 1
Maximum Outer Loop Convergence Iterations= 5
Convergence Maximum Absolute= 0.001
Convergence RMSE= 0.0001
Grain Fractions Max Abs Error= 0.001
Max Subgrid Regions= 1
Max Subgrid Length Scale= 3.402823E+38
Initial Layer Thickness= 3.402823E+38
Min Layer Thickness= 3.402823E+38
Max Layer Thickness= 3.402823E+38
Number of Layers= 5

--- PROCTRCK.f01 (steady flow) ---

Flow Title=Flow
Program Version=6.31
Number of Profiles= 1
Profile Names=F01pct
River Rch & RM=PROCTRCK,Main,48853
     316
River Rch & RM=PROCTRCK,Main,47752
     465
River Rch & RM=PROCTRCK,Main,46574
     958
River Rch & RM=PROCTRCK,Main,42896
    1110
River Rch & RM=PROCTRCK,Main,40408
    1470
River Rch & RM=PROCTRCK,Main,38505
    1760
River Rch & RM=PROCTRCK,Main,34525
    2080
River Rch & RM=PROCTRCK,Main,32675
    2610
River Rch & RM=PROCTRCK,Main,30788
    3010
River Rch & RM=PROCTRCK,Main,15414
    3380
River Rch & RM=PROCTRCK,Main,7320
    4510
Boundary for River Rch & Prof#=PROCTRCK,Main            , 1
Up Type= 0
Dn Type= 3
Dn Slope=0.0094
DSS Import GetInterval= 0
DSS Import GetPeak= 0
DSS Import FillOption= 0

--- PROCTRCK.g01 (geometry) ---

Geom Title=Geometry
Program Version=6.31

River Reach=PROCTRCK        ,Main
Reach XY= 30
1621352.96694749423749.7543739081620517.11230623425657.129924232
     1618146.651      427481.106      1615527.84      427591.173
     1614949.518         428886.      1612723.83      430390.153
      1610405.82      430196.132     1610333.457      430971.444
     1609238.776       431122.62     1609044.343      432260.988
1607897.84548074430534.3307688251606707.32906934430503.998186768
1607600.95506833431404.011637319     1607261.731      432884.832
     1606401.213      432466.202     1605507.327      433013.252
1605214.00396844432294.9187166991604639.78534113432676.029620368
     1604587.149      433593.672     1605452.723      433849.501
     1604685.234      435519.9771603279.56320024435694.876876353
     1602740.727      437063.044     1600731.505      437363.366
     1600380.624      438231.973      1599036.76        438614.2
     1597597.972      440015.1321597700.48996628441060.901552529
       1596387.3       443041.23     1594757.551      443820.372

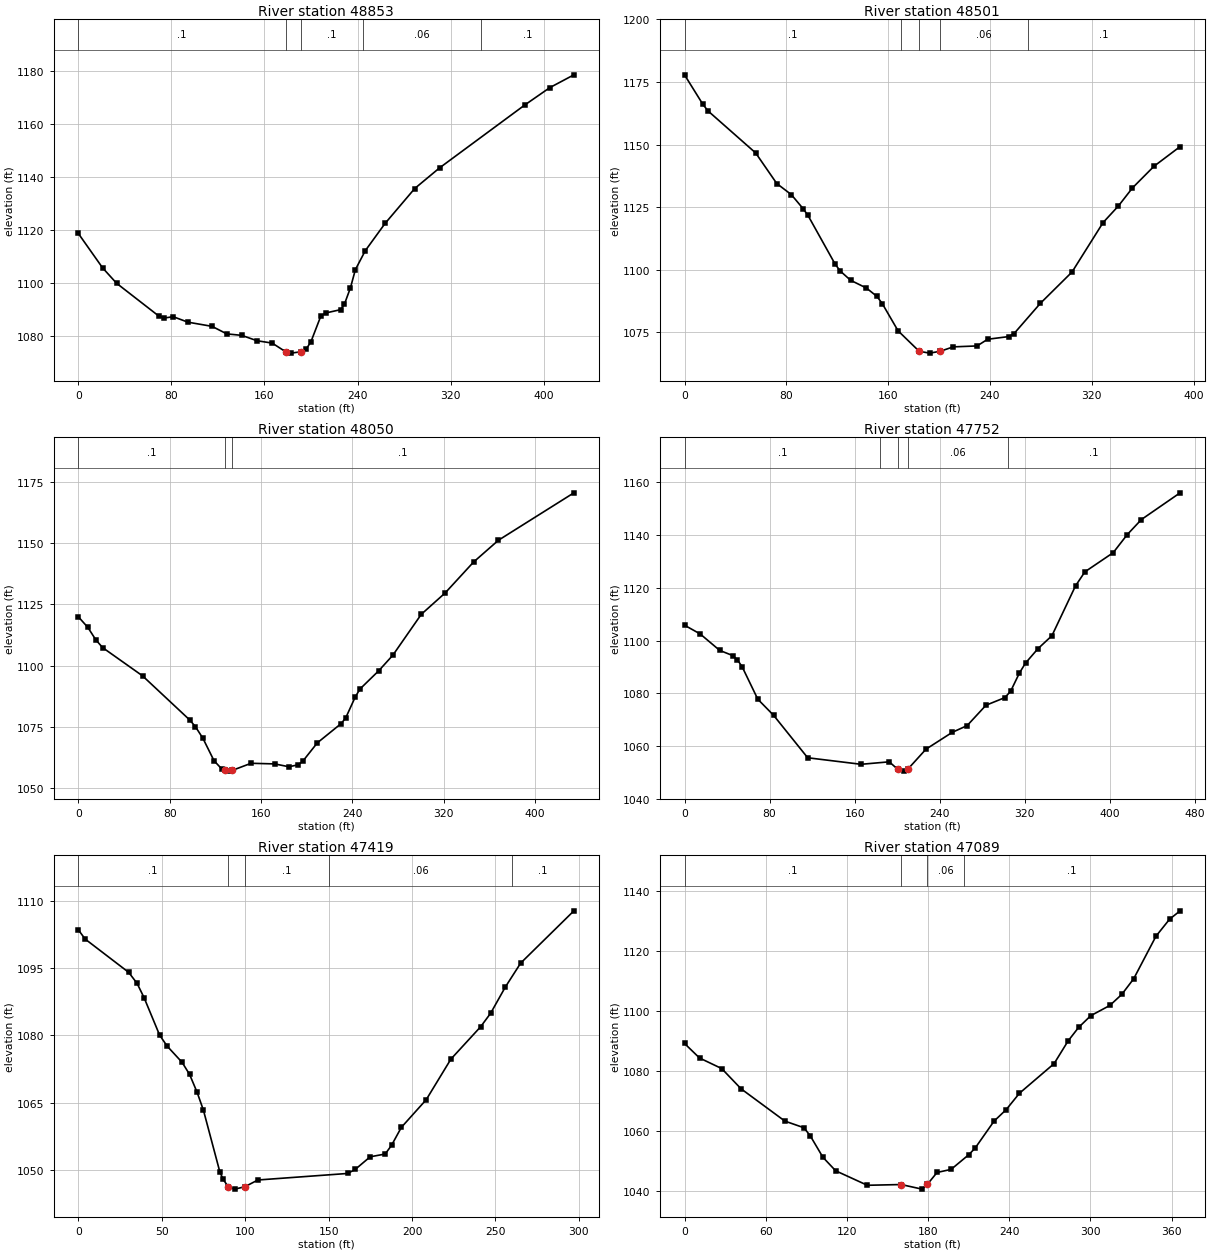
Type RM Length L Ch R = 1 ,48853   ,350.7,352.7,349.6
XS GIS Cut Line= 4
1621163.25277888423750.6130582111621247.58125344423744.756914145
 1621456.0599822423819.7155581941621567.32671946423864.222253097
#Sta/Elev= 30
       0 1118.78    20.9 1105.81    32.9 1100.03      69 1087.75      74 1086.96
    81.5 1087.45    94.2 1085.39   114.9 1083.82   127.6 1080.98   140.4 1080.43
   153.6  1078.4   166.6 1077.52  178.161074.265   182.9 1073.74   191.1 1074.24
   195.6 1075.11   199.9 1078.01   208.4 1087.67   212.6 1088.85   225.4  1090.1
   228.6 1092.05   233.9 1098.37   238.1 1105.15   246.6 1112.28   263.6 1122.54
   289.1 1135.69   310.4 1143.44   383.7 1167.13   405.2 1173.66   425.9 1178.48
#Mann= 5, -1 ,  0
       0     0.1       0  178.16   0.045       0   191.1     0.1       0
  244.53    0.06       0  346.08     0.1       0
Bank Sta=178.16,191.1
XS Rating Curve= 0 ,0
Exp/Cntr(USF)=0,0
Exp/Cntr=0.3,0.1

Type RM Length L Ch R = 1 ,48501   ,447.8,451,449
XS GIS Cut Line= 3
1621038.15474905424015.5471321551621341.10721213 424097.52530599
1621416.68801118424097.250204765
#Sta/Elev= 30
       0 1177.87    14.5 1166.01    18.6 1163.37    55.9 1146.63    72.5 1134.39
    83.9 1129.97    93.2 1124.33      97 1121.65   118.1 1102.38   122.2 1099.47
   130.5  1095.7   142.9  1092.6   151.2 1089.25   155.4 1086.36   167.8 1075.49
   184.4 1067.29   192.6 1066.56   200.9 1067.29   211.1 1069.06   229.9 1069.44
   238.2 1072.11   254.8 1073.18   258.9 1074.35   279.6 1086.47   304.5 1099.01
   328.9 1118.78   340.9  1125.4     352 1132.65   368.9  1141.3   389.4 1149.16
#Mann= 5, -1 ,  0
       0     0.1       0     170    0.06       0   184.4   0.045       0
   200.9    0.06       0     270     0.1       0
Bank Sta=184.4,200.9
XS Rating Curve= 0 ,0
Exp/Cntr(USF)=0,0
Exp/Cntr=0.3,0.1

Type RM Length L Ch R = 1 ,48050   ,295.3,297.6,300
XS GIS Cut Line= 4
1621015.59309755424403.6071604361621042.92176986424446.552216922
1621264.15387903424505.1136575851621412.50952871424462.168601098
#Sta/Elev= 30
       0 1119.91     8.4 1115.54    15.3 1110.52    21.3 1107.33    56.3 1095.81
    97.7  1077.8   102.6  1075.1   109.1 1070.43   118.9 1061.23   125.5 1057.96
   128.6 1057.27   130.8 1056.99   134.9  1057.3   151.4 1060.19   172.1 1059.93
   184.5 1058.77   192.8 1059.58     197 1061.23   209.4 1068.51   230.1  1076.3
   234.2  1078.6   242.5 1087.08   246.7 1090.43   263.2 1097.89   275.6 1104.25
   300.5 1120.91   321.4 1129.61   346.3 1142.21   368.1  1151.1   434.2 1170.42
#Mann= 3, -1 ,  0
       0     0.1       0   128.6   0.045       0   134.9     0.1       0
Bank Sta=128.6,134.9
XS Rating Curve= 0 ,0
Exp/Cntr(USF)=0,0
Exp/Cntr=0.3,0.1

Type RM Length L Ch R = 1 ,47752   ,333.2,333.1,331.7
XS GIS Cut Line= 4
1620942.71663806 424622.236538911620992.16852128424644.359749827
 1621214.7019958424805.7290529871621273.26343646424929.358761053
#Sta/Elev= 30
       0 1105.84    14.7 1102.53    33.1 1096.28    45.2 1094.34    49.7 1092.73
    54.2 1090.05    68.9 1077.77    83.8 1071.64   115.8 1055.56     166 1053.08
   192.5 1054.02   200.3 1051.24   206.1 1050.49  209.931051.227     227 1058.81
   251.7  1065.2   265.7 1067.76   283.4 1075.48   301.2 1078.38   306.6  1080.8
   314.9 1087.74   320.6 1091.48   332.2  1096.9   345.4 1101.85   367.6 1120.76
   376.4 1126.08     403 1133.34   416.3 1140.24   429.5 1145.91   465.9 1156.05
#Mann= 5, -1 ,  0
       0     0.1       0  184.17    0.06       0   200.3   0.045       0
  209.93    0.06       0  304.17     0.1       0
Bank Sta=200.3,209.93
XS Rating Curve= 0 ,0
Exp/Cntr(USF)=0,0
Exp/Cntr=0.3,0.1

Type RM Length L Ch R = 1 ,47419   ,326,329.5,329.8
XS GIS Cut Line= 2
1620772.91676889424858.6227080531621036.44325187424995.656479204
#Sta/Elev= 30
       0  1103.6     4.1 1101.53    30.2 1094.09    35.2 1091.64    39.4 1088.45
    48.7 1080.09    53.2 1077.63    62.2 1073.99    66.7 1071.28    71.2 1067.29
      75 1063.27    84.8 1049.54    86.8 1047.86    89.8 1046.22    93.8 1045.67
    99.81046.202   107.6 1047.71   161.4 1049.17   165.9 1050.06   174.9 1052.89
   183.9 1053.51   187.7 1055.45   193.6 1059.47   208.5 1065.65   223.3 1074.72
   241.1 1081.94   247.1 1084.96   255.9 1090.81   265.1 1096.16     297 1107.84
#Mann= 5, -1 ,  0
       0     0.1       0    89.8   0.045       0    99.8     0.1       0
     150    0.06       0     260     0.1       0
Bank Sta=89.8,99.8
XS Rating Curve= 0 ,0
Exp/Cntr(USF)=0,0
Exp/Cntr=0.3,0.1

Type RM Length L Ch R = 1 ,47089   ,373.7,382.2,376.7
XS GIS Cut Line= 4
1620623.63798339425123.1310118461620672.80067432425150.604280305
1620846.31605406425256.1594696481620943.19547442425300.984276082
#Sta/Elev= 30
       0 1089.16    11.1 1084.32    27.5 1080.79    41.8 1074.05    74.2 1063.28
    88.3 1061.07      93 1058.32   102.3 1051.22   111.7 1046.73   135.1  1041.9
   160.1 1042.15   175.5 1040.62   179.5 1042.23   186.6 1046.17     197  1047.2
     210 1052.07   214.7 1054.26   228.7 1063.26   237.7 1067.11   247.5 1072.57
   273.1 1082.44   283.4 1089.97   291.2  1094.5   300.2 1098.42   314.3 1101.83
   323.1  1105.5   331.9 1110.71   348.4 1124.91   358.4 1130.55   366.2 1133.36
#Mann= 4, -1 ,  0
       0     0.1       0   160.1   0.045       0   179.5    0.06       0
  206.32     0.1       0
Bank Sta=160.1,179.5
XS Rating Curve= 0 ,0
Exp/Cntr(USF)=0,0
Exp/Cntr=0.3,0.1

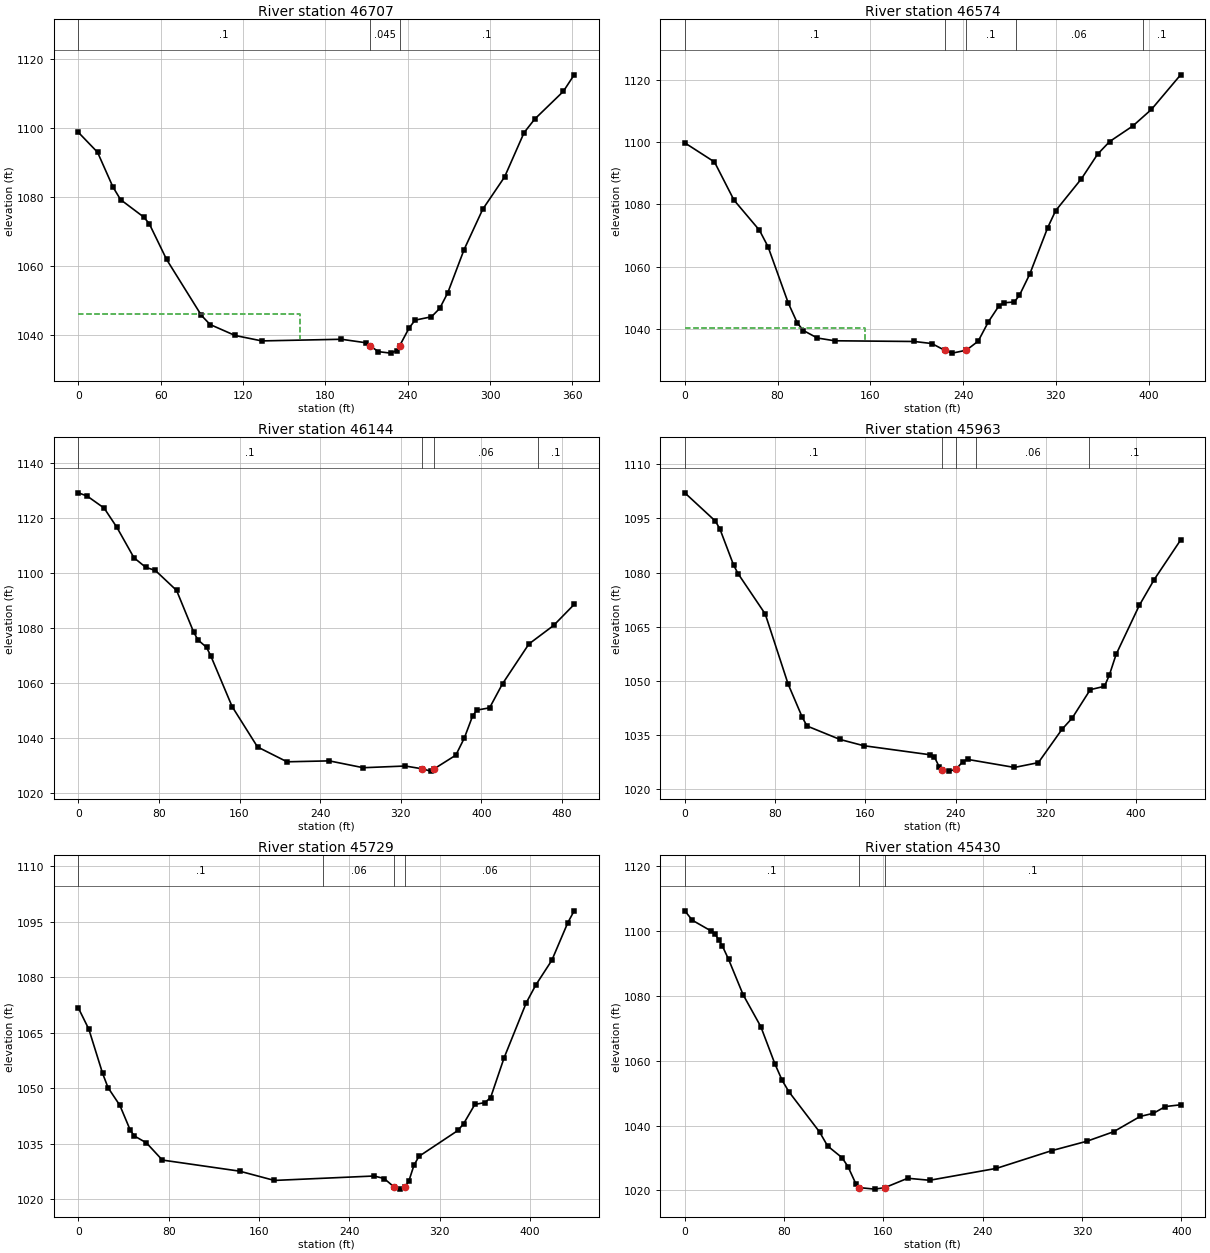
Type RM Length L Ch R = 1 ,46707   ,133,133.5,133.2
XS GIS Cut Line= 4
1620426.84515627425384.7026384481620522.29331206425415.868870119
1620701.88173008425505.6630791291620749.92423158 425541.77692658
#Sta/Elev= 30
       0 1098.78      14 1092.98    25.2  1082.9    30.8  1079.2    47.6 1074.16
    51.6 1072.27    64.3 1061.83    89.7 1045.55      96 1042.91   114.2 1039.72
   133.7 1038.14   191.7 1038.62   209.6  1037.6   212.5 1036.72   218.7 1035.02
   227.5 1034.59   232.1 1035.32   234.21036.767   241.1 1041.95   245.4 1044.18
   257.3 1045.15   263.3 1047.57   269.2 1052.13   281.1 1064.69   294.7 1076.43
   310.6  1085.8   324.8 1098.68   332.6 1102.64   353.4 1110.67   361.3 1115.49
#Mann= 3, -1 ,  0
       0     0.1       0   212.5   0.045       0   234.2     0.1       0
#XS Ineff= 2 , 0
           161.3 1046.01
Permanent Ineff=
       F       F
Bank Sta=212.5,234.2
XS Rating Curve= 0 ,0
Exp/Cntr(USF)=0,0
Exp/Cntr=0.3,0.1

Type RM Length L Ch R = 1 ,46574   ,418.2,429.3,430.6
XS GIS Cut Line= 4
1620365.33098303425455.1932203061620434.59020659425520.772793044
1620658.60298299425630.5725423741620741.27213556 425632.99877974
#Sta/Elev= 30
       0 1099.78    25.6 1093.63    42.4 1081.39    64.4 1071.68    71.8 1066.39
    89.2 1048.33    97.1 1041.84   102.3 1039.46   114.3 1037.06   129.2 1036.17
     198 1035.94     213 1035.28     2241033.146   230.7  1032.2   242.8 1033.14
     253 1036.04   261.9 1042.31   270.8 1047.32   275.3 1048.38   284.2 1048.64
   288.6 1050.79   297.5  1057.6     313 1072.56   319.8 1077.97   342.1 1088.26
     356 1096.14   366.4  1100.2   386.4 1105.21   402.4 1110.51   427.6 1121.64
#Mann= 5, -1 ,  0
       0     0.1       0     224   0.045       0   242.8     0.1       0
  285.38    0.06       0  394.86     0.1       0
#XS Ineff= 2 , 0
          155.66 1040.29
Permanent Ineff=
       F       F
Bank Sta=224,242.8
XS Rating Curve= 0 ,0
Exp/Cntr=0.3,0.1

Type RM Length L Ch R = 1 ,46144   ,181.4,181.4,181.7
XS GIS Cut Line= 4
1620179.24425084425472.3318279681620233.11160396425628.376910955
1620307.23982797425868.022885141  1620337.989098425937.550805681
#Sta/Elev= 30
       0 1128.99     8.7 1127.83    25.6 1123.44    38.3 1116.41    55.2 1105.39
    66.9 1101.91    76.4 1100.78    97.5 1093.51   114.5  1078.3   118.7 1075.53
   127.2 1072.82   131.4 1069.75   152.6 1051.29   177.8 1036.61   207.1 1031.21
     249 1031.55   282.7 1029.06   324.4 1029.68   341.1 1028.67   349.5 1027.82
   353.1 1028.66   374.6 1033.63     383 1039.84   391.3 1047.94   395.5    1050
   408.1 1050.84   420.9 1059.57   447.1 1074.04   471.6 1080.77     492 1088.41
#Mann= 4, -1 ,  0
       0     0.1       0   341.1   0.045       0   353.1    0.06       0
  455.93     0.1       0
Bank Sta=341.1,353.1
XS Rating Curve= 0 ,0
Exp/Cntr=0.3,0.1

Type RM Length L Ch R = 1 ,45963   ,235,233.7,232.4
XS GIS Cut Line= 4
1620093.60297803425557.600393248 1620084.4109302425645.320463215
1620168.15871599425917.5928320381620196.57550726425977.672173755
#Sta/Elev= 30
       0 1102.07    27.1 1094.25    31.1 1092.08    43.2 1082.12    47.2 1079.71
    71.3 1068.54    91.6 1049.14   104.1 1039.98   108.3 1037.55   137.6 1033.82
   158.5  1032.1   217.1  1029.6   221.3 1028.96   225.5 1026.24   228.2  1025.5
   233.9 1025.06   240.21025.515   246.4 1027.68   250.6 1028.31   292.2 1026.08
   313.4 1027.41   334.3 1036.61   343.4 1039.75   359.4  1047.6     372 1048.53
   376.3 1051.62   382.3 1057.35   402.9 1070.94   416.1 1078.08   439.5 1089.01
#Mann= 5, -1 ,  0
       0     0.1       0   228.2   0.045       0   240.2     0.1       0
   258.2    0.06       0   358.2     0.1       0
Bank Sta=228.2,240.2
XS Rating Curve= 0 ,0
Exp/Cntr=0.3,0.1

Type RM Length L Ch R = 1 ,45729   ,303.5,299.5,291.3
XS GIS Cut Line= 4
1619864.85358898425722.5825338671619919.47690835425776.878409047
1620036.28294489 426027.988720321620095.87285918426088.728373361
#Sta/Elev= 30
       0 1071.72     9.3 1065.96    21.5 1054.01    26.3 1050.16    36.8 1045.36
    46.1 1038.58    49.7 1037.08    60.3 1035.23    74.4 1030.58   142.8 1027.58
   173.6 1025.07   261.9 1026.27   270.8 1025.59   279.6 1023.31     285 1022.72
   289.5  1023.3   292.8    1025   297.2 1029.14   301.6 1031.57   336.2 1038.59
   341.3 1040.46   351.2 1045.64   359.9  1046.1   365.1 1047.46   377.1 1058.26
   396.7 1073.12   405.1  1077.9   419.3 1084.58   433.4 1094.71   439.1 1097.97
#Mann= 4, -1 ,  0
       0     0.1       0  217.02    0.06       0   279.6   0.045       0
   289.5    0.06       0
Bank Sta=279.6,289.5
XS Rating Curve= 0 ,0
Exp/Cntr=0.3,0.1

Type RM Length L Ch R = 1 ,45430   ,250.1,249.9,248
XS GIS Cut Line= 3
1619648.08959319425854.2266892291619832.25609175426061.814861113
1619913.07499809426152.915849379
#Sta/Elev= 30
       0 1106.18     6.1 1103.27    21.5  1099.9    24.5 1098.92    27.2 1097.33
    30.2 1095.39    35.2 1091.28      47  1080.3    61.2  1070.5    72.6 1058.98
    78.4 1053.94    83.8 1050.44   108.5 1038.04     115 1033.71   126.6 1030.11
   131.4 1027.37   137.7  1022.1   140.5 1020.88   152.8 1020.41     1611020.853
   179.5 1023.76   197.2 1023.14     251 1026.81   295.4 1032.26   323.9 1035.18
   345.3 1038.09   366.7 1042.81   377.4 1043.78     387 1045.86   399.3  1046.4
#Mann= 3, -1 ,  0
       0     0.1       0   140.5   0.045       0     161     0.1       0
Bank Sta=140.5,161
XS Rating Curve= 0 ,0
Exp/Cntr=0.3,0.1

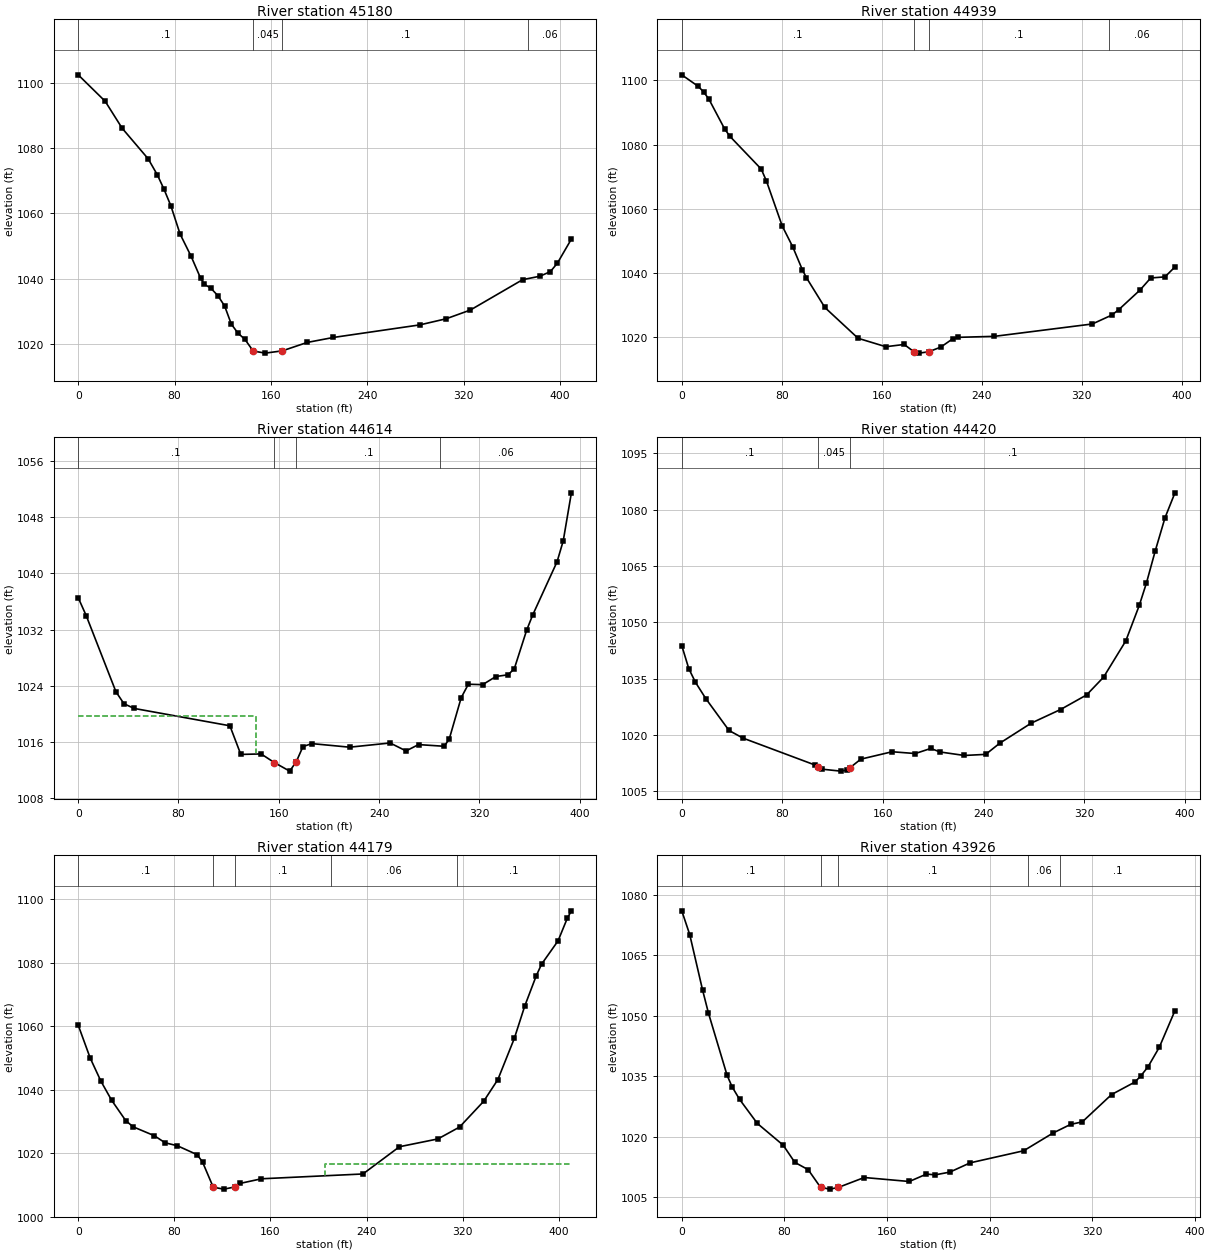
Type RM Length L Ch R = 1 ,45180   ,238.9,240.3,242.7
XS GIS Cut Line= 3
1619448.95132388426020.0653050541619652.36913179426217.780747618
1619722.70965539426322.099903956
#Sta/Elev= 30
       0 1102.38    22.4 1094.28    36.5 1086.02    58.1 1076.66    65.8 1071.69
    71.3  1067.3    76.9 1062.32    84.6 1053.62    93.7 1046.85   101.6 1040.13
   104.8 1038.23   110.1 1037.06     116 1034.74   121.6 1031.58   127.1 1026.07
   132.7 1023.25   138.3 1021.44   145.31017.806   155.3 1017.16   169.5 1017.86
   190.1 1020.43   211.9 1021.96   283.7 1025.81   305.6 1027.69   325.6 1030.35
     369 1039.65   383.5 1040.72   392.1 1042.14   397.9 1044.72   409.5 1052.09
#Mann= 4, -1 ,  0
       0     0.1       0   145.3   0.045       0   169.5     0.1       0
  373.67    0.06       0
Bank Sta=145.3,169.5
XS Rating Curve= 0 ,0
Exp/Cntr=0.3,0.1

Type RM Length L Ch R = 1 ,44939   ,325.5,325.8,321.9
XS GIS Cut Line= 4
1619299.76096609426103.8172880951619332.67803391426208.948372907
1619419.81322666426333.6271627451619504.76483475426435.235042406
#Sta/Elev= 30
       0 1101.74    13.3 1098.11    17.5  1096.4    21.7 1094.17    34.3 1084.88
    38.5 1082.58    63.6 1072.36    67.8  1068.6    80.4 1054.61    88.8 1048.13
    96.6 1040.89    99.8 1038.48   114.5 1029.22   141.1 1019.61   163.3 1016.98
     178 1017.68     186 1015.36   189.9 1014.98   197.5 1015.39   207.3 1016.86
     217 1019.49   220.9  1019.9   250.2 1020.21   328.6 1024.07   344.1 1026.83
   349.7 1028.52   366.8 1034.67   375.3 1038.41   386.7 1038.75   394.7 1041.85
#Mann= 4, -1 ,  0
       0     0.1       0     186   0.045       0   197.5     0.1       0
  342.27    0.06       0
Bank Sta=186,197.5
XS Rating Curve= 0 ,0
Exp/Cntr=0.3,0.1

Type RM Length L Ch R = 1 ,44614   ,193,193.7,192.3
XS GIS Cut Line= 4
1619039.82139067426268.2043757481619057.74731632426302.560585528
1619252.18970798426525.6904001141619285.62554158426573.888717777
#Sta/Elev= 30
       0 1036.55     6.4 1033.99    30.1 1023.15    36.5 1021.44    44.7 1020.77
     121  1018.3   129.7 1014.22   145.9 1014.29   156.41013.067   168.7 1011.84
     174  1013.2   179.3 1015.34   186.4 1015.76   216.5 1015.25   248.8 1015.85
   261.5 1014.72   271.5 1015.62     292 1015.38     296 1016.43   305.5  1022.3
   311.2 1024.22   322.6 1024.16   333.2 1025.32     343 1025.57   347.9 1026.45
   357.7 1031.91   362.5 1034.07     382 1041.68   386.9 1044.65   393.4 1051.49
#Mann= 4, -1 ,  0
       0     0.1       0   156.4   0.045       0     174     0.1       0
  288.75    0.06       0
#XS Ineff= 2 , 0
          141.55 1019.66
Permanent Ineff=
       F       F
Bank Sta=156.4,174
XS Rating Curve= 0 ,0
Exp/Cntr=0.3,0.1

Type RM Length L Ch R = 1 ,44420   ,245.2,241.1,235.5
XS GIS Cut Line= 4
1618895.25220901  426423.23493781618942.17638548426449.314399049
1619098.34022724426631.5055477641619174.17453861426694.487962345
#Sta/Elev= 30
       0  1043.8     5.6 1037.66    10.9 1034.03    19.1  1029.7    37.6  1021.2
    48.7 1019.17   105.6 1012.05   108.4 1011.39   111.2 1010.91   126.4 1010.38
   131.7 1010.67   133.9 1011.32   142.4 1013.57   167.3 1015.54   185.7 1015.06
     198 1016.42   205.4 1015.48   224.7 1014.55   241.7 1014.84   252.9 1017.82
   277.9 1023.16   301.2 1026.78   321.9 1030.66   335.4 1035.38   353.1 1045.05
   363.8 1054.48   369.5 1060.44   376.6  1069.1   384.3 1077.85   392.2 1084.48
#Mann= 3, -1 ,  0
       0     0.1       0   108.4   0.045       0   133.9     0.1       0
Bank Sta=108.4,133.9
XS Rating Curve= 0 ,0
Exp/Cntr=0.3,0.1

Type RM Length L Ch R = 1 ,44179   ,250.6,252.9,253.5
XS GIS Cut Line= 3
1618747.10476475426635.1964510011619021.16750807426769.013074887
 1619113.9036328426819.359495546
#Sta/Elev= 30
       0 1060.37      10 1049.98    18.9  1042.7    27.8  1036.7    39.5  1030.3
    45.6 1028.33    63.4  1025.5    72.3 1023.28    82.5 1022.34    99.1 1019.51
   103.5 1017.19   112.4 1009.26   112.4 1009.25   121.3 1008.66   130.2 1009.33
   134.7 1010.46   152.5 1011.92     237 1013.44   267.4 1022.03   299.4 1024.49
   317.4 1028.23   337.5 1036.36   349.3 1043.21     363 1056.19   371.7 1066.42
   381.2 1075.88   385.7 1079.61   399.4 1086.95   407.1 1094.08   410.5 1096.42
#Mann= 5, -1 ,  0
       0     0.1       0   112.4   0.045       0   130.2     0.1       0
     210    0.06       0  314.99     0.1       0
#XS Ineff= 2 , 0
                          205.59         1016.72
Permanent Ineff=
       F       F
Bank Sta=112.4,130.2
XS Rating Curve= 0 ,0
Exp/Cntr=0.3,0.1

Type RM Length L Ch R = 1 ,43926   ,258.6,263,265.3
XS GIS Cut Line= 3
1618610.99427811426811.1436720461618845.71277366 426972.65918541
1618893.29980568427059.946367205
#Sta/Elev= 30
       0 1075.97     6.2  1070.1    16.2 1056.37    20.8 1050.63    35.3 1035.24
    39.2 1032.38      45 1029.28    58.9 1023.29      79 1017.92    88.1 1013.65
    98.5 1011.84   108.2 1007.44   115.4 1007.02   121.91007.428   142.2  1009.9
   177.3 1008.91   190.7 1010.75   197.4 1010.55   208.9 1011.24   224.7 1013.53
   266.4 1016.52   289.3 1020.92     303 1023.06   312.1 1023.68   334.9 1030.45
   353.1 1033.55   357.7 1035.07   363.3 1037.32   372.1 1042.16   384.3 1051.24
#Mann= 5, -1 ,  0
       0     0.1       0   108.2   0.045       0   121.9     0.1       0
     270    0.06       0  294.92     0.1       0
Bank Sta=108.2,121.9
XS Rating Curve= 0 ,0
Exp/Cntr=0.3,0.1

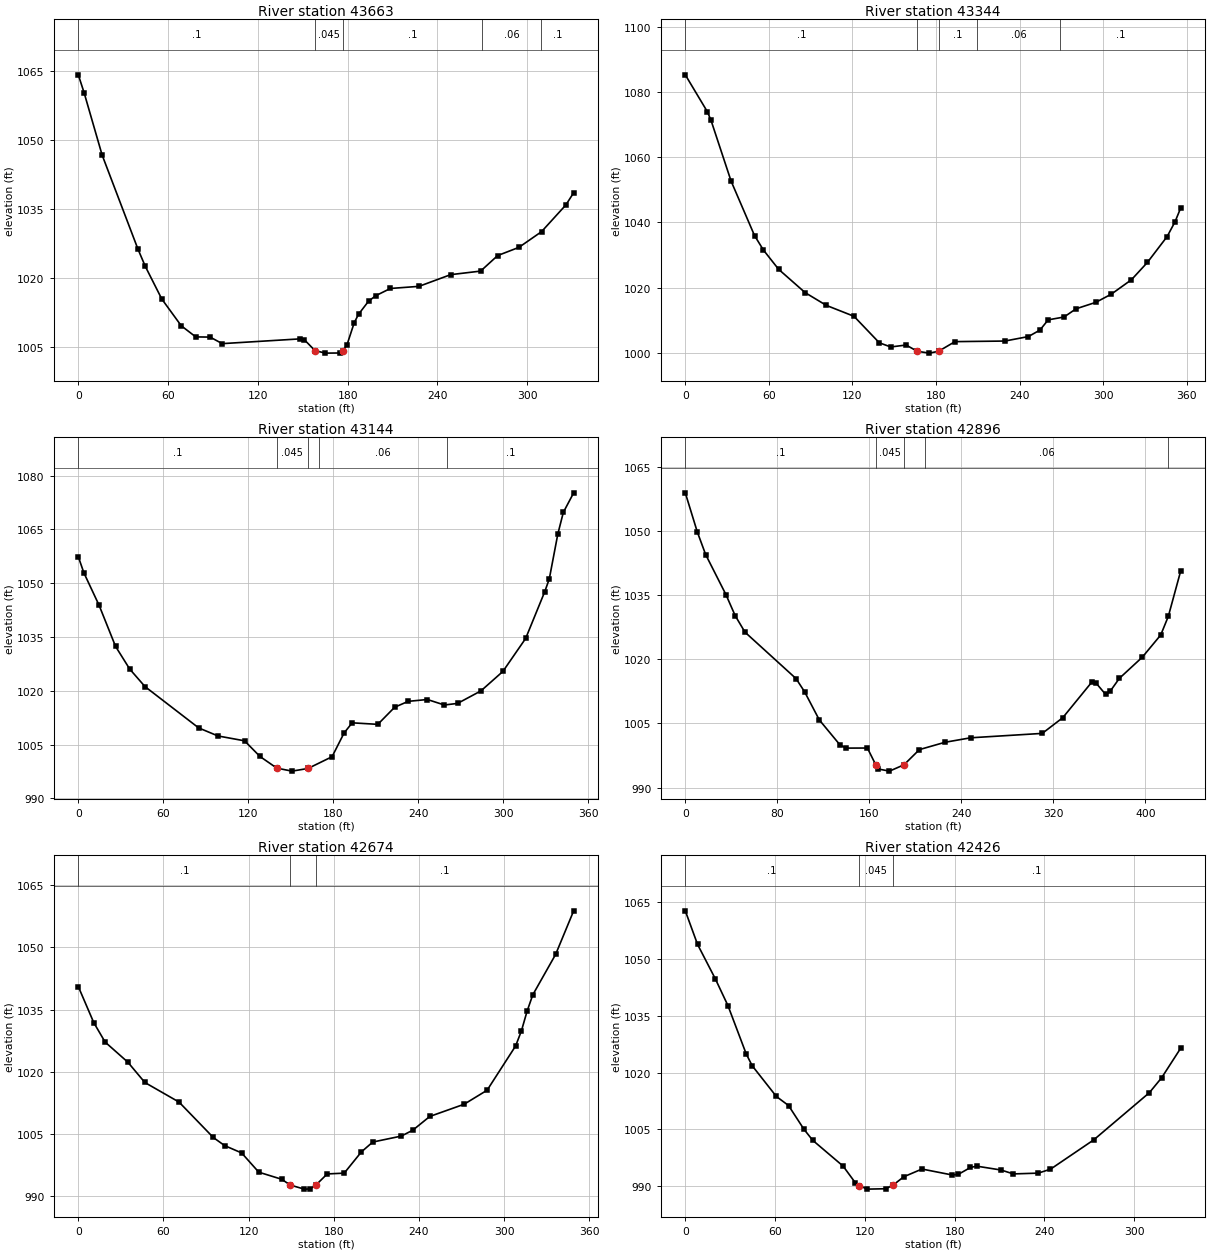
Type RM Length L Ch R = 1 ,43663   ,320.2,319,314.4
XS GIS Cut Line= 3
1618487.84148725426927.3509109811618621.20302541427126.372309298
1618677.26422036427198.738089019
#Sta/Elev= 30
       0 1064.13     3.9 1060.22    15.9 1046.74    39.9 1026.28    44.8 1022.55
    55.8 1015.48    68.8 1009.68    78.5 1007.26    88.1 1007.22    96.2  1005.8
   148.1 1006.83     151 1006.67   158.21004.293   165.1 1003.74   174.8 1003.77
   176.9  1004.3   179.6 1005.55   184.4 1010.32   187.3 1012.17     194 1015.01
   198.8  1016.2   208.6 1017.77   227.7 1018.23   248.9 1020.77   268.9 1021.54
   280.3 1024.91   294.5 1026.69   309.6 1030.09   325.9  1035.9   331.1 1038.55
#Mann= 5, -1 ,  0
       0     0.1       0   158.2   0.045       0   176.9     0.1       0
  269.57    0.06       0  309.57     0.1       0
Bank Sta=158.2,176.9
XS Rating Curve= 0 ,0
Exp/Cntr=0.3,0.1

Type RM Length L Ch R = 1 ,43344   ,199.4,200,200.3
XS GIS Cut Line= 3
1618229.57678648427148.7242691381618267.45911022427180.290610181
1618506.62716104427371.651995793
#Sta/Elev= 30
       0 1085.21    15.9 1073.88    18.5 1071.23    32.9 1052.64    49.7 1035.99
    56.1 1031.55      67 1025.66      86 1018.53   101.2 1014.62   121.1 1011.27
   139.3 1003.15   147.5 1001.88   158.5 1002.47   166.6 1000.55   175.2  999.99
   181.81000.555   193.6 1003.51   229.4 1003.69   246.3 1005.06   254.6 1007.05
   260.5 1010.18   271.9 1011.05   280.5 1013.56   294.7 1015.54   305.8 1018.04
   320.3 1022.47   331.7 1027.75   345.9 1035.69   351.6 1040.24   355.6 1044.41
#Mann= 5, -1 ,  0
       0     0.1       0   166.6   0.045       0   181.8     0.1       0
  209.31    0.06       0  269.31     0.1       0
Bank Sta=166.6,181.8
XS Rating Curve= 0 ,0
Exp/Cntr=0.3,0.1

Type RM Length L Ch R = 1 ,43144   ,243.1,247.7,251.5
XS GIS Cut Line= 3
1618117.25034338427302.2011374771618295.07915253427464.008101669
  1618367.522178427546.000822044
#Sta/Elev= 30
       0  1057.4     3.9 1052.93    14.7 1043.83    26.3 1032.39    36.3 1026.07
    47.1 1021.18      85 1009.66    98.6 1007.42   117.4 1006.06   128.3 1001.69
   140.2  998.44   150.9  997.61   162.2  998.35   179.2 1001.63   187.7 1008.26
   193.4 1011.08   211.5 1010.65   223.4 1015.43     233 1017.07   246.5 1017.58
   258.5 1016.05   267.8 1016.49   284.3 1019.98   299.8  1025.4   315.9 1034.61
   329.4 1047.67   332.6 1051.23   338.6  1063.7   342.5 1069.76   349.8 1075.21
#Mann= 5, -1 ,  0
       0     0.1       0   140.2   0.045       0   162.2     0.1       0
     170    0.06       0  260.43     0.1       0
Bank Sta=140.2,162.2
XS Rating Curve= 0 ,0
Exp/Cntr=0.3,0.1

Type RM Length L Ch R = 1 ,42896   ,219.9,222.5,227.6
XS GIS Cut Line= 5
1617951.23459509427391.9672466651617980.12616368427468.463117565
1618027.32442374427540.7204613921618102.45450639427694.900688111
1618098.20879099427785.774711868
#Sta/Elev= 30
       0 1058.89    10.4 1049.78    17.7 1044.46    35.3 1035.12    43.4 1030.16
    51.9 1026.32    96.3 1015.46   103.7 1012.39   116.5 1005.81   134.4  999.99
   139.6  999.22   158.3  999.24   165.6   995.3   167.9  994.33   177.5  993.84
   190.1  995.32   203.5  998.87   225.7 1000.58     248 1001.63   310.3 1002.66
   328.1 1006.32   353.2 1014.59   357.2 1014.38   365.3  1011.8   369.3 1012.49
   377.3 1015.52   397.3 1020.48   413.3 1025.67   419.9 1030.03   430.6 1040.59
#Mann= 5, -1 ,  0
       0     0.1       0   165.6   0.045       0   190.1     0.1       0
  208.08    0.06       0  419.59     0.1       0
Bank Sta=165.6,190.1
XS Rating Curve= 0 ,0
Exp/Cntr=0.3,0.1

Type RM Length L Ch R = 1 ,42674   ,248.7,247.9,246.8
XS GIS Cut Line= 4
1617814.38338418427457.6118229281617812.79807105 427523.62208586
1617827.11308988 427683.690023661617842.37538418427805.139502859
#Sta/Elev= 30
       0 1040.53    10.9 1031.84    18.9 1027.16    34.9 1022.32    46.9 1017.42
      71  1012.7    95.1 1004.18   103.1 1002.22   115.1 1000.45   127.2  995.81
   143.3  994.11   149.4992.7065   159.3  991.73   163.3  991.77   167.3  992.66
   175.4  995.39   187.4  995.58   199.5  1000.7   207.5 1003.07   227.6 1004.51
   235.7 1005.92   247.7 1009.24   271.9 1012.18   288.1 1015.56   308.2 1026.23
   312.3 1029.88   316.3 1034.63   320.3 1038.55   336.4 1048.29   349.1 1058.78
#Mann= 3, -1 ,  0
       0     0.1       0   149.4   0.045       0   167.3     0.1       0
Bank Sta=149.4,167.3
XS Rating Curve= 0 ,0
Exp/Cntr=0.3,0.1

Type RM Length L Ch R = 1 ,42426   ,223.1,222.8,222.2
XS GIS Cut Line= 3
1617553.18111487427500.4068605841617585.13811487427696.803459486
1617617.75128813427824.789060294
#Sta/Elev= 30
       0 1062.78     8.2  1053.9    20.1 1044.78    28.5 1037.73    40.7 1024.97
    44.7 1021.83    60.9 1013.69      69 1011.31    79.3 1005.03    85.2  1002.1
   105.5  995.28   113.6  990.91   116.1  990.14   121.7   989.2   133.9   989.3
   138.6  990.17     146  992.46   158.2  994.51   178.4  992.94   182.5  993.11
   190.6  994.92   194.7  995.28   211.1  994.25   219.3  993.22   235.9  993.43
   244.1  994.47     273 1002.22   310.2  1014.7   318.4 1018.65   331.1 1026.44
#Mann= 3, -1 ,  0
       0     0.1       0   116.1   0.045       0   138.6     0.1       0
Bank Sta=116.1,138.6
XS Rating Curve= 0 ,0
Exp/Cntr=0.3,0.1

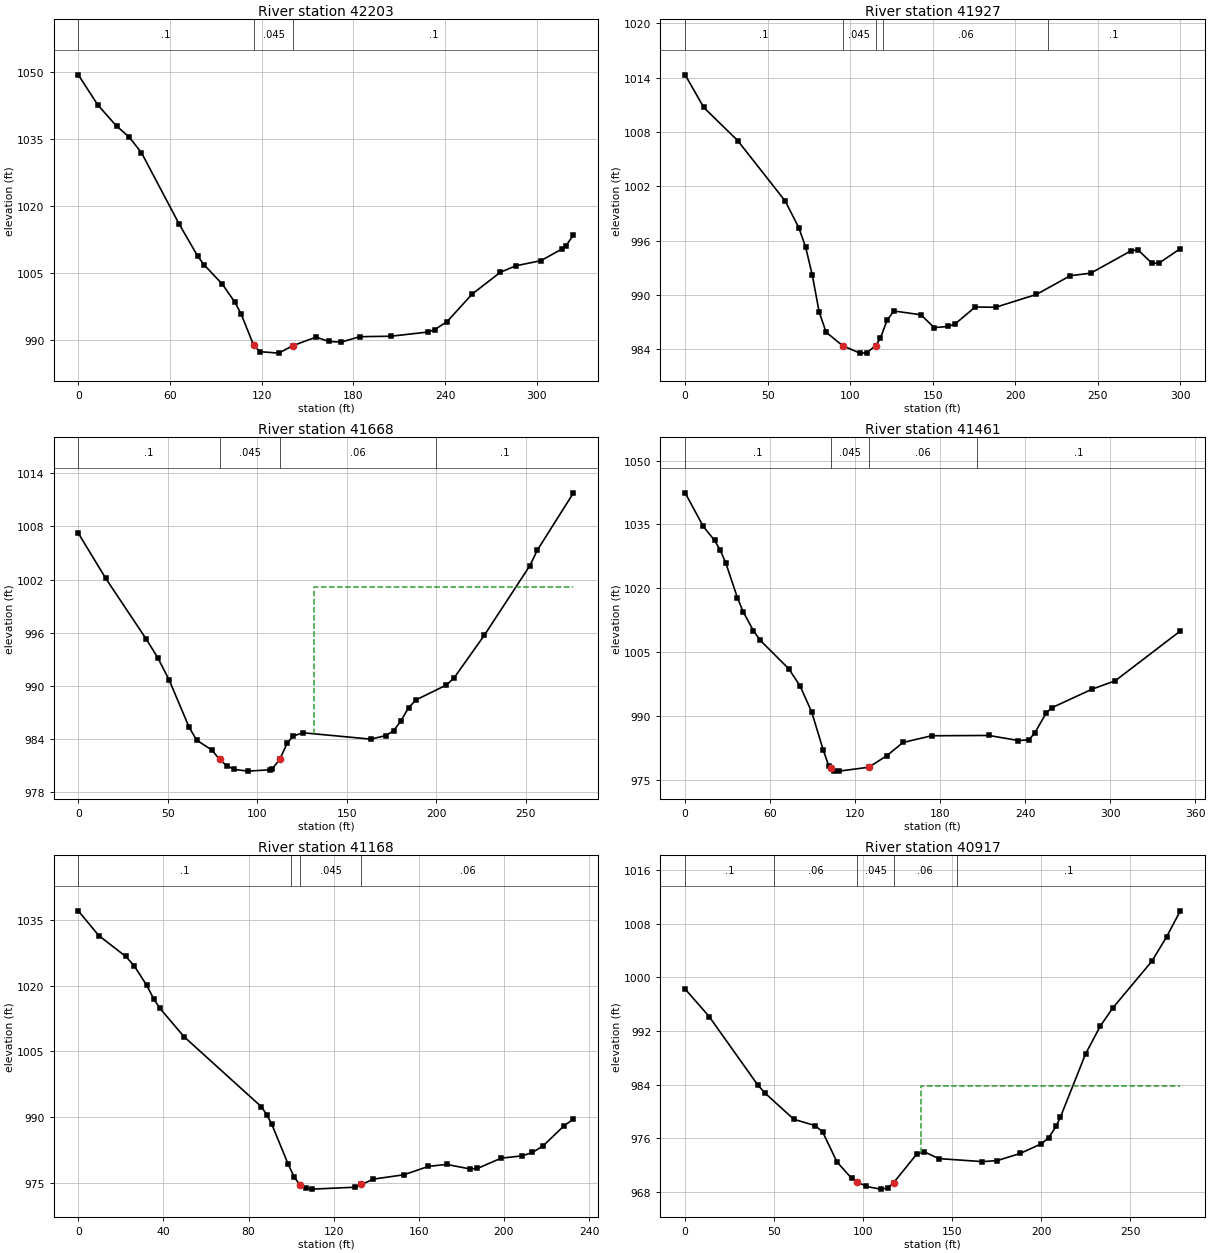
Type RM Length L Ch R = 1 ,42203   ,273.4,276.5,283
XS GIS Cut Line= 3
1617366.57022784427547.9886877471617348.88530696427637.340039561
1617395.62769304427865.467425642
#Sta/Elev= 30
       0 1049.31    12.8 1042.56      25 1037.86    33.2 1035.44    41.3 1031.92
    65.8 1016.07      78 1008.85    82.1 1006.91    94.3  1002.5   102.5  998.44
   106.6  995.79   114.8  988.81   118.8  987.43   131.1   987.1   140.6   988.8
   155.6  990.68   163.8  989.72   171.9  989.55   184.2  990.77   204.6  990.88
   229.1  991.83   233.2  992.37   241.3  994.14   257.7  1000.3   276.1 1005.16
   286.3 1006.63   302.6 1007.76   316.8 1010.44   318.9 1011.02     324 1013.52
#Mann= 3, -1 ,  0
       0     0.1       0   114.8   0.045       0   140.6     0.1       0
Bank Sta=114.8,140.6
XS Rating Curve= 0 ,0
Exp/Cntr=0.3,0.1

Type RM Length L Ch R = 1 ,41927   ,258.5,258.8,260.1
XS GIS Cut Line= 2
1617110.95181832427561.514806106 1617041.1727007427853.344275544
#Sta/Elev= 30
       0 1014.32    11.3 1010.71    31.9 1007.04    60.7 1000.35    68.9  997.41
      73  995.28    77.1  992.15    81.2  988.12    85.4  985.87    95.5984.3619
   105.9  983.55     110  983.58   115.4  984.37   118.3  985.18   122.4   987.2
   126.5  988.21   142.9  987.79   150.9  986.37   159.4   986.5   163.5  986.76
   175.8  988.65   188.2  988.62   212.9  990.04   233.4  992.11   245.8  992.39
   270.4  994.88   274.5  994.95   282.8  993.51   286.9  993.47   300.1   995.1
#Mann= 5, -1 ,  0
       0     0.1       0    95.5   0.045       0   115.4     0.1       0
     120    0.06       0     220     0.1       0
Bank Sta=95.5,115.4
XS Rating Curve= 0 ,0
Exp/Cntr=0.3,0.1

Type RM Length L Ch R = 1 ,41668   ,208.4,206.6,204.1
XS GIS Cut Line= 2
1616874.14842575427486.0882453251616783.52720639427747.675903424
#Sta/Elev= 30
       0 1007.23    15.3 1002.14    38.1  995.24    44.4  993.18    50.7   990.7
    61.9  985.35    66.1  983.88    74.6  982.77      79   981.7      83  980.98
    87.3  980.57    94.7  980.38   107.3  980.53   108.4  980.64   112.7  981.74
   116.7  983.51   119.9  984.31   125.4  984.71   163.5  983.99   171.9  984.39
   176.2  984.93   180.4  986.06   184.6  987.54   188.9  988.43   205.8   990.1
     210  990.89     227  995.72   252.4 1003.56   256.6 1005.32   276.8 1011.78
#Mann= 4, -1 ,  0
       0     0.1       0      79   0.045       0   112.7    0.06       0
     200     0.1       0
#XS Ineff= 2 , 0
                          131.56         1001.18
Permanent Ineff=
       F       F
Bank Sta=79,112.7
XS Rating Curve= 0 ,0
Exp/Cntr=0.3,0.1

Type RM Length L Ch R = 1 ,41461   ,299.7,292.9,279
XS GIS Cut Line= 4
1616672.63671991427367.7943273141616671.71958311427393.908963219
1616645.74728649 427591.386320631616666.68076835427713.916964251
#Sta/Elev= 30
       0 1042.43    12.8 1034.54    20.8 1031.27    24.8 1028.96    28.8 1025.86
    36.9 1017.82    40.9 1014.55    48.2 1010.07      53 1007.81    73.2 1001.12
    81.2  997.06    89.3  991.03    97.4  982.18   101.4  978.32   102.8977.8912
   105.4  977.13   108.6  977.11   129.6  978.02   142.2  980.69   153.8  983.83
     174  985.41   214.4  985.48   235.3  984.29   242.7  984.47   246.8  986.05
   254.9  990.76   258.9  991.99   287.3  996.35   303.6  998.31   349.6    1010
#Mann= 4, -1 ,  0
       0     0.1       0   102.8   0.045       0   129.6    0.06       0
  206.13     0.1       0
Bank Sta=102.8,129.6
XS Rating Curve= 0 ,0
Exp/Cntr=0.3,0.1

Type RM Length L Ch R = 1 ,41168   ,246.9,251.3,256
XS GIS Cut Line= 2
1616336.94271182427494.3606270751616471.34327116427684.288220306
#Sta/Elev= 30
       0 1037.14     9.6 1031.49    22.3 1026.71    26.3 1024.55    32.1 1020.14
    35.4 1017.04    38.3 1014.87    49.7 1008.35      86  992.35    88.6  990.51
    90.9  988.36    98.5  979.34   101.4   976.3   104.3  974.36   107.1  973.65
     110   973.5   130.1  973.94     133  974.56   138.7  975.79   153.1  976.79
   164.5   978.7   173.1  979.15     184  978.12   187.5  978.22   198.7  980.58
   208.5   981.1   213.4  981.88   218.3  983.34   228.1  987.91   232.7  989.55
#Mann= 4, -1 ,  0
       0     0.1       0     100    0.06       0   104.3   0.045       0
     133    0.06       0
Bank Sta=104.3,133
XS Rating Curve= 0 ,0
Exp/Cntr=0.3,0.1

Type RM Length L Ch R = 1 ,40917   ,241.8,247.7,252.6
XS GIS Cut Line= 3
1616180.68940677427624.4261609421616204.47968644427764.795093208
1616238.89075426427895.962466133
#Sta/Elev= 30
       0  998.25    13.5  994.15    40.7  983.98    44.7  982.78      61  978.84
    73.1  977.89    77.2  976.94    85.3  972.46    93.4  970.06    96.7969.5208
   101.5  968.84   109.7  968.43   113.7  968.58     117969.3688   129.9  973.62
     134  974.02   142.4  972.98   166.9  972.53   175.2  972.68   188.2  973.76
     200  975.19   204.1   976.1   208.3  977.81   210.7  979.17   224.8  988.59
   233.1  992.74   240.1  995.44     262 1002.39   270.3 1006.04     278 1009.91
#Mann= 5, -1 ,  0
       0     0.1       0      50    0.06       0    96.7   0.045       0
     117    0.06       0  152.37     0.1       0
#XS Ineff= 2 , 0
                          132.21          983.82
Permanent Ineff=
       F       F
Bank Sta=96.7,117
XS Rating Curve= 0 ,0
Exp/Cntr=0.3,0.1