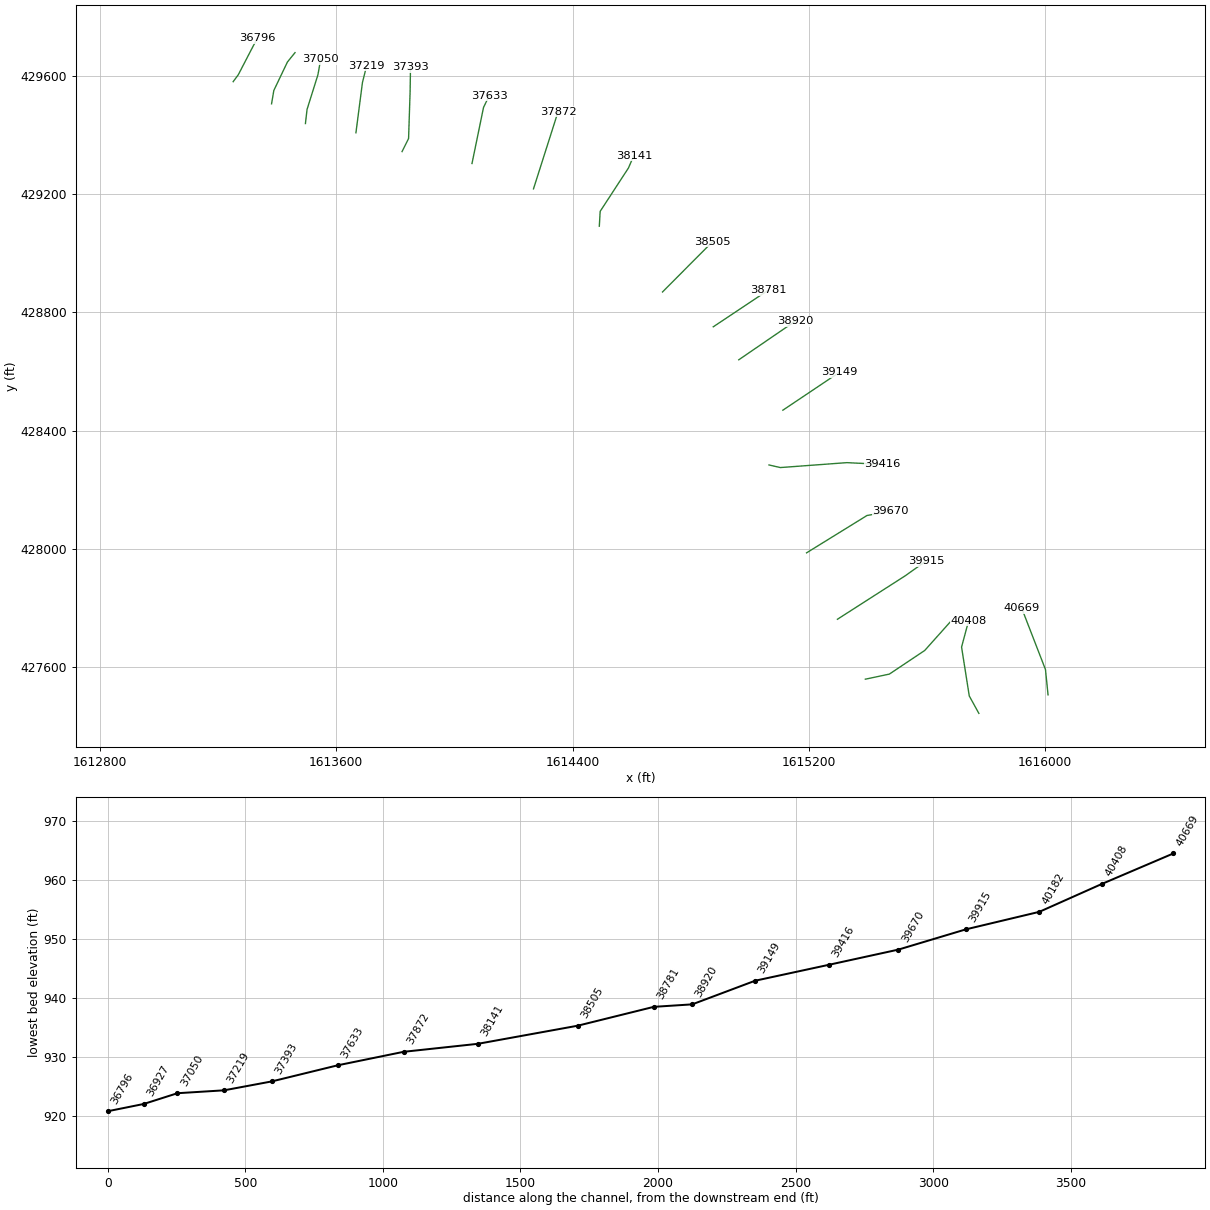
HEC-RAS study PROCTRCK.prj: PROCTRCK

--- PROCTRCK.g01 (geometry) --- (continued)

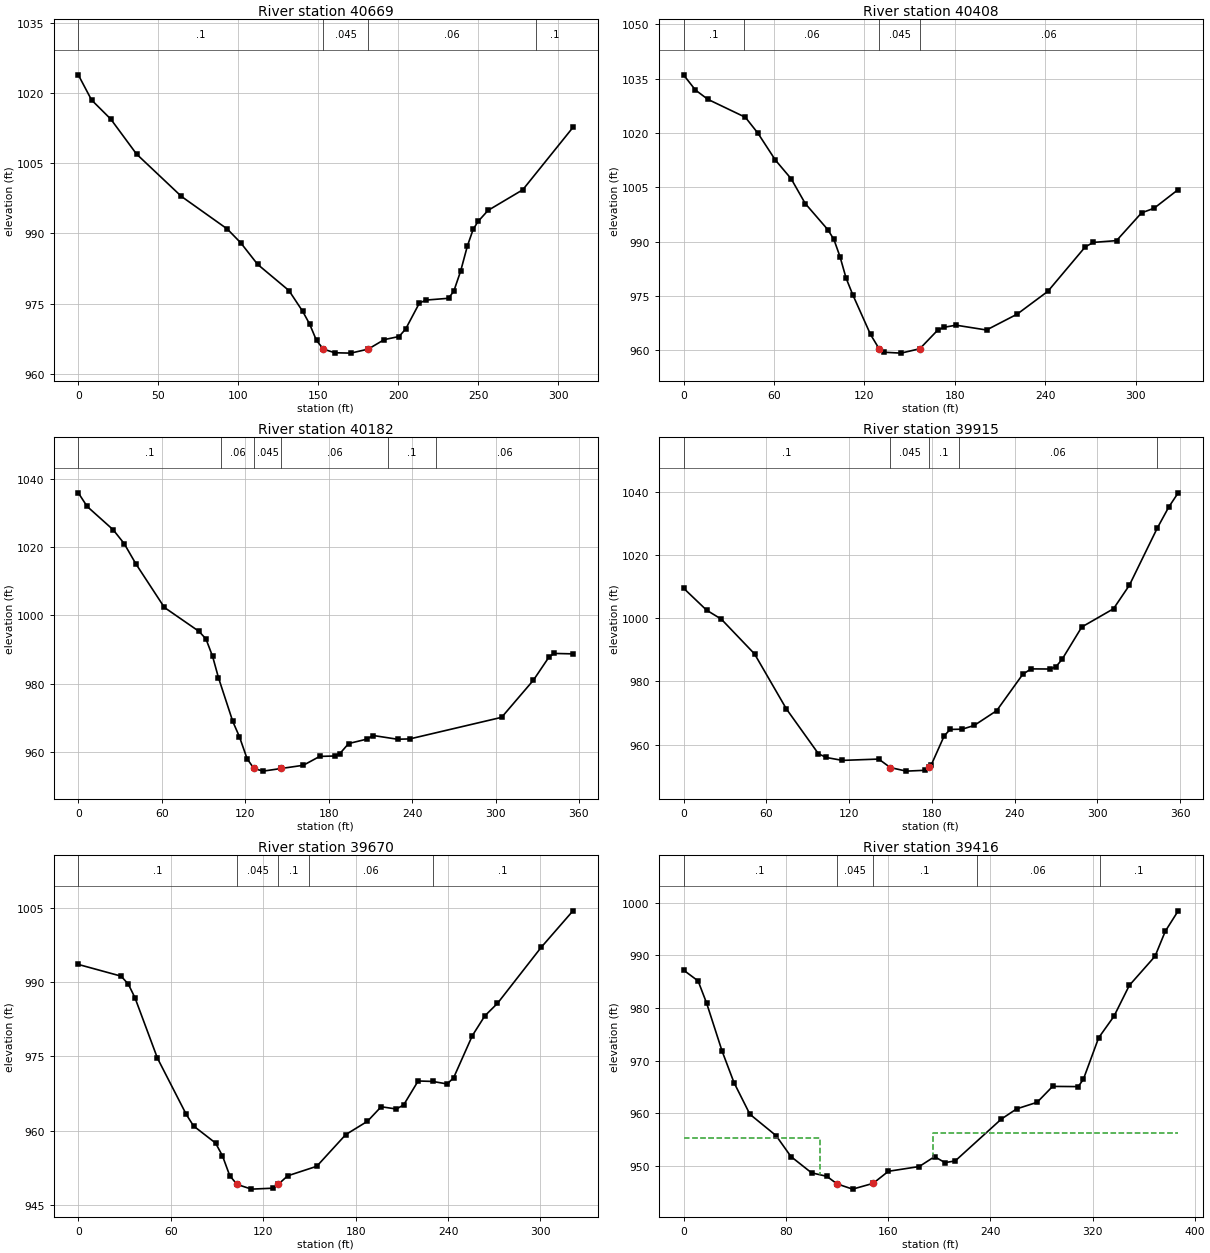
Type RM Length L Ch R = 1 ,40669   ,263.3,261.2,257.6
XS GIS Cut Line= 3
1616010.14752355 427504.328399591616001.47719145427590.080117624
 1615920.9542289427798.046850226
#Sta/Elev= 30
       0 1023.86     8.3 1018.49    20.3 1014.41    36.4 1006.95    64.5  997.89
    93.1  990.95   101.5  988.01   112.1  983.39   131.7  977.79   140.3  973.34
   144.6  970.64   148.9  967.14   153.2   965.3   160.3  964.52   170.3  964.44
   181.2 965.297   191.2  967.32   200.5  967.99   204.6  969.58   213.2  975.13
   217.5  975.77   231.4  976.15   234.7  977.66     239  981.97   243.2  987.31
   246.8  990.86   249.9  992.56   256.1  994.91   277.8  999.31   309.2 1012.64
#Mann= 4, -1 ,  0
       0     0.1       0   153.2   0.045       0   181.2    0.06       0
  286.19     0.1       0
Bank Sta=153.2,181.2
XS Rating Curve= 0 ,0
Exp/Cntr=0.3,0.1

Type RM Length L Ch R = 1 ,40408   ,237,226.3,212.4
XS GIS Cut Line= 4
1615775.90432769427441.5839189721615743.42037131427500.545402465
1615717.34269304427666.2835743581615741.42921282427756.012504764
#Sta/Elev= 30
       0 1036.03     7.9 1031.84    16.1 1029.28      41 1024.32    49.3 1019.95
    60.9 1012.52    71.4 1007.34    80.7 1000.53    95.7   993.3    99.7  990.63
   103.8  985.81   107.8  979.94   112.2  975.38     124  964.39   129.7  960.45
   133.2  959.49   144.2  959.25   156.7960.4638   168.5  965.58   172.6  966.37
   180.7  966.96   200.9  965.63   221.2     970   241.6  976.31   266.4  988.58
   271.8   989.8   287.1  990.29   303.7  997.95     312  999.22     328 1004.37
#Mann= 4, -1 ,  0
       0     0.1       0      40    0.06       0   129.7   0.045       0
   156.7    0.06       0
Bank Sta=129.7,156.7
XS Rating Curve= 0 ,0
Exp/Cntr=0.3,0.1

Type RM Length L Ch R = 1 ,40182   ,265.6,267.3,267.9
XS GIS Cut Line= 4
1615391.56614933427557.4749374591615472.72083878427574.604187174
1615592.65878151 427654.750511971615678.22558074427750.577845529
#Sta/Elev= 30
       0 1035.82     6.4 1031.83    25.1 1025.03      33 1020.99    41.4 1015.09
    61.9 1002.35    86.8  995.36    91.8  993.16    96.6  988.03   100.8  981.83
   111.1  969.05   115.9  964.56   121.4  958.15   126.3 955.323   132.9  954.55
   146.1955.3318   161.8  956.26   173.6  958.85   184.8  958.97   188.1  959.68
   194.4  962.61   207.3  963.87   212.1  964.95   229.6  963.86   238.4  963.96
   304.4  970.26   327.2  981.08   338.6  987.95   342.2  988.92   355.7  988.79
#Mann= 6, -1 ,  0
       0     0.1       0  102.94    0.06       0   126.3   0.045       0
   146.1    0.06       0  222.94     0.1       0  257.19    0.06       0
Bank Sta=126.3,146.1
XS Rating Curve= 0 ,0
Exp/Cntr=0.3,0.1

Type RM Length L Ch R = 1 ,39915   ,244.9,244.7,244.5
XS GIS Cut Line= 3
1615297.01788132427760.5032673981615526.73761286427907.828305901
1615596.55819463427957.560501588
#Sta/Elev= 30
       0 1009.55    16.7 1002.59    27.4  999.73    51.5  988.71    74.6  971.27
    97.8  957.09   103.5   955.9   115.2  954.98   141.5   955.4   149.9  952.71
   161.5  951.58   174.7  951.84   177.9  952.76   179.5  953.46     189  962.77
   193.3   964.8     202  964.86   210.7  966.05     227  970.73     246   982.3
     252  983.97   265.7  983.93   269.8  984.57   274.4  986.98   288.7  997.24
   311.7 1003.02   323.2 1010.47   343.3 1028.47   351.8 1035.28   358.6 1039.75
#Mann= 5, -1 ,  0
       0     0.1       0   149.9   0.045       0   177.9     0.1       0
     200    0.06       0   342.9     0.1       0
Bank Sta=149.9,177.9
XS Rating Curve= 0 ,0
Exp/Cntr=0.3,0.1

Type RM Length L Ch R = 1 ,39670   ,262.3,253.4,249.1
XS GIS Cut Line= 3
1615192.48091876427985.5065358561615397.22018934428112.073267398
 1615476.4287326428125.854117624
#Sta/Elev= 30
       0   993.6    27.8  991.23    32.5   989.6    36.8  986.86    51.4  974.63
    70.1  963.27    74.8  960.94    89.1  957.48    93.6  954.89    98.3  950.89
     103  949.12   112.4  948.16   126.5  948.35   129.8  949.13   135.9  950.85
   154.8  952.78   173.6  959.18   187.7  961.88   196.6  964.82   206.5  964.36
   211.2  965.19   220.6  970.03     230  969.94   239.4  969.43   243.6  970.66
   255.8  979.21   263.9   983.2   272.1  985.73   300.5  997.07   321.1 1004.44
#Mann= 5, -1 ,  0
       0     0.1       0     103   0.045       0   129.8     0.1       0
     150    0.06       0     230     0.1       0
Bank Sta=103,129.8
XS Rating Curve= 0 ,0
Exp/Cntr=0.3,0.1

Type RM Length L Ch R = 1 ,39416   ,264,267.4,277.2
XS GIS Cut Line= 4
1615065.20694953428283.3146415151615103.69896899428274.462905333
1615328.84369869428291.126039403 1615450.2593657428285.182046613
#Sta/Elev= 30
       0   987.2    11.4  985.14    18.1   980.9    30.2  971.78    39.5  965.81
    51.9  959.81    72.4  955.74      84  951.77   100.1  948.68   112.1  948.01
     120  946.58   132.2  945.58   148.2  946.67   160.2  948.97   184.3  949.87
   196.3  951.75   204.4  950.62   212.4  950.93   248.5  958.89   260.5  960.83
   276.5  962.08   288.6   965.1   308.6  965.06   312.6  966.42   324.6  974.34
   336.6  978.44   348.6   984.3   368.7  989.83   376.7  994.58   386.8  998.46
#Mann= 5, -1 ,  0
       0     0.1       0     120   0.045       0   148.2     0.1       0
   229.5    0.06       0  325.26     0.1       0
#XS Ineff= 2 , 0
          106.71  955.33  194.83          956.16
Permanent Ineff=
       F       F
Bank Sta=120,148.2
XS Rating Curve= 0 ,0
Exp/Cntr=0.3,0.1

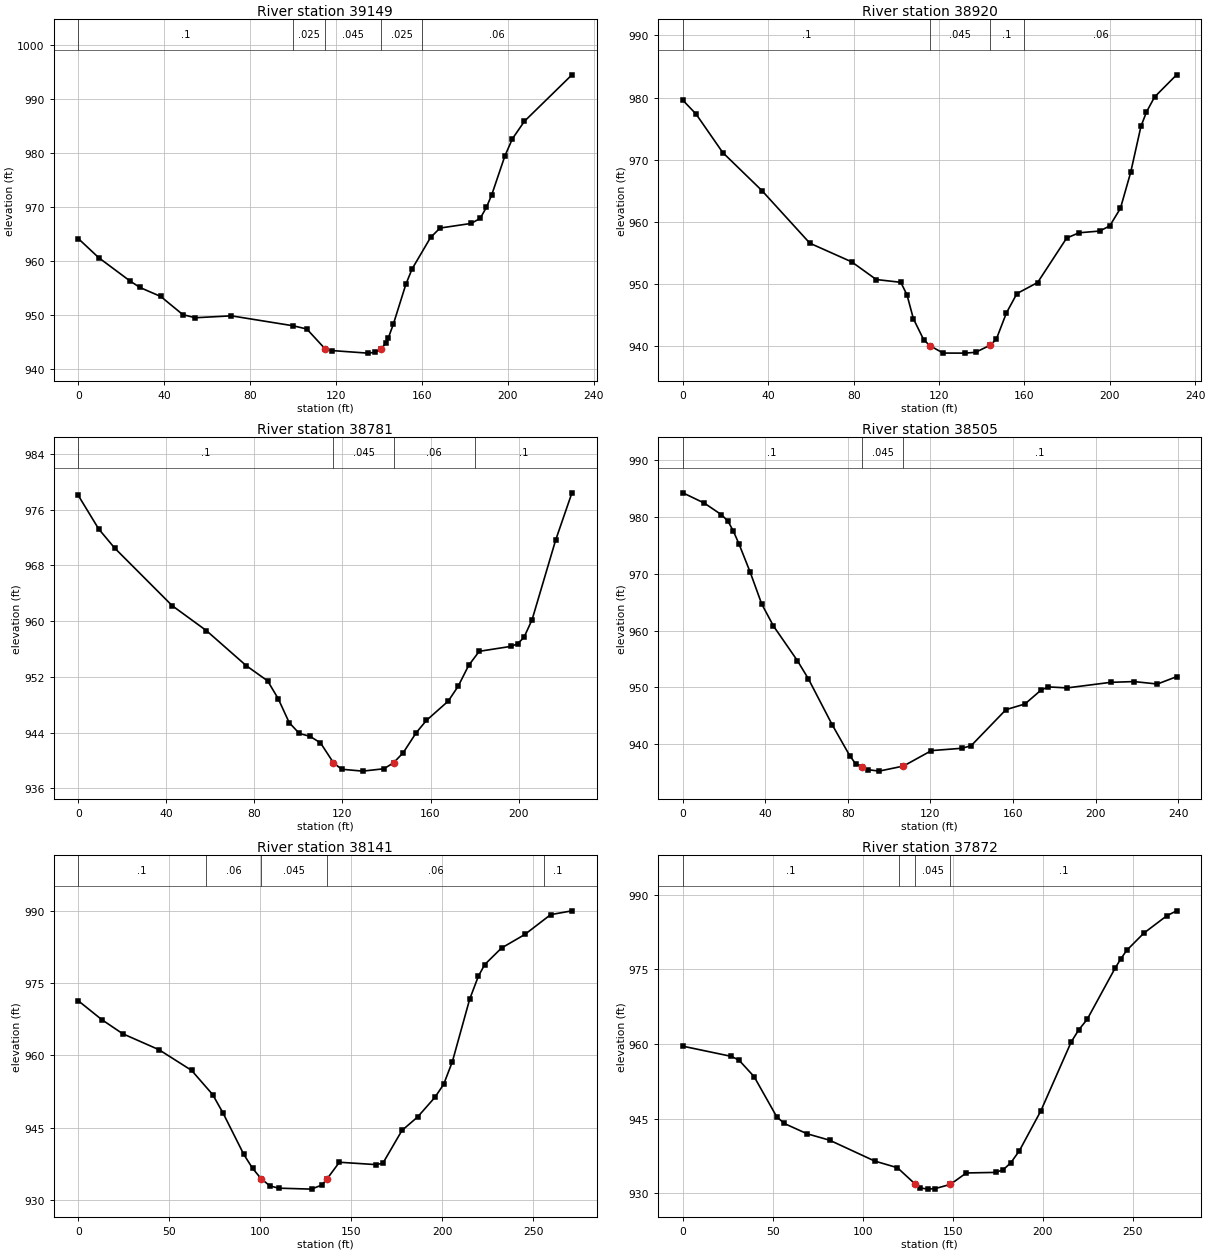
Type RM Length L Ch R = 1 ,39149   ,228.5,228.7,228.4
XS GIS Cut Line= 2
1615112.25253289428468.8256139191615303.11419018428596.843190182
#Sta/Elev= 30
       0  964.13     9.5  960.59    23.9  956.32    28.7  955.06    38.4  953.39
    48.7  950.02    54.5  949.45    71.3   949.8     100  947.96   106.4  947.36
   114.8943.7266   117.9  943.37   134.7  942.89   138.1  943.03     141   943.7
   143.1   944.7   144.3  945.67   146.7  948.29   152.5  955.65   155.4   958.5
     164  964.33   168.4  966.07   182.9  966.93   187.1  967.87     190  969.92
   192.5  972.27   198.6  979.45   202.1  982.63   207.7  985.87   229.8  994.47
#Mann= 5, -1 ,  0
       0     0.1       0     100   0.025       0   114.8   0.045       0
     141   0.025       0     160    0.06       0
Bank Sta=114.8,141
XS Rating Curve= 0 ,0
Exp/Cntr=0.3,0.1

Type RM Length L Ch R = 1 ,38920   ,140,139.4,139.7
XS GIS Cut Line= 2
1614963.03436824428639.6349948651615153.82754191428770.344130414
#Sta/Elev= 30
       0  979.57     6.2  977.34    18.7  971.15      37  965.05    59.5  956.57
    79.1  953.57    90.6  950.73   102.1  950.28     105  948.26     108  944.42
   112.8  941.06   115.7940.0941   121.9   938.9   132.2  938.89   137.1  939.02
   143.9940.1523   146.8  941.09   151.6  945.37   156.5  948.47   166.2  950.25
   179.8   957.4   185.6  958.25   195.3  958.53     200  959.36     205  962.19
   209.8  967.98   214.6  975.36   217.2  977.69     221   980.1   231.3  983.66
#Mann= 4, -1 ,  0
       0     0.1       0   115.7   0.045       0   143.9     0.1       0
     160    0.06       0
Bank Sta=115.7,143.9
XS Rating Curve= 0 ,0
Exp/Cntr(USF)=0,0
Exp/Cntr=0.3,0.1

Type RM Length L Ch R = 1 ,38781   ,266.6,276.3,275.6
XS GIS Cut Line= 2
1614876.59768183428751.3702236411615063.17443177  428875.7547236
#Sta/Elev= 30
       0  978.04     9.3  973.21    16.5  970.49    42.7   962.2    58.2  958.63
    76.3   953.6      86  951.42    90.8  948.87    95.8  945.43   100.4  943.87
   105.2  943.47     110  942.53   115.9  939.67   119.6  938.74   129.2  938.47
   138.8  938.81   143.2939.6633   147.6  941.12   153.5  943.99   158.1  945.74
     168  948.51   172.5  950.63   177.3  953.64   182.1  955.66   196.5  956.37
   199.5  956.74   202.4  957.65   206.1   960.2   216.8  971.62   224.2   978.4
#Mann= 4, -1 ,  0
       0     0.1       0   115.9   0.045       0   143.2    0.06       0
     180     0.1       0
Bank Sta=115.9,143.2
XS Rating Curve= 0 ,0
Exp/Cntr(USF)=0,0
Exp/Cntr=0.3,0.1

Type RM Length L Ch R = 1 ,38505   ,356.8,363.4,365.7
XS GIS Cut Line= 2
1614704.77841494428869.4300880091614873.43536404429039.141143037
#Sta/Elev= 30
       0  984.23    10.4  982.42    18.7  980.38    21.8  979.27    24.4  977.56
    27.2  975.24    32.6   970.3    38.2  964.69    43.9  960.81    55.5  954.72
    60.8  951.54    72.4  943.42    80.9  937.99    83.8  936.54    86.6  936.09
    89.9  935.53    95.1  935.28   106.9  936.17   120.5  938.89   135.2   939.3
   139.7  939.74   156.6  946.09   165.8  947.09   173.6  949.53   177.1  950.09
   186.3  949.92   207.4   950.9   218.7  951.03     230   950.6   239.3  951.89
#Mann= 3, -1 ,  0
       0     0.1       0    86.6   0.045       0   106.9     0.1       0
Bank Sta=86.6,106.9
XS Rating Curve= 0 ,0
Exp/Cntr(USF)=0,0
Exp/Cntr=0.3,0.1

Type RM Length L Ch R = 1 ,38141   ,268.9,269.4,273.3
XS GIS Cut Line= 4
1614490.79155693429092.2220262111614493.63764295429142.502879161
1614589.45587216429289.5506566541614607.48108359429331.293251556
#Sta/Elev= 30
       0  971.31    12.9   967.4    24.4  964.47    44.4  961.14    62.3  956.85
    73.9  951.82    79.6  947.98      91   939.4    95.8  936.53   100.5  934.38
   105.3  932.89   110.1  932.41   128.2  932.21     134  933.09   136.8934.3735
   143.5  937.79   163.5   937.3   167.4  937.58   177.9  944.39   186.5  947.19
     196  951.26   200.8  953.96   205.6  958.68   215.1  971.63   219.9  976.42
   223.4  978.83   232.6  982.25   245.4  985.06   259.6  989.18   271.3  989.97
#Mann= 5, -1 ,  0
       0     0.1       0   70.36    0.06       0   100.5   0.045       0
   136.8    0.06       0  255.87     0.1       0
Bank Sta=100.5,136.8
XS Rating Curve= 0 ,0
Exp/Cntr(USF)=0,0
Exp/Cntr=0.3,0.1

Type RM Length L Ch R = 1 ,37872   ,238.3,239.3,240.3
XS GIS Cut Line= 2
1614267.90183613429218.811910949 1614351.1892184 429480.38634589
#Sta/Elev= 30
       0  959.58      27  957.53    31.2  956.78    39.6  953.47    52.2  945.39
    56.4  944.05      69  941.99    81.6  940.69   106.6  936.51   119.3  935.16
   129.2931.8593   131.9  931.12   136.1  930.86   140.3  930.97   148.7  931.81
   157.6  934.11   173.9  934.22   178.1  934.75   182.3  936.14   187.1  938.57
     199  946.56   215.9  960.43   220.1  962.86   224.8  964.98   240.3  975.25
   243.5  977.13   246.7  978.81   256.3   982.3     269  985.77   274.5  986.78
#Mann= 4, -1 ,  0
       0     0.1       0     120    0.06       0   129.2   0.045       0
   148.7     0.1       0
Bank Sta=129.2,148.7
XS Rating Curve= 0 ,0
Exp/Cntr(USF)=0,0
Exp/Cntr=0.3,0.1

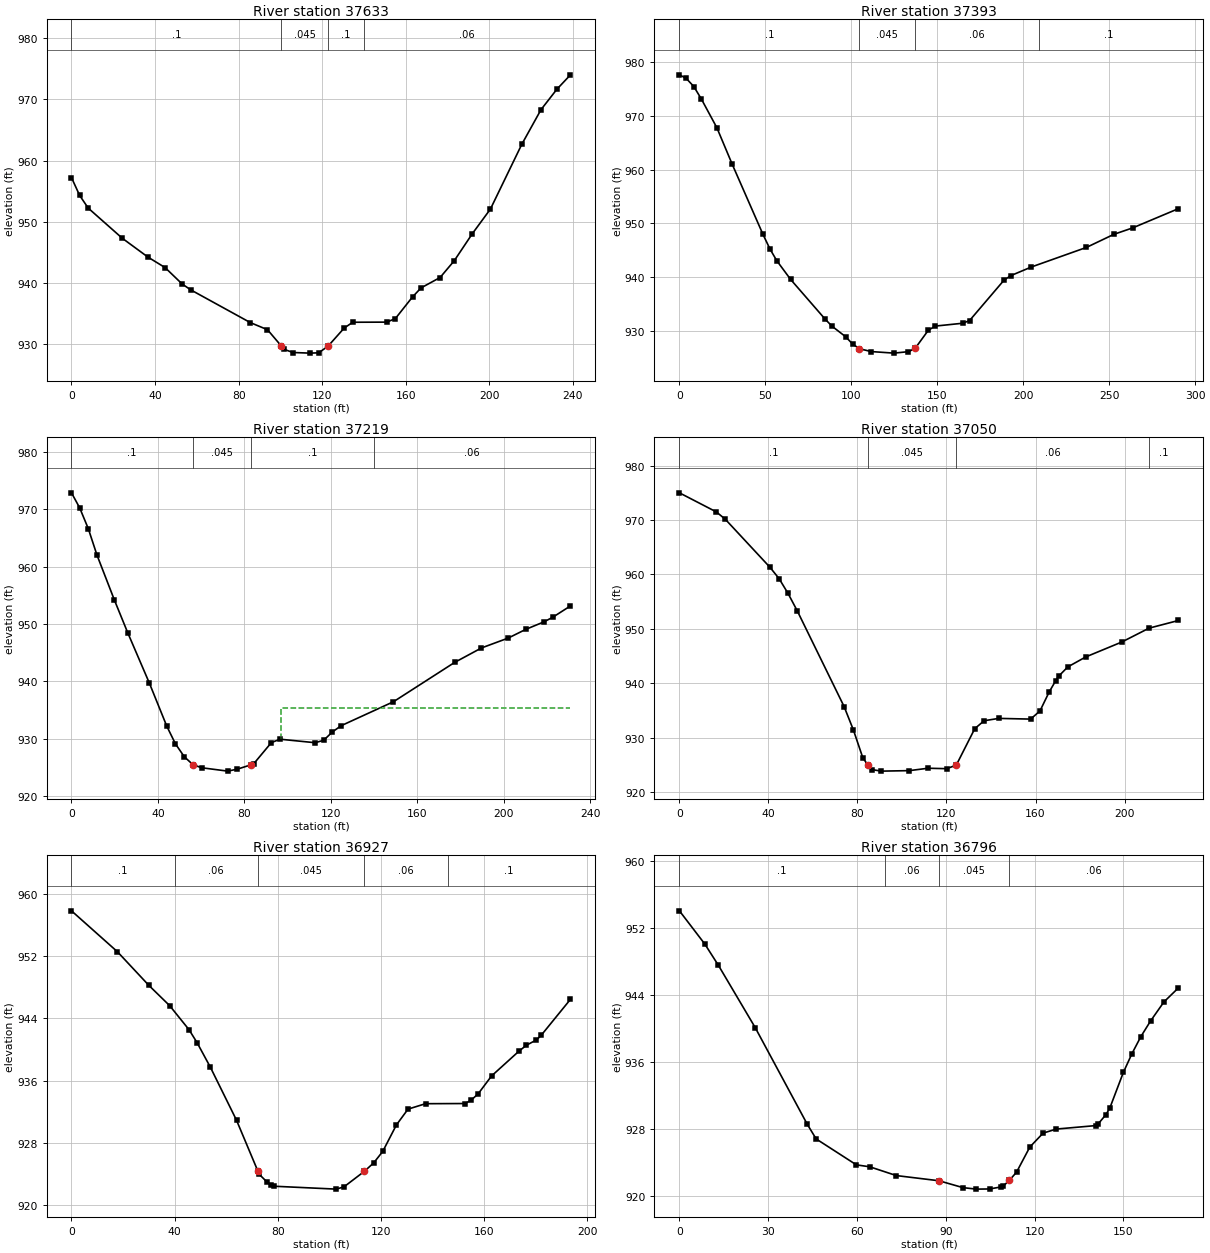
Type RM Length L Ch R = 1 ,37633   ,237.7,239.8,243.1
XS GIS Cut Line= 3
1614059.68338046429304.702023915 1614098.7243409429494.701364718
1614118.24482112429535.043690505
#Sta/Elev= 30
       0  957.22     3.9  954.32       8  952.25    24.3  947.33    36.6  944.25
    44.8  942.54    52.9  939.88      57  938.92    85.6  933.56    93.8   932.4
   100.4929.7535   101.9  929.18     106  928.68   114.2  928.58   118.3  928.63
   122.8929.7213   130.5  932.67   134.6  933.62   150.9  933.64     155  934.22
   163.2  937.75   167.3  939.23   176.4  940.92   183.2  943.67   191.8  948.06
   200.5   952.1   215.5  962.66   224.7  968.32   232.3  971.65   238.8     974
#Mann= 4, -1 ,  0
       0     0.1       0   100.4   0.045       0   122.8     0.1       0
     140    0.06       0
Bank Sta=100.4,122.8
XS Rating Curve= 0 ,0
Exp/Cntr(USF)=0,0
Exp/Cntr=0.3,0.1

Type RM Length L Ch R = 1 ,37393   ,174.7,173.6,171.7
XS GIS Cut Line= 4
1613822.83488713429345.0443497021613844.95809804429389.290771533
1613850.16355943429549.3587093331613851.46492478429630.043360907
#Sta/Elev= 30
       0  977.63     3.9  976.99     8.4  975.44    12.8  973.11    21.8  967.78
    30.7     961    48.6  947.95    52.7  945.21    56.7  943.02    64.7  939.56
    84.7   932.2    88.7  930.88    96.7   928.9   100.7  927.56   104.7  926.67
   111.6  926.14   124.8  925.85   133.2  926.12   137.1  926.72   144.8   930.1
   148.8  930.88   164.8  931.41   168.8  931.91   188.8  939.41   192.8  940.27
   204.8  941.88   236.8  945.52   252.8  947.96   263.7  949.15   290.3  952.73
#Mann= 4, -1 ,  0
       0     0.1       0   104.7   0.045       0   137.1    0.06       0
  209.47     0.1       0
Bank Sta=104.7,137.1
XS Rating Curve= 0 ,0
Exp/Cntr(USF)=0,0
Exp/Cntr=0.3,0.1

Type RM Length L Ch R = 1 ,37219   ,172,169.6,168.4
XS GIS Cut Line= 3
1613666.67104537429408.8112517521613688.79425629429579.290112336
1613703.10927511429636.550187647
#Sta/Elev= 30
       0   972.9     3.8  970.27     7.8  966.62    11.8  962.03    19.9  954.15
      26  948.51      36  939.73    44.1  932.18    48.1   929.1    52.2  926.85
    56.2  925.47    60.2  924.93    72.3  924.34    76.8  924.69    83.2  925.46
    84.4  925.66    92.5  929.32    96.5  929.91   112.7   929.3   116.7  929.72
   120.7  931.17   124.8  932.27     149  936.45   177.3  943.31   189.7  945.83
   202.1  947.56   210.3  949.09   218.6  950.38   222.7  951.19   230.9  953.17
#Mann= 4, -1 ,  0
       0     0.1       0    56.2   0.045       0    83.2     0.1       0
     140    0.06       0
#XS Ineff= 2 , 0
                           97.12          935.36
Permanent Ineff=
       F       F
Bank Sta=56.2,83.2
XS Rating Curve= 0 ,0
Exp/Cntr(USF)=0,0
Exp/Cntr=0.3,0.1

Type RM Length L Ch R = 1 ,37050   ,124.1,122.4,118.4
XS GIS Cut Line= 4
1613495.73691513429440.064243321 1613501.1160177429487.707723229
1613538.00129247 429605.279536551613547.22261116429657.533675804
#Sta/Elev= 30
       0  974.99    16.6  971.48    20.6  970.14    40.7   961.3    44.8  959.21
    48.8  956.51      53  953.26      74  935.71    78.2  931.38    82.4   926.3
    84.7  924.96    86.5  924.13    90.7  923.85   103.3  923.94   111.7  924.38
   120.1   924.3   124.4 924.954   132.7  931.65   136.9  933.11   143.5  933.54
   157.8  933.41     162  934.91   166.2  938.45   169.1  940.48   170.4   941.3
   174.5     943   182.6  944.84   198.8  947.58     211  950.12   224.2  951.53
#Mann= 4, -1 ,  0
       0     0.1       0    84.7   0.045       0   124.4    0.06       0
  211.17     0.1       0
Bank Sta=84.7,124.4
XS Rating Curve= 0 ,0
Exp/Cntr(USF)=0,0
Exp/Cntr=0.3,0.1

Type RM Length L Ch R = 1 ,36927   ,133,130.8,129.3
XS GIS Cut Line= 4
1613381.04097721429506.9887093271613388.72540945429552.241476982
1613434.83200291429648.7237929251613460.44677705429680.315347702
#Sta/Elev= 30
       0  957.83    17.8  952.57      30  948.24    38.1  945.62    45.6  942.53
    48.7  940.87    53.8  937.75      64  930.89    72.3  924.33    72.8  923.94
    75.7  922.98    77.3  922.51    78.7   922.4   102.7  922.03   105.7  922.33
   113.6924.3265   117.2  925.41   120.7  926.88     126  930.29   130.5  932.32
   137.3  933.02   152.6  933.04   154.9  933.45   157.7  934.29   162.9  936.59
   173.5  939.77   176.4  940.54   180.3  941.22   182.1   941.8   193.5  946.45
#Mann= 5, -1 ,  0
       0     0.1       0      40    0.06       0    72.3   0.045       0
   113.6    0.06       0   145.9     0.1       0
Bank Sta=72.3,113.6
XS Rating Curve= 0 ,0
Exp/Cntr(USF)=0,0
Exp/Cntr=0.3,0.1

Type RM Length L Ch R = 1 ,36796   ,288.4,284.5,278.8
XS GIS Cut Line= 4
1613251.01249425429581.9027576621613268.44078658429605.555440107
1613320.10322455429705.145681979 1613333.1744438429728.798364424
#Sta/Elev= 30
       0  954.06     8.6  950.08    13.2  947.53    25.6  940.11    43.2  928.55
    46.2   926.8    59.8   923.7    64.3  923.47    73.3  922.42    87.7   921.8
    95.8  920.98   100.3   920.8   104.8  920.82   108.5  921.05   109.3  921.13
   111.5  921.86   113.9  922.82   118.4  925.83   122.9   927.5   127.4  927.98
   140.9   928.4   141.6  928.64   144.1   929.7   145.4  930.47     150  934.75
   152.9  936.99   155.9  939.02   159.2   940.9   163.7  943.17   168.6  944.85
#Mann= 4, -1 ,  0
       0     0.1       0   69.38    0.06       0    87.7   0.045       0
   111.5    0.06       0
Bank Sta=87.7,111.5
XS Rating Curve= 0 ,0
Exp/Cntr(USF)=0,0
Exp/Cntr=0.3,0.1