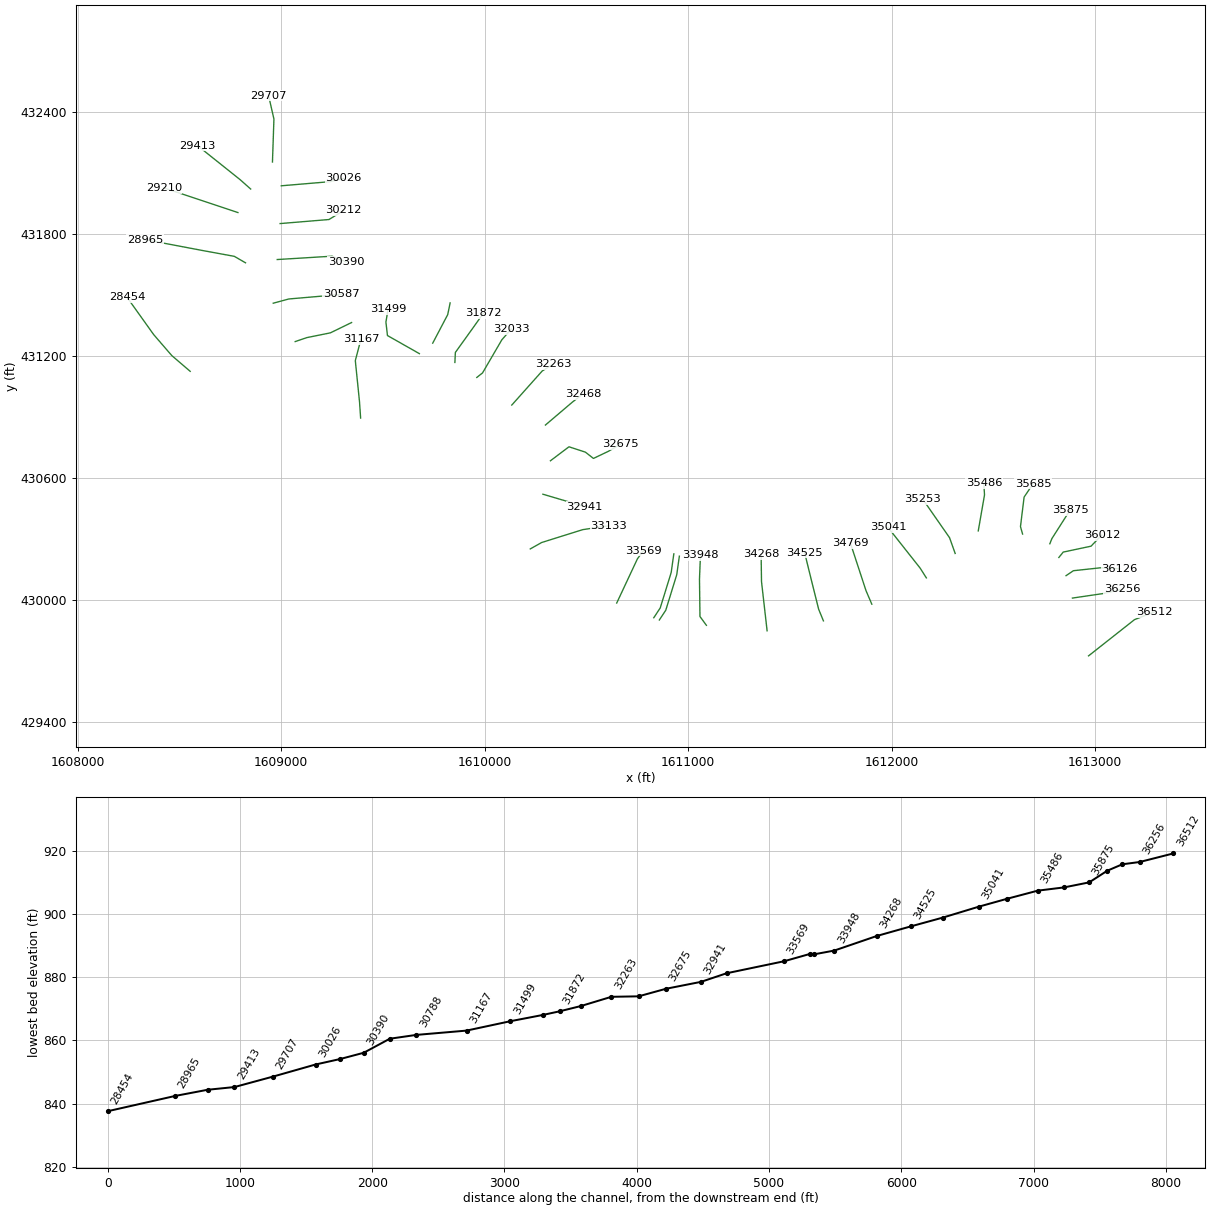
HEC-RAS study PROCTRCK.prj: PROCTRCK

--- PROCTRCK.g01 (geometry) --- (continued)

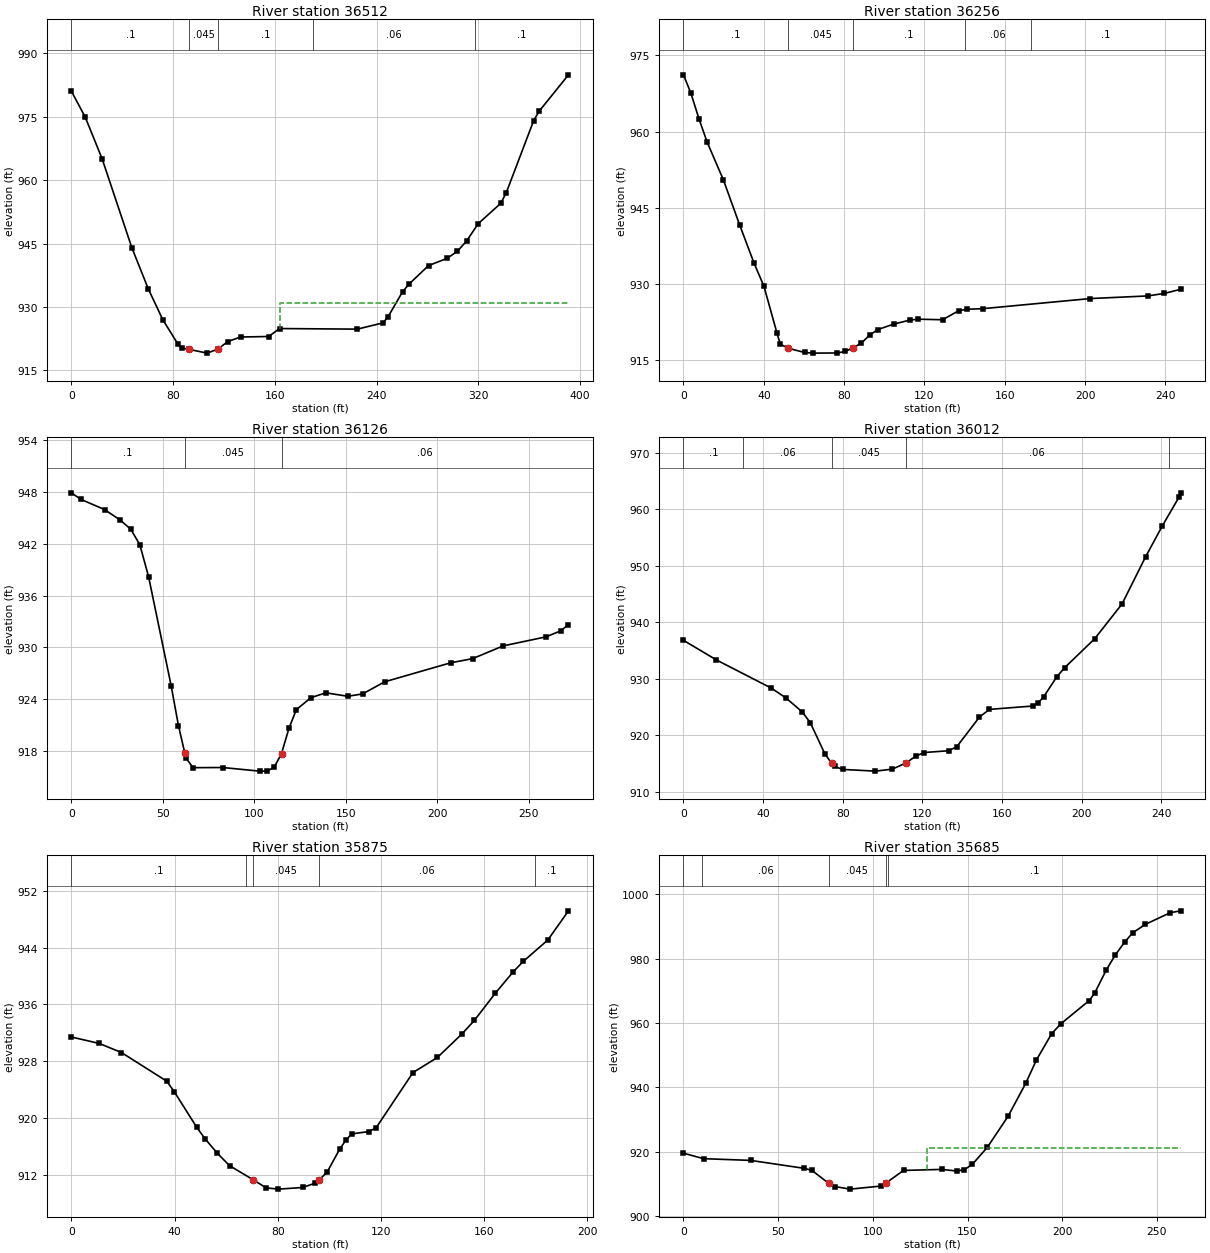
Type RM Length L Ch R = 1 ,36512   ,261.3,255.5,247.2
XS GIS Cut Line= 3
1612967.59587231 429723.100029591613193.51818026429901.378857632
 1613289.5735833429939.032575624
#Sta/Elev= 30
       0  981.02    10.9  974.87    24.2  965.01    47.5  944.06    60.4  934.33
      72  926.95      84  921.14    86.8  920.31    92.8 919.978   106.8   919.1
   115.3  920.06     123  921.84   133.1  922.91   155.2  923.03   163.7  924.91
   224.9  924.77   245.2  926.26   249.2  927.75   260.5  933.61   265.6  935.42
   280.9  939.79   295.3  941.47   303.5  943.13   310.8  945.59     320   949.7
   337.8  954.53   342.1  957.05   363.6  974.04   367.9  976.27     391  984.88
#Mann= 5, -1 ,  0
       0     0.1       0    92.8   0.045       0   115.3     0.1       0
     190    0.06       0  317.79     0.1       0
#XS Ineff= 2 , 0
                          164.15          930.98
Permanent Ineff=
       F       F
Bank Sta=92.8,115.3
XS Rating Curve= 0 ,0
Exp/Cntr(USF)=0,0
Exp/Cntr=0.3,0.1

Type RM Length L Ch R = 1 ,36256   ,132.1,130.8,130.2
XS GIS Cut Line= 3
 1612888.4462202430007.4240225891613039.82953539430029.708876094
1613132.04272231430050.456843151
#Sta/Elev= 30
       0  971.16     3.7  967.53     7.8   962.4    11.8   957.9    19.9  950.45
      28  941.58    35.1  934.14    40.1   929.5    46.5  920.39    48.2  918.15
    52.2  917.33    60.3  916.51    64.4  916.38    76.5  916.41    80.5  916.71
    84.6  917.44    88.6  918.37    92.7  919.92    96.7  921.01   104.8  922.11
   112.9   922.9   116.9  923.06     129  922.95   137.1  924.74   141.2  925.01
   149.3  925.14   202.5  927.12   231.2  927.64   239.4  928.13   247.5  928.94
#Mann= 5, -1 ,  0
       0     0.1       0    52.2   0.045       0    84.6     0.1       0
     140    0.06       0  173.01     0.1       0
Bank Sta=52.2,84.6
XS Rating Curve= 0 ,0
Exp/Cntr(USF)=0,0
Exp/Cntr=0.3,0.1

Type RM Length L Ch R = 1 ,36126   ,104.1,113.7,112.1
XS GIS Cut Line= 4
1612857.10588564430117.6580244291612893.20734832430141.933145886
 1613025.1644188430156.2492431551613120.39758759430151.269731061
#Sta/Elev= 30
       0  947.93     5.2  947.17    18.1  945.99    26.7  944.77    32.5  943.69
    37.4  941.91    42.2  938.18    54.5  925.57    58.5  920.93    61.9  917.81
    62.5   917.2    66.5  916.06    82.6  916.08   102.8  915.66   106.8  915.66
   110.8   916.1   114.8   917.7   118.9  920.64   122.9  922.79   130.9  924.18
     139  924.74     151  924.34   159.1  924.61   171.2  926.02   207.2  928.22
   219.2   928.7   235.9  930.18   259.3  931.23   267.3  931.92   271.6  932.64
#Mann= 3, -1 ,  0
       0     0.1       0    61.9   0.045       0   114.8    0.06       0
Bank Sta=61.9,114.8
XS Rating Curve= 0 ,0
Exp/Cntr(USF)=0,0
Exp/Cntr=0.3,0.1

Type RM Length L Ch R = 1 ,36012   ,126.2,136.9,152.2
XS GIS Cut Line= 4
1612821.73225572430207.0626293371612843.07790084430233.531229285
1612979.69002961430262.5613066491613032.62722951430317.206158156
#Sta/Elev= 30
       0  936.78    16.5  933.32    44.2  928.31    51.4   926.6    59.6  924.13
    63.7  922.21    71.1  916.63    74.5     915      76  914.45      80  913.93
    96.4  913.63   104.9  913.98   111.6  915.05   116.8   916.3   120.9  916.92
   133.2  917.24   137.3  917.95   148.7  923.21   153.7  924.56   175.4  925.15
   178.2  925.71     181  926.82   187.6  930.36   191.5  931.95   206.5  937.04
   220.3  943.22   232.1  951.54   240.4  956.95   248.9  962.11   249.7  962.89
#Mann= 5, -1 ,  0
       0     0.1       0      30    0.06       0    74.5   0.045       0
   111.6    0.06       0  243.67     0.1       0
Bank Sta=74.5,111.6
XS Rating Curve= 0 ,0
Exp/Cntr(USF)=0,0
Exp/Cntr=0.3,0.1

Type RM Length L Ch R = 1 ,35875   ,185.2,189.7,197.5
XS GIS Cut Line= 4
1612777.33331387430274.5148679161612787.57922353 430300.12964206
1612837.10112021430377.8277902971612876.37710723430439.303248243
#Sta/Elev= 30
       0  931.39    10.8  930.48    19.4   929.2      37  925.15    39.9  923.67
    48.5   918.7    51.8  917.05    56.5  915.03    61.3  913.25    70.5911.2521
    75.5  910.12    80.2  909.94    89.7  910.17    94.5  910.79    96.1911.2437
    99.2  912.38     104  915.58   106.5  916.89   108.7  917.73   115.2  918.05
   118.1  918.57   132.4  926.37   141.9  928.51   151.4  931.82   156.2  933.72
   164.4  937.59   171.3  940.59   175.2  942.06   184.7  945.07   192.7  949.18
#Mann= 5, -1 ,  0
       0     0.1       0   67.59    0.06       0    70.5   0.045       0
    96.1    0.06       0  179.73     0.1       0
Bank Sta=70.5,96.1
XS Rating Curve= 0 ,0
Exp/Cntr(USF)=0,0
Exp/Cntr=0.3,0.1

Type RM Length L Ch R = 1 ,35685   ,199.6,199.2,198.1
XS GIS Cut Line= 4
1612643.28266252430322.3291129851612633.03675286430359.043622591
1612650.96709476430504.194009408 1612694.5122108430569.084770573
#Sta/Elev= 30
       0  919.52    10.6  917.82    35.5  917.28    63.9   914.8    67.8  914.18
    76.8910.1055    79.9  909.16      88  908.35   104.1  909.29   106.8  910.19
   116.2  914.16   136.4  914.48   144.4  913.97   148.4  914.42   152.5  916.03
   160.5  921.37   171.4  930.98   180.7  941.21   186.4  948.52   194.4  956.65
   199.2  959.71   214.3  966.99   217.2  969.35   223.3  976.52   228.1   981.2
     233  985.17   237.3  988.06   243.9  990.66     257  994.27   262.5  994.87
#Mann= 5, -1 ,  0
       0     0.1       0      10    0.06       0    76.8   0.045       0
   106.8    0.06       0  108.12     0.1       0
#XS Ineff= 2 , 0
                          128.37          921.11
Permanent Ineff=
       F       F
Bank Sta=76.8,106.8
XS Rating Curve= 0 ,0
Exp/Cntr(USF)=0,0
Exp/Cntr=0.3,0.1

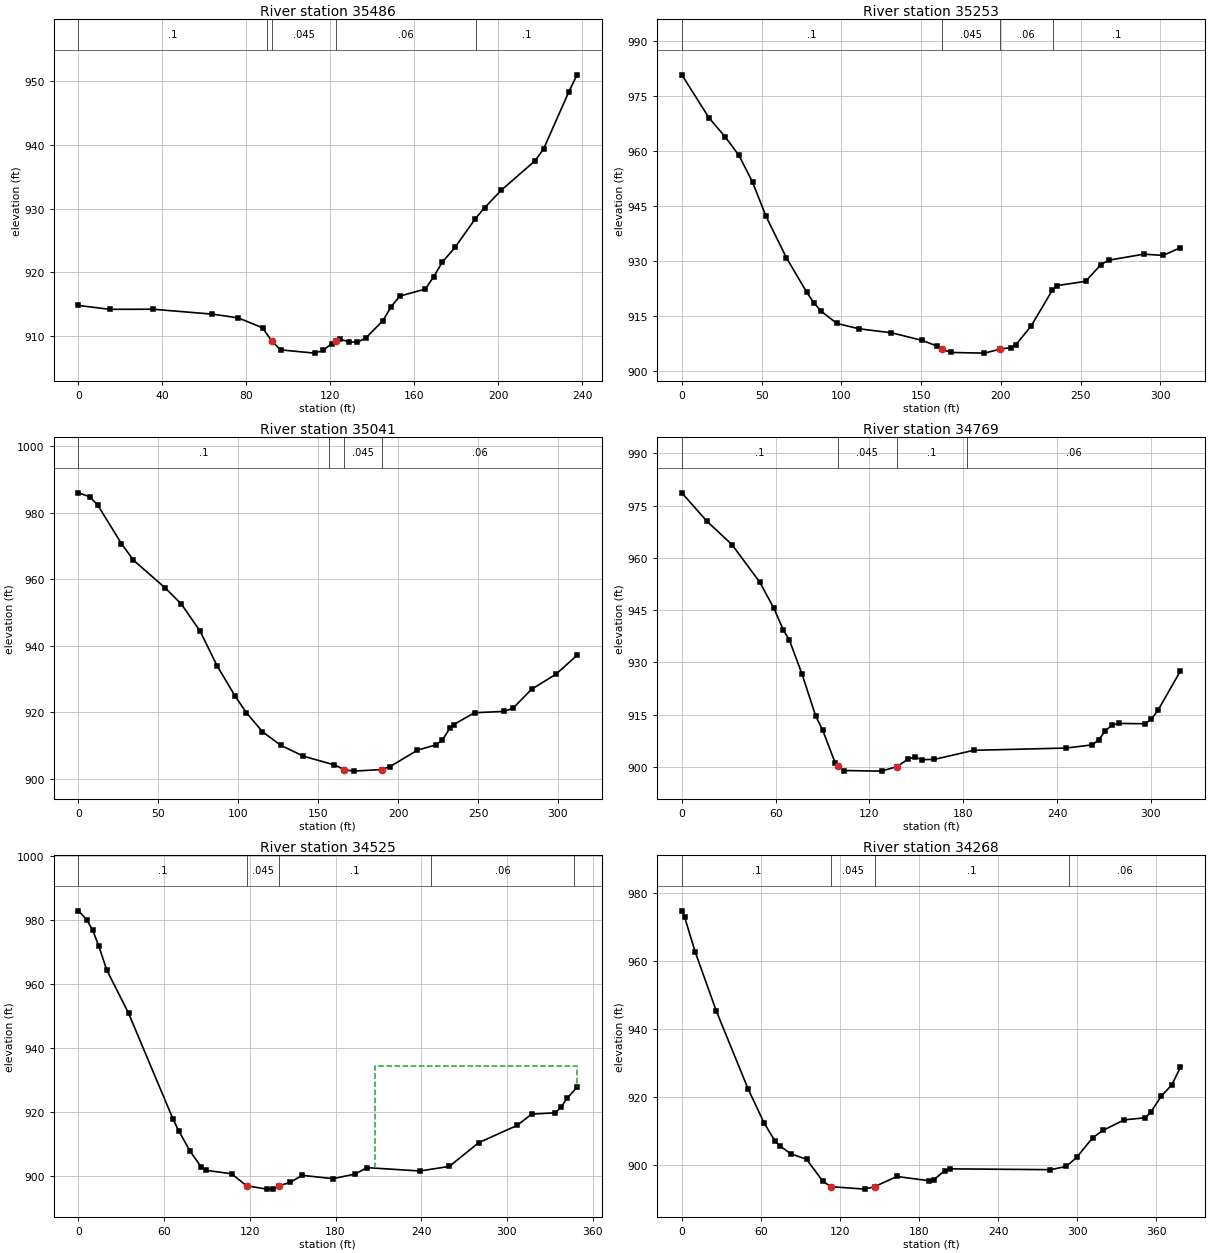
Type RM Length L Ch R = 1 ,35486   ,220.6,233,246
XS GIS Cut Line= 3
1612425.55708229430337.6979774711612456.29481127430514.439919066
1612452.87950805430572.500073792
#Sta/Elev= 30
       0   914.8      15  914.19    35.4  914.21    63.8  913.44      76  912.86
    87.7   911.3    92.2  909.18    96.3  907.83   112.5  907.32   116.6  907.74
   120.6  908.79   122.8 909.171   124.7   909.5   128.7   909.1   132.8  909.01
   136.9  909.69     145  912.39     149   914.6   153.1  916.27   165.3  917.37
   169.3  919.34   173.4  921.61   179.4   923.9   189.1  928.41   193.5  930.13
   201.5  932.89   217.6  937.52   221.6  939.34   233.6  948.29   237.6  950.99
#Mann= 5, -1 ,  0
       0     0.1       0      90    0.06       0    92.2   0.045       0
   122.8    0.06       0  189.39     0.1       0
Bank Sta=92.2,122.8
XS Rating Curve= 0 ,0
Exp/Cntr(USF)=0,0
Exp/Cntr=0.3,0.1

Type RM Length L Ch R = 1 ,35253   ,211.2,212.2,213.8
XS GIS Cut Line= 3
1612312.10273225 430226.786305461612284.43877617430304.399071116
1612153.03498481430493.436104299
#Sta/Elev= 30
       0  980.65      17  968.92    27.3  963.64    35.8  958.67    44.3   951.4
    52.8  942.02    65.6  930.71    78.3  921.34    82.6  918.54    87.4  916.15
    97.2  912.84     111  911.38   131.3   910.3   150.8   908.2   160.1  906.65
   163.2  905.73   168.9  904.92   189.7  904.74   199.5  905.83   206.3  906.26
   209.2  906.91     219  912.16   232.2  921.86     235  923.14   253.1  924.33
   262.8  928.91   267.7   930.1   289.6  931.73   301.8   931.4   312.6  933.51
#Mann= 4, -1 ,  0
       0     0.1       0   163.2   0.045       0   199.5    0.06       0
   232.4     0.1       0
Bank Sta=163.2,199.5
XS Rating Curve= 0 ,0
Exp/Cntr(USF)=0,0
Exp/Cntr=0.3,0.1

Type RM Length L Ch R = 1 ,35041   ,278.4,271.6,264.9
XS GIS Cut Line= 3
1612170.51569197430106.6223285291612140.06374283430154.642709869
1611981.94785305430354.922836921
#Sta/Elev= 30
       0  986.04       7  984.86      12  982.37    26.9  970.74    34.4  965.77
    54.4  957.34    64.4  952.54    76.1  944.39    86.7     934      98  924.85
   105.1  919.83   115.1  914.13   126.5  910.06   140.8  906.75   160.1  904.14
   166.4  902.69   172.1  902.26   189.7  902.74   194.9   903.6     212  908.55
   223.4  910.13   227.5  911.51   232.5  915.25   234.7  916.25   247.8  919.84
   266.1  920.24   271.8  921.14   283.5   926.9   298.8  931.45     312  937.15
#Mann= 4, -1 ,  0
       0     0.1       0  156.86    0.06       0   166.4   0.045       0
   189.7    0.06       0
Bank Sta=166.4,189.7
XS Rating Curve= 0 ,0
Exp/Cntr(USF)=0,0
Exp/Cntr=0.3,0.1

Type RM Length L Ch R = 1 ,34769   ,246,244.7,244
XS GIS Cut Line= 3
1611902.38309866429977.434778263 1611873.9222385 430043.84345197
1611797.07791607430278.171200621
#Sta/Elev= 30
       0  978.66    15.9  970.56    32.1  963.78    49.8  953.04    58.9  945.52
      65  939.21    68.7   936.5    76.8  926.73    85.6  914.63    90.1  910.52
    98.2  901.03    99.6  900.21   103.7  898.98   127.7  898.81   137.6  900.12
   144.5   902.2   148.8  902.87   153.5  902.11   161.4  902.17   186.6  904.78
   245.6  905.43   262.4  906.34   266.6  907.76   270.8  910.39     275  911.98
   279.3   912.5   296.1   912.4   300.3  913.73   304.5  916.28   318.9  927.58
#Mann= 4, -1 ,  0
       0     0.1       0    99.6   0.045       0   137.6     0.1       0
  182.25    0.06       0
Bank Sta=99.6,137.6
XS Rating Curve= 0 ,0
Exp/Cntr(USF)=0,0
Exp/Cntr=0.3,0.1

Type RM Length L Ch R = 1 ,34525   ,257.8,256.4,254.2
XS GIS Cut Line= 4
1611664.60117893429895.2788054811611641.17660267429952.669017327
1611606.03973827430093.2164749081611572.07410269430231.421474862
#Sta/Elev= 30
       0   982.9     5.7  980.17      10  976.83    14.3  971.82    19.7  964.53
    35.1  950.89    66.1     918    70.1  914.26    78.3  907.76    85.8     903
    89.1  901.89   107.2  900.79   117.7897.0433   131.9     896   136.1  896.06
   140.2  896.99   148.4  898.15   156.7  900.31   178.2  899.26   193.8  900.72
     202  902.71   239.1  901.66   259.7  903.09   280.3   910.5   307.1  915.88
   317.4  919.43   333.9  919.82     338  921.59   342.1  924.35   349.2  927.82
#Mann= 5, -1 ,  0
       0     0.1       0   117.7   0.045       0   140.2     0.1       0
  246.86    0.06       0  346.86     0.1       0
#XS Ineff= 2 , 0
                          207.58           934.5
Permanent Ineff=
       F       F
Bank Sta=117.7,140.2
XS Rating Curve= 0 ,0
Exp/Cntr(USF)=0,0
Exp/Cntr=0.3,0.1

Type RM Length L Ch R = 1 ,34268   ,321.6,320.5,318.2
XS GIS Cut Line= 3
1611387.85152267429846.4971254131611360.33935785430088.414436774
1611358.44196717430223.129174865
#Sta/Elev= 30
       0  974.64     2.1  972.81    10.1  962.59    26.2  945.17    50.4  922.25
    62.4  912.38    70.5  907.16    74.5   905.6    82.6  903.36    94.6  901.72
   106.7  895.41   112.9893.6852   138.9  892.97   146.2   893.7   163.1  896.68
   187.2  895.45   191.3  895.78   199.3  898.38   203.3  898.92   279.6  898.68
   291.6  899.62   299.6  902.36   311.6  908.05   319.6  910.25   335.6   913.3
   351.6  913.92   355.6   915.5   363.6  920.24   371.6  923.56   378.2  928.75
#Mann= 4, -1 ,  0
       0     0.1       0   112.9   0.045       0   146.2     0.1       0
  293.48    0.06       0
Bank Sta=112.9,146.2
XS Rating Curve= 0 ,0
Exp/Cntr(USF)=0,0
Exp/Cntr=0.3,0.1

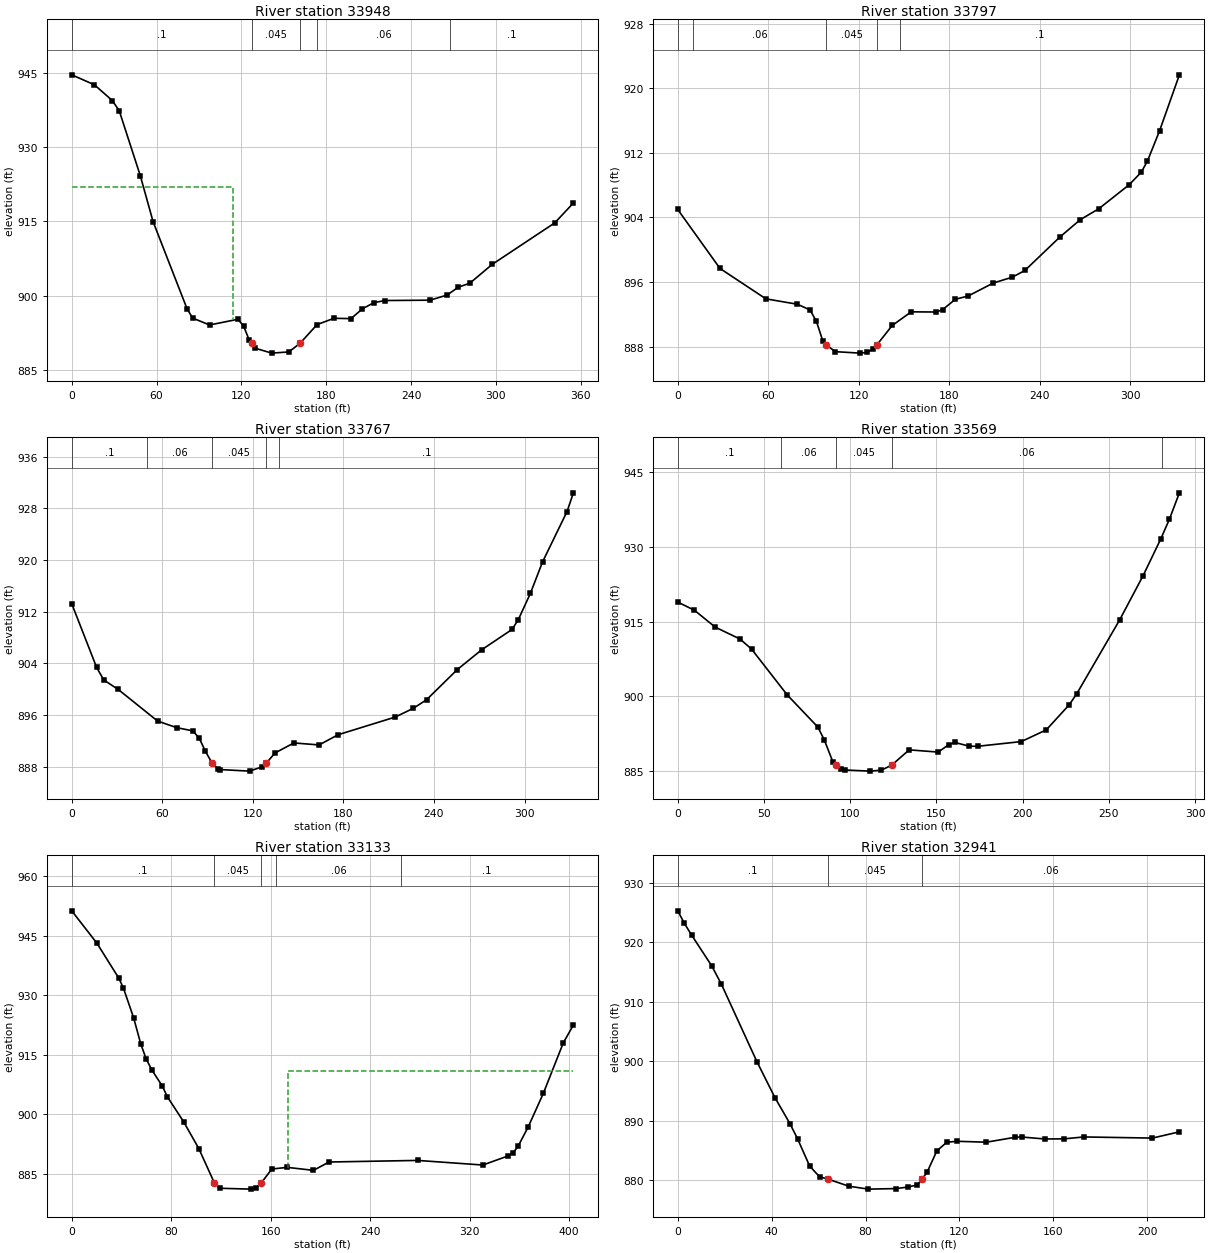
Type RM Length L Ch R = 1 ,33948   ,155.3,150.6,145
XS GIS Cut Line= 4
1611089.53892219429873.3750481421611057.91574423 429916.71051423
1611055.57328661430100.5934378981611060.25820186430217.716319215
#Sta/Elev= 30
       0  944.61      16   942.6    28.7  939.41    33.6  937.34    48.5  924.21
    57.5  914.96    81.5  897.36    85.5  895.45    97.5  894.06   117.5  895.21
   121.5  893.86   125.5  891.03   127.2890.3288   129.5  889.38   141.5  888.37
   153.5  888.61   161.5  890.36   173.5  894.14   185.5  895.41   197.5  895.34
   205.5  897.31   213.7  898.57   221.5     899   253.4  899.07   265.5  900.11
   273.5  901.71   281.5  902.49   297.5  906.33   341.6  914.69   354.8  918.71
#Mann= 5, -1 ,  0
       0     0.1       0   127.2   0.045       0   161.5     0.1       0
  173.65    0.06       0  267.54     0.1       0
#XS Ineff= 2 , 0
          113.87  921.94
Permanent Ineff=
       F       F
Bank Sta=127.2,161.5
XS Rating Curve= 0 ,0
Exp/Cntr(USF)=0,0
Exp/Cntr=0.3,0.1

Type RM Length L Ch R = 1 ,33797   ,29.4,30,29.4
XS GIS Cut Line= 4
1610858.24342516429899.6516409461610889.86660312429947.672022286
1610943.74312852430122.1851154491610956.62664547430213.540962876
#Sta/Elev= 30
       0  904.98      28  897.68    58.4  893.92    79.3  893.25    87.7  892.54
    91.9  891.12    96.1  888.72    98.4   888.2   104.5  887.38   120.8   887.2
   125.4  887.29   129.6   887.7  131.91  888.21   142.1  890.62   154.7  892.31
   171.4  892.29   175.6   892.6     184  893.87   192.4  894.27   209.1  895.88
   221.7   896.6     230  897.43   253.2  901.57   266.8  903.73   278.9  905.06
   299.1  908.04   307.1  909.59   311.2  910.96   319.3  914.74   332.4  921.65
#Mann= 5, -1 ,  0
       0     0.1       0      10    0.06       0    98.4   0.045       0
  131.91    0.06       0   147.5     0.1       0
Bank Sta=98.4,131.91
XS Rating Curve= 0 ,0
Exp/Cntr(USF)=0,0
Exp/Cntr=0.3,0.1

Type RM Length L Ch R = 1 ,33767   ,199.5,198,194.8
XS GIS Cut Line= 4
1610831.02040111429910.8331687761610862.64357907429958.853550116
1610916.52010447430133.3666432791610929.40362142430224.722490706
#Sta/Elev= 30
       0  913.24    16.5  903.38    21.2  901.45    30.8  899.98    56.9  895.09
    69.6  894.07    80.2  893.58    84.4  892.48    88.6   890.4   93.09  888.55
    96.9  887.69    98.4  887.59   117.9  887.35   126.2  888.03   128.8 888.535
   134.6  890.15   147.2  891.71   163.9   891.4   176.5  892.98   214.2   895.7
   226.4  897.07   235.1  898.39   255.5  903.06   271.6  906.11   291.8  909.27
   295.9  910.78   303.9  914.84     312  919.73   328.2   927.5   332.4  930.39
#Mann= 5, -1 ,  0
       0     0.1       0      50    0.06       0   93.09   0.045       0
   128.8    0.06       0   137.5     0.1       0
Bank Sta=93.09,128.8
XS Rating Curve= 0 ,0
Exp/Cntr(USF)=0,0
Exp/Cntr=0.3,0.1

Type RM Length L Ch R = 1 ,33569   ,452.1,435.9,421.6
XS GIS Cut Line= 3
1610648.78713604429983.0006099281610750.99008488430201.238485635
1610780.95937062  430241.1975333
#Sta/Elev= 30
       0  918.94     9.7  917.29    21.7  913.91    36.1  911.52    42.8   909.5
    63.5  900.29    81.2  893.86    84.9  891.34      90  886.82    91.6886.2106
    94.5   885.4    96.9  885.23   111.6     885     118  885.19  124.06  886.19
   134.2  889.27   151.1  888.82   157.1  890.32   160.7  890.75   169.1     890
     174  889.99   199.2  890.93   213.7  893.28     227  898.31   231.4  900.54
   256.2  915.32   269.9  924.27   280.1  931.61   285.1  935.56   290.9  940.87
#Mann= 5, -1 ,  0
       0     0.1       0      60    0.06       0    91.6   0.045       0
  124.06    0.06       0  280.98     0.1       0
Bank Sta=91.6,124.06
XS Rating Curve= 0 ,0
Exp/Cntr(USF)=0,0
Exp/Cntr=0.3,0.1

Type RM Length L Ch R = 1 ,33133   ,206.2,192.5,183.8
XS GIS Cut Line= 4
1610223.90884506430249.1510509541610280.26134817430280.742605731
1610481.76423811430343.9257152871610608.13045722430362.709882993
#Sta/Elev= 30
       0  951.29    20.3  943.11    37.9   934.3    41.5  931.88    49.7  924.42
    55.5  917.78    59.8  914.02    64.4  911.22    72.8  907.17      77   904.4
    89.9  898.21   102.2  891.41   114.8   882.7   118.9  881.41   144.1  881.19
   148.3  881.55   152.5  882.77   160.9  886.25   173.4  886.67   194.4  885.92
     207  888.02   278.2  888.42   330.7  887.26   350.9  889.55     355  890.35
     359  891.98   367.1  896.83   379.3   905.3   395.4  918.06   403.5  922.52
#Mann= 5, -1 ,  0
       0     0.1       0   114.8   0.045       0   152.5     0.1       0
   164.6    0.06       0   264.6     0.1       0
#XS Ineff= 2 , 0
                          174.34          910.89
Permanent Ineff=
       F       F
Bank Sta=114.8,152.5
XS Rating Curve= 0 ,0
Exp/Cntr(USF)=0,0
Exp/Cntr=0.3,0.1

Type RM Length L Ch R = 1 ,32941   ,267.1,265.2,264
XS GIS Cut Line= 2
1610286.23812881430518.1061794671610491.15632196430457.484547326
#Sta/Elev= 30
       0  925.31     2.8  923.22       6  921.17    14.5  916.03    18.6  912.96
    33.7  899.95    41.4  893.88    47.8   889.5    51.1   886.9    56.2  882.36
    60.4  880.56    63.9  880.18    72.9  878.97    81.2  878.48    92.9  878.57
    97.9  878.82   102.1  879.19   104.2  880.24   106.2  881.31   110.4  884.93
   114.6  886.36   118.8  886.53   131.5  886.38   143.8  887.21   146.5  887.25
   156.3  886.92   164.6  886.94     173  887.26   202.2  887.07   213.7  888.12
#Mann= 3, -1 ,  0
       0     0.1       0    63.9   0.045       0   104.2    0.06       0
Bank Sta=63.9,104.2
XS Rating Curve= 0 ,0
Exp/Cntr(USF)=0,0
Exp/Cntr=0.3,0.1

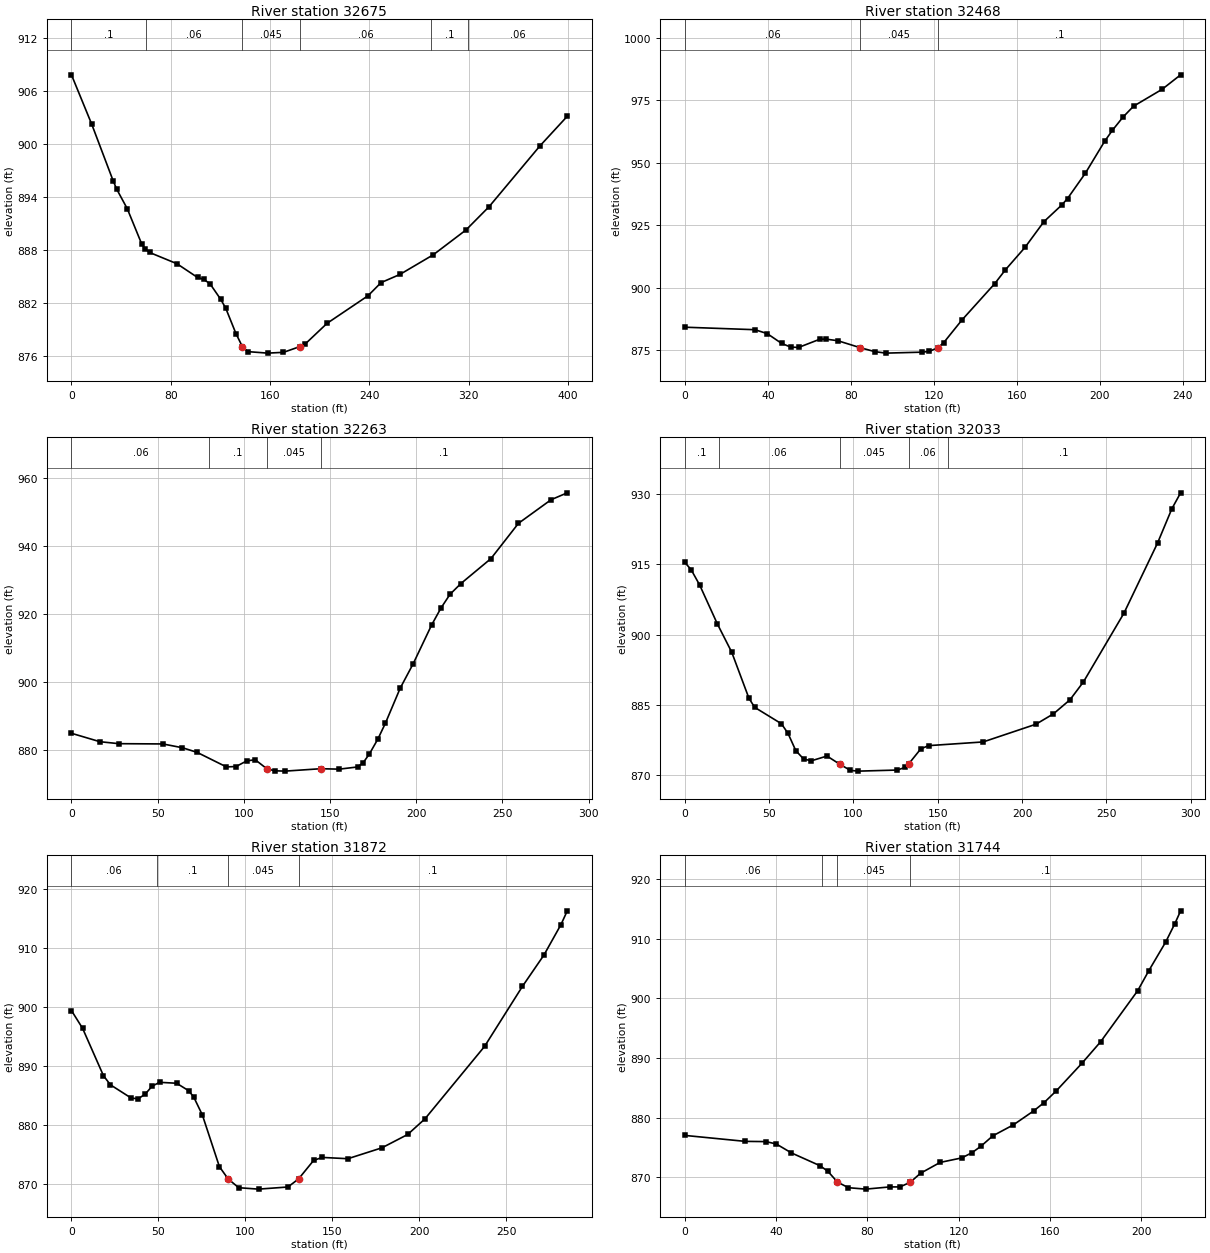
Type RM Length L Ch R = 1 ,32675   ,186.5,207.1,230.9
XS GIS Cut Line= 6
1610323.03338881430682.6346492011610414.12576609430751.386828572
1610494.87817483430725.0023781921610534.38177495430694.138908143
1610608.33883794430729.4172511671610667.25281847430763.570283359
#Sta/Elev= 30
       0  907.86    16.4  902.23    33.5  895.87    36.4   894.9      45  892.66
    56.5   888.7    59.2  888.15    62.9  887.71      85  886.43   101.6  884.87
   106.6  884.65   111.6  884.16   120.2   882.4   124.3  881.38   132.5  878.51
  137.63  877.04   142.1  876.46     158  876.29   170.8  876.38   184.2877.0409
   188.1   877.3   205.9  879.67   238.9   882.8   249.4  884.29   264.5  885.21
   291.5  887.45   317.8  890.26   336.4   892.9   377.4   899.8   399.4  903.16
#Mann= 6, -1 ,  0
       0     0.1       0      60    0.06       0  137.63   0.045       0
   184.2    0.06       0  289.37     0.1       0  319.37    0.06       0
Bank Sta=137.63,184.2
XS Rating Curve= 0 ,0
Exp/Cntr(USF)=0,0
Exp/Cntr=0.3,0.1

Type RM Length L Ch R = 1 ,32468   ,202,205.3,207.3
XS GIS Cut Line= 3
 1610298.4000708430858.3449476931610429.88924474430970.196128122
1610481.97261883431011.179766752
#Sta/Elev= 30
       0  884.27    33.8  883.27    39.7  881.71    46.6  877.81      51  876.32
    54.8  876.17    65.1  879.48      68   879.5    73.7  878.87    84.6876.0522
    91.5  874.51    96.8   873.9   114.5  874.29   117.8  874.61     122  876.08
   124.8  878.15   133.5  887.12   149.3  901.66   154.5  907.25   163.9  916.18
     173  926.46   181.6  933.13   184.4  935.73     193  945.87   202.3  958.65
     206     963   211.1  968.28   216.2  972.66     230  979.44   238.9  985.22
#Mann= 3, -1 ,  0
       0    0.06       0    84.6   0.045       0     122     0.1       0
Bank Sta=84.6,122
XS Rating Curve= 0 ,0
Exp/Cntr(USF)=0,0
Exp/Cntr=0.3,0.1

Type RM Length L Ch R = 1 ,32263   ,227.5,230,234.1
XS GIS Cut Line= 3
1610133.12999568430956.6469503081610282.51535849431124.083044456
 1610336.0451135431157.694751088
#Sta/Elev= 30
       0  884.89    16.5  882.41    27.5  881.83      53  881.75    64.4  880.63
    72.9  879.27    89.9  874.99    95.5  875.11   101.7  876.77   106.6   877.1
   113.3874.4548   117.8  873.85   123.9  873.75   144.6  874.46   155.3  874.33
     166  874.98   169.2  876.22   172.7  878.71   177.7  883.15   182.1  887.85
   190.7  898.18   198.2  905.33   208.9  916.75   214.3  921.72   219.6   925.8
   225.9  928.96   243.3  936.29   259.3  946.69   278.2  953.63   287.6  955.66
#Mann= 4, -1 ,  0
       0    0.06       0      80     0.1       0   113.3   0.045       0
   144.6     0.1       0
Bank Sta=113.3,144.6
XS Rating Curve= 0 ,0
Exp/Cntr(USF)=0,0
Exp/Cntr=0.3,0.1

Type RM Length L Ch R = 1 ,32033   ,162.3,160.6,158.5
XS GIS Cut Line= 4
1609961.21124579431092.387431855 1609989.3207373431114.640779305
1610084.19027117431277.4415843361610129.86819488431330.146880929
#Sta/Elev= 30
       0  915.38     3.7  913.87     8.8  910.57    19.3  902.26    27.8  896.24
      38  886.42    41.4  884.46    57.3  880.95    61.2  878.89    65.8  875.22
    70.5  873.41    75.1  873.05    84.3  874.06    91.9  872.31    98.2  870.99
   102.9  870.84     126  871.07   130.6  871.64   132.9  872.45   139.9  875.58
   144.5  876.28   176.9  877.07   208.2  880.85   218.6  883.07   228.4  886.07
   236.4   889.9   260.4  904.56   280.3  919.51   288.8  926.84     294  930.24
#Mann= 5, -1 ,  0
       0     0.1       0      20    0.06       0    91.9   0.045       0
   132.9    0.06       0  155.85     0.1       0
Bank Sta=91.9,132.9
XS Rating Curve= 0 ,0
Exp/Cntr(USF)=0,0
Exp/Cntr=0.3,0.1

Type RM Length L Ch R = 1 ,31872   ,126.5,128,131.2
XS GIS Cut Line= 4
1609853.45819498431166.174847085 1609855.8006526431215.366457238
1609950.67018647431347.7153131271609992.83442374431407.447982599
#Sta/Elev= 30
       0  899.46     6.4  896.45    18.4  888.42    22.4  886.87    34.4  884.61
    38.4   884.5    42.4  885.28    46.4  886.64    50.7  887.29    60.5  887.13
    67.5  885.85    70.4  884.75    75.3  881.75    85.1  872.98    90.1  870.91
    96.2  869.41   107.6  869.17   124.5  869.53   130.6  870.89   139.3  874.04
   144.2  874.55     159  874.33   178.6  876.18   193.4  878.44   203.3  881.08
   237.6  893.37   259.4  903.56   271.8  908.89   281.6  914.06   285.2  916.38
#Mann= 4, -1 ,  0
       0    0.06       0   49.25     0.1       0    90.1   0.045       0
   130.6     0.1       0
Bank Sta=90.1,130.6
XS Rating Curve= 0 ,0
Exp/Cntr(USF)=0,0
Exp/Cntr=0.3,0.1

Type RM Length L Ch R = 1 ,31744   ,230.8,245.4,281.8
XS GIS Cut Line= 3
1609744.53391535431261.0443809521609818.32133058431401.591838533
1609830.03361871431458.982050378
#Sta/Elev= 30
       0  877.02    26.5  876.02    35.6  875.98    40.1  875.58    46.7  874.09
    59.3  871.93    62.7     871    66.9869.1945    71.7  868.25    79.3  868.01
    89.8  868.38    94.3  868.38    98.8  869.16   103.3  870.67   111.9  872.49
   121.4  873.25   125.9  874.13   129.7  875.18     135  876.95     144  878.79
     153  881.16   157.5  882.54   162.8  884.49     174   889.1   182.2  892.71
   198.5   901.3   203.4  904.68   210.7  909.42   214.8  912.56   217.3  914.69
#Mann= 4, -1 ,  0
       0    0.06       0      60     0.1       0    66.9   0.045       0
    98.8     0.1       0
Bank Sta=66.9,98.8
XS Rating Curve= 0 ,0
Exp/Cntr(USF)=0,0
Exp/Cntr=0.3,0.1

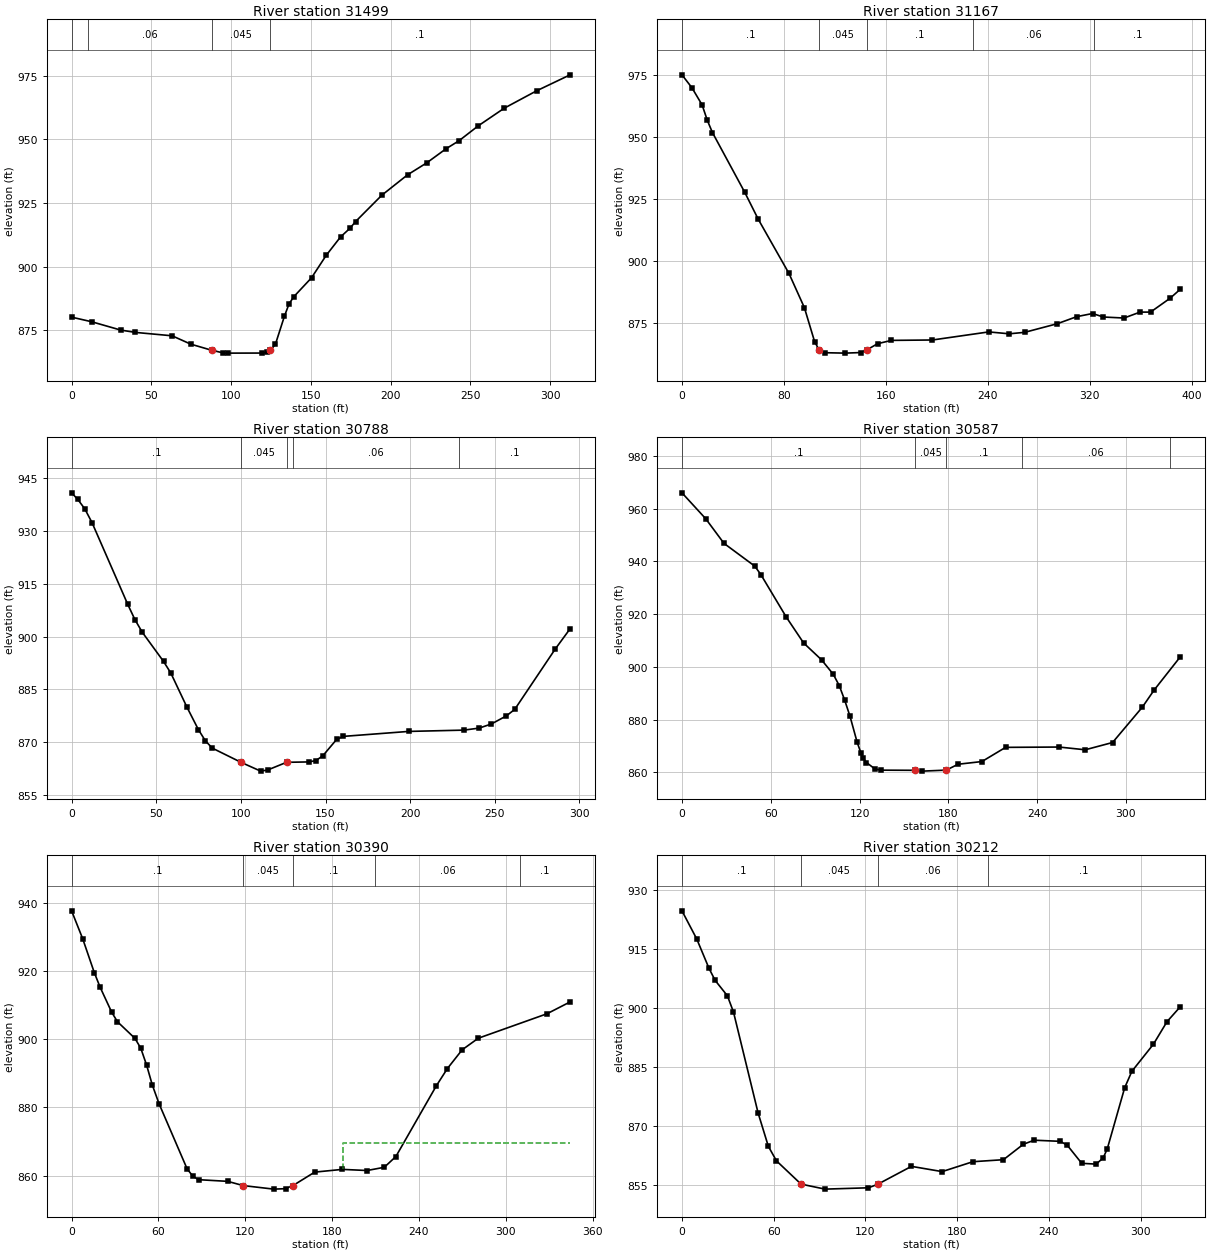
Type RM Length L Ch R = 1 ,31499   ,345.1,331.5,308.6
XS GIS Cut Line= 4
1609678.94510181431209.5103131721609522.00044085431298.523702973
1609514.51779977431364.7183926661609525.27600491 431429.26762351
#Sta/Elev= 30
       0  880.16    12.5  878.37    30.7   875.1      40  874.17      63  872.84
    74.7  869.56    87.8867.1624    95.2   866.1    98.2  866.03   119.6  866.06
   122.8  866.39   124.6  867.09   127.8  869.57   133.4   880.5   136.3  885.37
   139.3   888.2   150.4  895.62   159.6  904.44   168.6  911.68   174.5  915.07
     178   917.7   194.5  928.08   210.6  936.07   222.7   940.8   234.8  946.34
   242.8  949.43     255  955.35   271.2  962.24   291.5  969.07   312.5  975.35
#Mann= 4, -1 ,  0
       0     0.1       0      10    0.06       0    87.8   0.045       0
   124.6     0.1       0
Bank Sta=87.8,124.6
XS Rating Curve= 0 ,0
Exp/Cntr(USF)=0,0
Exp/Cntr=0.3,0.1

Type RM Length L Ch R = 1 ,31167   ,398.7,379.6,346.8
XS GIS Cut Line= 4
 1609390.1260885430892.7263349081609384.92062711430970.808255787
1609364.09878154431175.1226154181609391.42745385431279.231843256
#Sta/Elev= 30
       0   975.1     7.8  969.91    15.8     963    19.9  956.77    23.9  951.88
    49.2  927.88    59.9  916.93      84  895.13    96.1  881.35   104.1   867.7
   107.5864.4785   112.2  863.23     128  863.06   140.3  863.29   145.3864.4175
   153.5  866.85   164.4  868.19   196.6  868.35   240.8   871.6   256.9  870.84
     269  871.43   294.6   874.9   309.9  877.75   322.3  879.01   330.7   877.6
     347  877.19   359.5  879.57   367.8  879.58   383.1  885.14   391.3  888.84
#Mann= 5, -1 ,  0
       0     0.1       0   107.5   0.045       0   145.3     0.1       0
  228.26    0.06       0  323.63     0.1       0
Bank Sta=107.5,145.3
XS Rating Curve= 0 ,0
Exp/Cntr(USF)=0,0
Exp/Cntr=0.3,0.1

Type RM Length L Ch R = 1 ,30788   ,200.7,200.4,198.5
XS GIS Cut Line= 4
1609068.68884755431268.8209204721609125.94892286431288.341400692
1609241.77043883431311.7659769551609345.87966667431362.519225526
#Sta/Elev= 30
       0   940.9     3.6  939.06     7.8  936.34    12.1  932.39    33.2  909.13
    37.4  904.83    41.7  901.26    54.3  892.93    58.6  889.63    68.1  879.95
    74.9  873.52      79  870.35    83.1  868.25   100.3  864.16   111.7   861.7
   115.8  862.02     127  864.21   140.2  864.32   144.3   864.7   148.4  866.06
   156.6  870.74   160.6  871.59   199.1     873   231.8  873.37   240.8  873.95
     248  875.12   256.9  877.44   261.8  879.28   285.7  896.44   294.5  902.22
#Mann= 5, -1 ,  0
       0     0.1       0   100.3   0.045       0     127     0.1       0
   130.5    0.06       0  228.66     0.1       0
Bank Sta=100.3,127
XS Rating Curve= 0 ,0
Exp/Cntr(USF)=0,0
Exp/Cntr=0.3,0.1

Type RM Length L Ch R = 1 ,30587   ,197,197.1,196.3
XS GIS Cut Line= 3
1608960.67552367431457.518895928 1609037.4560792431478.340741496
1609293.82505275431500.463952411
#Sta/Elev= 30
       0  965.99      16   956.2    28.4  946.83    49.2   938.2    53.3  935.01
    70.5  918.88    82.2  909.08    94.3   902.7   102.3  897.17   106.3  892.89
   109.9   887.5   113.6  881.21   118.4   871.4     121   867.3   122.4  865.42
   124.7  863.74   130.4  861.32   134.4  860.86   157.7 860.796   162.5  860.49
   178.6  860.87   186.6   863.1   202.7  864.12   218.7   869.5   254.9  869.62
   272.5  868.58     291  871.34   311.1  884.73   319.1  891.24   336.9  903.92
#Mann= 5, -1 ,  0
       0     0.1       0   157.7   0.045       0   178.6     0.1       0
  229.55    0.06       0  329.55     0.1       0
Bank Sta=157.7,178.6
XS Rating Curve= 0 ,0
Exp/Cntr(USF)=0,0
Exp/Cntr=0.3,0.1

Type RM Length L Ch R = 1 ,30390   ,178.4,178.2,178.7
XS GIS Cut Line= 3
1608980.43876865431672.2931437631609249.82139568431688.690347148
1609318.92389566431660.580855632
#Sta/Elev= 30
       0  937.69     7.7  929.47    15.7  919.56    19.7  915.29    27.7  907.96
    31.7  905.15    43.8  900.27    47.8   897.4    51.8  892.48    55.8  886.57
    60.4  881.14    79.8  862.02    83.8  859.83    87.8  858.82   107.9  858.33
   118.5857.0983   139.7  856.05   147.9  856.18     153   857.1     168  861.04
   187.1  861.84   204.2  861.51   216.1  862.46   224.1  865.62   252.1  886.39
   259.7  891.43   269.9  896.92     281  900.31   328.5  907.49   344.5  910.97
#Mann= 5, -1 ,  0
       0     0.1       0   118.5   0.045       0     153     0.1       0
     210    0.06       0  309.88     0.1       0
#XS Ineff= 2 , 0
                          187.45          869.68
Permanent Ineff=
       F       F
Bank Sta=118.5,153
XS Rating Curve= 0 ,0
Exp/Cntr(USF)=0,0
Exp/Cntr=0.3,0.1

Type RM Length L Ch R = 1 ,30212   ,185.8,185.8,185.7
XS GIS Cut Line= 3
1608994.49351441431849.1486945531609234.59542111431869.059584377
1609307.21160752431913.566279277
#Sta/Elev= 30
       0   924.6     9.7  917.44    17.7  910.01    21.7  906.97    29.7  903.08
    33.7  898.95    49.8  873.37    56.5  864.92    61.8  861.24    77.9  855.34
    93.6  854.07     122  854.41     128855.2915   150.1  859.84   170.2  858.51
   190.3  861.02   210.3  861.53   223.3  865.44   230.4  866.47   247.6  866.18
   252.1  865.16   261.5  860.61   270.9  860.41   275.5  861.96   278.2  864.27
   289.6  879.77   294.3  883.93   308.4   890.8   317.3  896.52   326.1  900.35
#Mann= 4, -1 ,  0
       0     0.1       0    77.9   0.045       0     128    0.06       0
     200     0.1       0
Bank Sta=77.9,128
XS Rating Curve= 0 ,0
Exp/Cntr(USF)=0,0
Exp/Cntr=0.3,0.1

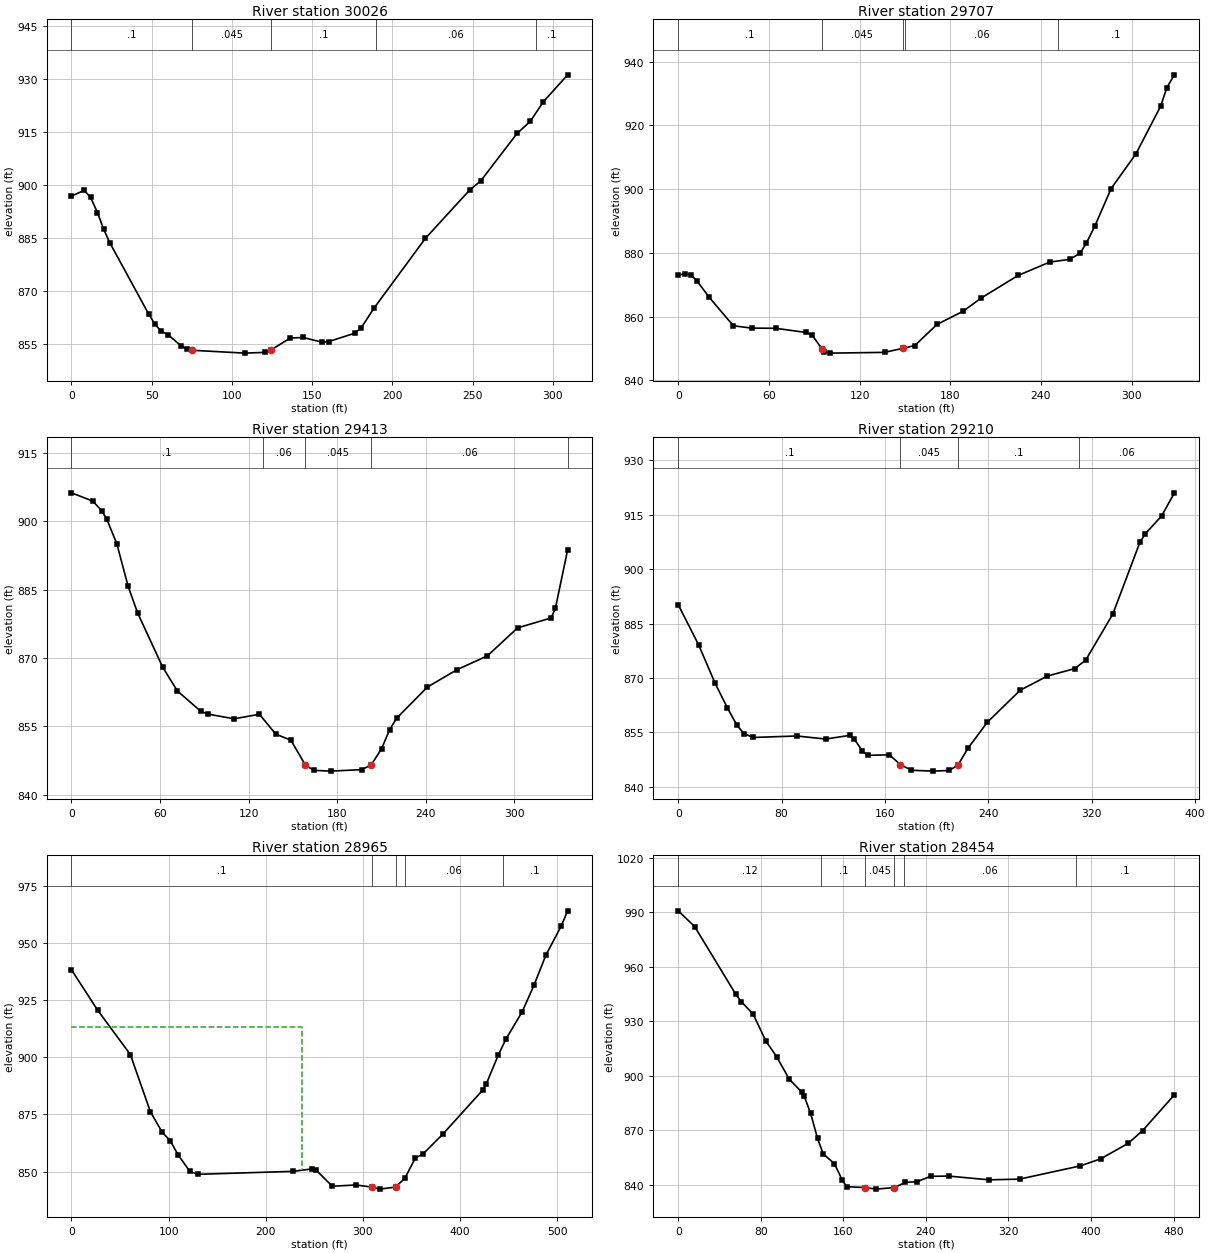
Type RM Length L Ch R = 1 ,30026   ,278.3,319.6,354.5
XS GIS Cut Line= 3
1609000.26531461432034.9046413871609238.84896173432055.148102355
1609306.80915213 432071.05367883
#Sta/Elev= 30
       0  896.85     7.9  898.44    11.9  896.49    16.2  892.17      20   887.5
    23.9   883.6      48   863.5      52  860.51      56  858.51    60.1  857.59
    68.1  854.49    72.1  853.46    75.4  853.14   108.2  852.34   120.3  852.55
   124.3  853.23   136.3   856.6   144.4  856.78   156.4   855.4   160.4  855.63
   176.5  857.98   180.5  859.49   188.5  865.08   220.6  884.89   248.3  898.63
     255  901.12   277.7  914.61   285.9  918.01   294.1   923.6   309.2   931.2
#Mann= 5, -1 ,  0
       0     0.1       0    75.4   0.045       0   124.3     0.1       0
     190    0.06       0  289.44     0.1       0
Bank Sta=75.4,124.3
XS Rating Curve= 0 ,0
Exp/Cntr(USF)=0,0
Exp/Cntr=0.3,0.1

Type RM Length L Ch R = 1 ,29707   ,269.2,293.3,315.9
XS GIS Cut Line= 3
1608956.88646967432152.0275227041608964.11627716432363.137901375
 1608938.0889702432477.368859697
#Sta/Elev= 30
       0     873     4.5  873.43     8.5  873.04    12.5  871.14    20.5  866.04
    36.5  857.12    48.5  856.39    64.5  856.33    84.6  855.02    88.6   854.2
      95 849.978    96.6  849.03   100.6  848.54   136.6  848.78   148.6  850.04
   156.6  850.92   171.2  857.52   188.6  861.69   200.6  865.85     225  872.92
   245.8  877.08   259.2  877.97   265.9  879.85   270.1  883.02   275.9  888.56
   286.5  900.16   302.9  911.03   319.3  926.01   323.4  931.85   328.4  935.83
#Mann= 5, -1 ,  0
       0     0.1       0      95   0.045       0   148.6     0.1       0
     150    0.06       0  251.23     0.1       0
Bank Sta=95,148.6
XS Rating Curve= 0 ,0
Exp/Cntr(USF)=0,0
Exp/Cntr=0.3,0.1

Type RM Length L Ch R = 1 ,29413   ,195.1,203.1,210.7
XS GIS Cut Line= 3
1608849.88531884432018.9990649111608797.83070492432065.269832839
1608589.61224925 432231.55540508
#Sta/Elev= 30
       0  906.21    14.4   904.4    20.4  902.33    23.8  900.51    30.7  895.07
    38.4  885.69    44.8  879.89    61.8  867.99    71.8  862.76    87.4  858.38
    92.3  857.72   110.2  856.67   127.3  857.68   138.4  853.31   148.6     852
   158.4 846.575     164  845.38   175.7  845.21   196.7  845.54   203.1   846.6
   210.1  850.15   215.5  854.29   220.3  856.82   241.1  863.64   261.2  867.45
   281.7  870.47   302.2  876.61   324.9  878.78   327.8  880.91   336.1  893.72
#Mann= 5, -1 ,  0
       0     0.1       0  129.65    0.06       0   158.4   0.045       0
   203.1    0.06       0  336.12     0.1       0
Bank Sta=158.4,203.1
XS Rating Curve= 0 ,0
Exp/Cntr(USF)=0,0
Exp/Cntr=0.3,0.1

Type RM Length L Ch R = 1 ,29210   ,244.9,245.1,247.3
XS GIS Cut Line= 3
1608787.17045791431903.3681619731608486.55506253432003.573293767
1608422.78816048432024.395139335
#Sta/Elev= 30
       0  890.18    15.9  879.04    28.5  868.58    38.1  861.73    45.4  857.03
    50.8  854.68      58  853.62    91.8  854.03     114  853.19     133  854.21
   136.2  853.22   142.5  849.89   146.6  848.71   163.4  848.83   171.9  846.17
   180.4  844.59   197.2  844.35   209.8  844.53   216.6846.0845   224.3   850.7
   239.3  857.84   264.6  866.62   285.7  870.54   306.8  872.59   315.2  874.85
   336.3  887.58   357.3  907.39   361.5  909.73   374.1  914.63     384     921
#Mann= 4, -1 ,  0
       0     0.1       0   171.9   0.045       0   216.6     0.1       0
     310    0.06       0
Bank Sta=171.9,216.6
XS Rating Curve= 0 ,0
Exp/Cntr(USF)=0,0
Exp/Cntr=0.3,0.1

Type RM Length L Ch R = 1 ,28965   ,521.6,510.8,502.2
XS GIS Cut Line= 4
1608824.51625164431656.1756885211608769.56971472431687.986841471
1608611.95991147431716.9060714261608329.99741941431770.406646843
#Sta/Elev= 30
       0  938.21    26.9  920.58    60.6  901.18    81.2  876.23    93.4   867.2
   101.6  863.55   109.9  857.25   121.9  850.11     130  848.87   227.6  850.16
     248  851.24   252.1  850.58   268.4  843.67   292.8  844.21   309.1  843.31
   317.2   842.4   333.5   843.3   343.1  847.12   353.9     856     362  857.81
   382.4   866.5   423.1  885.59   427.1  888.51   439.4   901.1   447.5  908.19
   463.8   919.8     476  931.41   488.2  944.55   503.9  957.19   510.7  963.96
#Mann= 5, -1 ,  0
       0     0.1       0   309.1   0.045       0   333.5     0.1       0
  343.73    0.06       0  443.73     0.1       0
#XS Ineff= 2 , 0
          237.67  913.11
Permanent Ineff=
       F       F
Bank Sta=309.1,333.5
XS Rating Curve= 0 ,0
Exp/Cntr(USF)=0,0
Exp/Cntr=0.3,0.1

Type RM Length L Ch R = 1 ,28454   ,344.7,335.8,327.9
XS GIS Cut Line= 4
1608552.50679455 431122.547525081608462.32217594431199.848626749
1608373.30878614431302.9167623091608242.13115906431486.799685977
#Sta/Elev= 30
       0  990.67    15.9  982.03    55.6  944.91    61.3  940.59    72.6  933.85
    84.8  919.15    95.3  910.45   107.5  898.11   119.7  890.93   122.2  888.53
   128.3  879.23     135  865.44   140.5  856.93   151.4  851.52   158.9  842.58
   163.4  838.86   181.2  838.42   191.7  837.56   209.5  838.43   220.1  841.28
   231.4  841.66   244.6  844.61   261.9  844.74   301.2  842.67   330.7  843.06
   389.6  850.35   409.3  854.21   436.1  862.79   449.9  869.72   480.8  889.45
#Mann= 6, -1 ,  0
       0    0.12       0  138.78     0.1       0   181.2   0.045       0
   209.5     0.1       0  218.78    0.06       0  384.97     0.1       0
Bank Sta=181.2,209.5
XS Rating Curve= 0 ,0
Exp/Cntr(USF)=0,0
Exp/Cntr=0.3,0.1