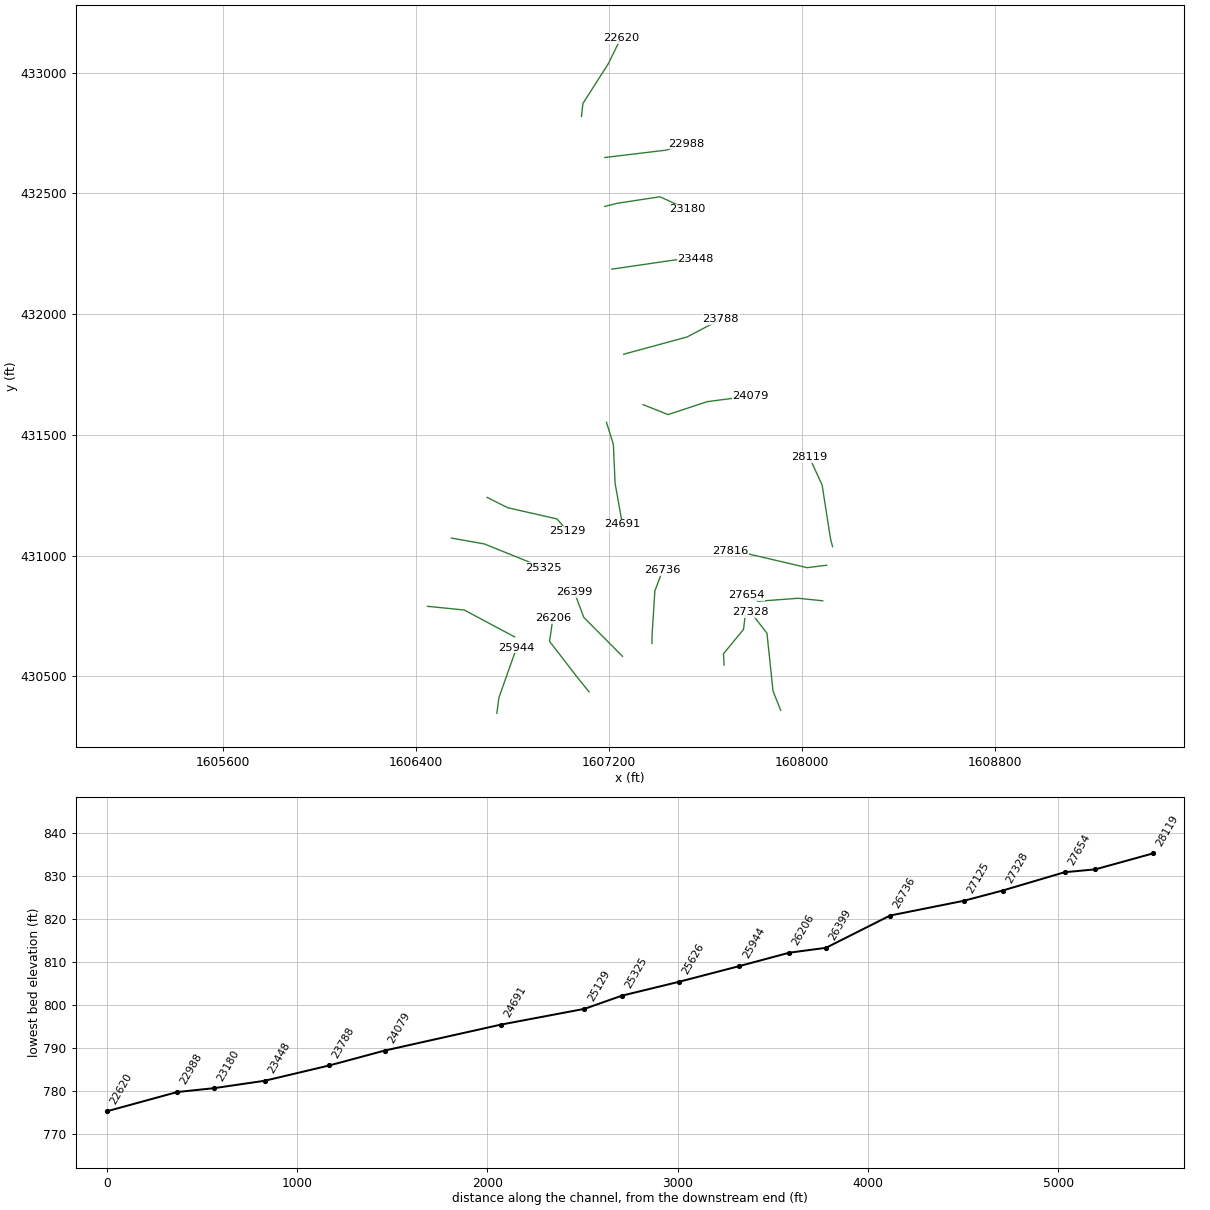
HEC-RAS study PROCTRCK.prj: PROCTRCK

--- PROCTRCK.g01 (geometry) --- (continued)

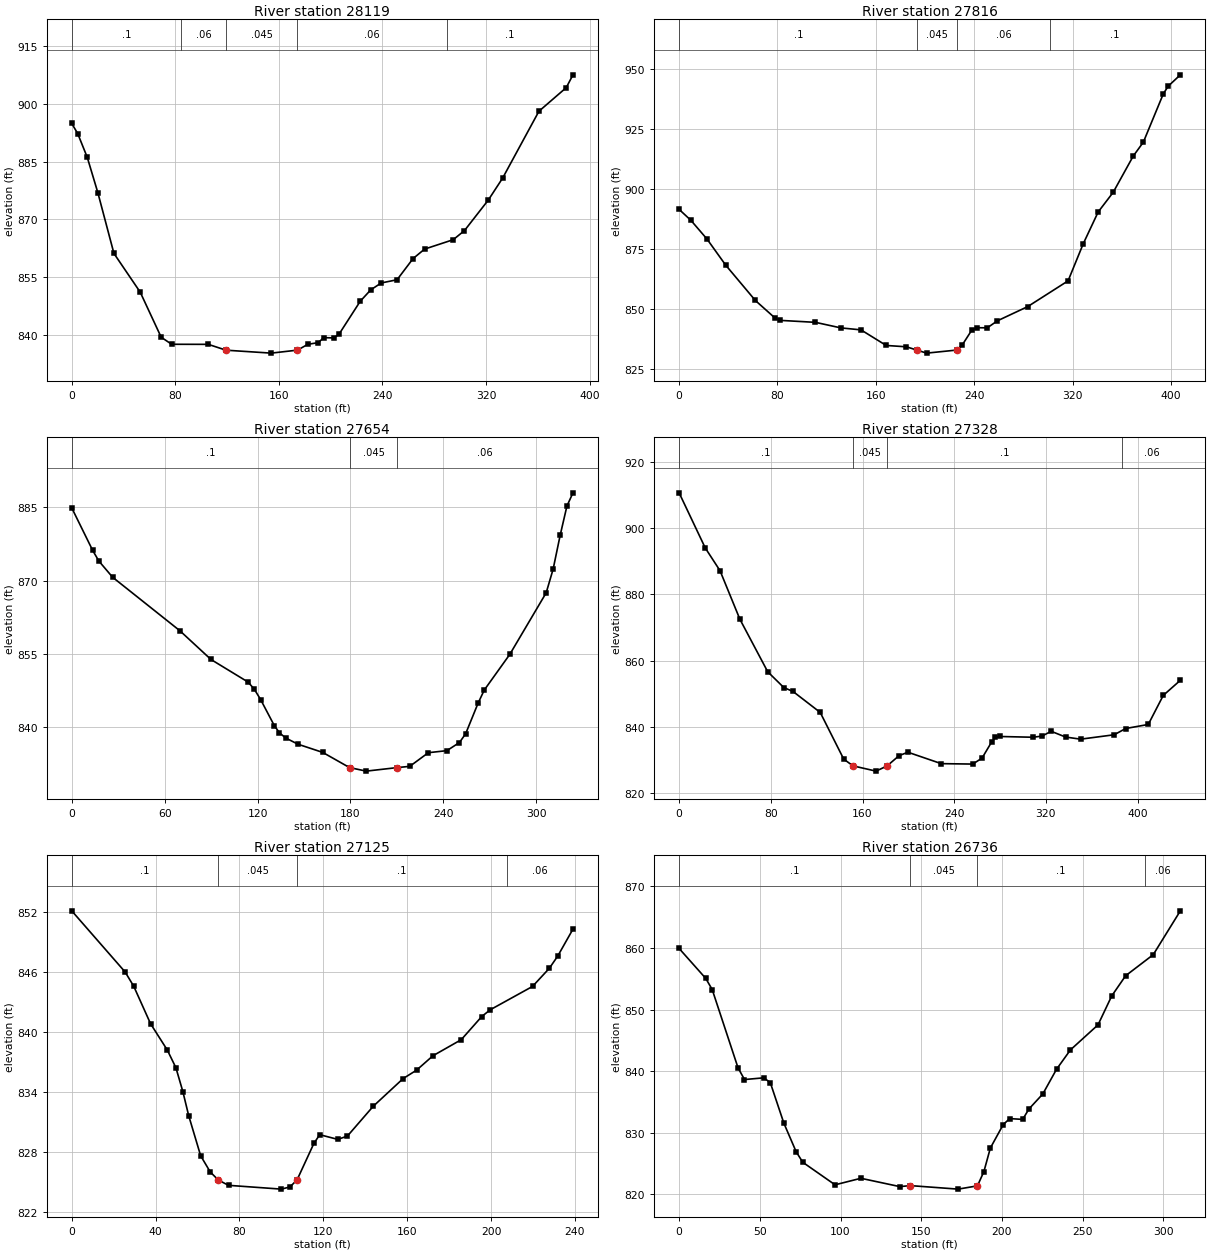
Type RM Length L Ch R = 1 ,28119   ,284,302.7,336.7
XS GIS Cut Line= 4
1608126.20867605431036.9694328711608117.53290706431070.226547319
1608082.82983112431292.904617972 1608029.3292557431408.581537792
#Sta/Elev= 30
       0  894.95     4.6  892.33      12  886.14    20.2  876.94    32.6  861.18
    52.9  851.12    69.1  839.41    77.2  837.58   105.5  837.56   119.2836.0428
   154.1  835.28   174.4  836.06   182.4  837.57   190.5  838.01   194.6   839.3
   202.7  839.23   206.7  840.31   222.9  848.77     231  851.72   239.1  853.51
   251.3  854.34   263.7  859.85   272.6  862.31   294.7  864.75   303.4  867.12
   321.8  875.05   332.9  880.77   360.9  898.12     382  904.25   387.2  907.58
#Mann= 5, -1 ,  0
       0     0.1       0   84.37    0.06       0   119.2   0.045       0
   174.4    0.06       0  289.74     0.1       0
Bank Sta=119.2,174.4
XS Rating Curve= 0 ,0
Exp/Cntr(USF)=0,0
Exp/Cntr=0.3,0.1

Type RM Length L Ch R = 1 ,27816   ,159.4,162.1,168.9
XS GIS Cut Line= 4
1608101.62733059 430960.333473491608020.65348671430950.211743006
1607786.40772408431005.1582799211607702.54195721431021.063856396
#Sta/Elev= 30
       0   891.4     9.6  886.84    22.7  879.04    37.8  868.25      62  853.49
    78.1  846.13    82.2  845.21   110.9  844.39   131.5  842.08   147.9  841.26
   168.4  834.77   184.9  834.21   193.8  832.77   201.3  831.58     226  832.87
   230.1  834.86   238.3  841.39   242.4  842.16   250.6  842.11   258.8  845.02
   283.5  850.95   316.3  861.66   328.6  877.06   340.8  890.35     353  898.52
   369.3   913.6   377.5  919.37   393.8  939.56   397.8  942.72   407.6   947.4
#Mann= 4, -1 ,  0
       0     0.1       0   193.8   0.045       0     226    0.06       0
   301.6     0.1       0
Bank Sta=193.8,226
XS Rating Curve= 0 ,0
Exp/Cntr(USF)=0,0
Exp/Cntr=0.3,0.1

Type RM Length L Ch R = 1 ,27654   ,359.1,325.6,314.3
XS GIS Cut Line= 4
1608085.54191267430813.0165950731607984.03151143430823.452243798
1607818.00982717430811.1192043951607768.67766956430835.785283201
#Sta/Elev= 30
       0   884.9    13.5  876.19    17.5     874    26.4  870.67    69.8  859.71
    89.9  853.81     114  849.15     118  847.66     122  845.58   130.8  840.26
   134.1  838.79   138.1  837.72   146.1  836.43   162.1  834.75   179.4  831.64
   190.2  830.91   210.3  831.64   218.3  831.89   230.3  834.69   242.3  835.11
   250.4  836.78   254.4  838.58   262.4  844.83   266.4  847.53   282.9  854.85
   306.4  867.48   310.9  872.35   315.4  879.23   319.8  885.27   323.7  887.98
#Mann= 3, -1 ,  0
       0     0.1       0   179.4   0.045       0   210.3    0.06       0
Bank Sta=179.4,210.3
XS Rating Curve= 0 ,0
Exp/Cntr(USF)=0,0
Exp/Cntr=0.3,0.1

Type RM Length L Ch R = 1 ,27328   ,221.5,203.6,198.1
XS GIS Cut Line= 4
1607911.44265369430359.3510914231607879.63150074  430438.8789738
1607854.48189241430678.7234993541607787.01911277430766.214291698
#Sta/Elev= 30
       0   910.7    22.8  894.06    35.7  887.18      53  872.54    77.3  856.67
    91.3  851.91    99.4  850.71   123.1  844.39   143.6  830.29   151.7  828.25
   171.8  826.66   181.4  828.22   191.9  831.33   199.6  832.37   228.7  828.92
   256.2  828.79   264.3   830.6   272.8  835.54     276  836.82   279.7  837.12
   308.8  836.89   316.6  837.24   324.6  838.69   337.2  836.95   350.3  836.31
   379.6  837.64   389.6  839.53   409.3  840.75   422.4  849.53   437.3  854.09
#Mann= 4, -1 ,  0
       0     0.1       0   151.7   0.045       0   181.4     0.1       0
  386.81    0.06       0
Bank Sta=151.7,181.4
XS Rating Curve= 0 ,0
Exp/Cntr(USF)=0,0
Exp/Cntr=0.3,0.1

Type RM Length L Ch R = 1 ,27125   ,373.8,388.1,399.3
XS GIS Cut Line= 4
1607677.26340528430547.0470155621607674.10108749430593.427676563
 1607757.3754561430694.6218460221607764.75419763430755.759990069
#Sta/Elev= 30
       0  852.14    25.5  846.01    29.6  844.58    37.6  840.84    45.6   838.2
    49.7  836.43      53  834.05    55.8  831.63    61.5  827.62    66.1  825.99
      70  825.18    74.8  824.66     100  824.28   104.1   824.5   107.5  825.21
   115.5  828.85   118.3  829.73   126.9  829.26   131.5  829.59   143.8  832.57
   158.1  835.35   164.5  836.19   172.3  837.63   185.8  839.24   195.6  841.56
   199.6  842.23   219.8  844.57   227.8  846.38   231.8   847.6   239.1  850.31
#Mann= 4, -1 ,  0
       0     0.1       0      70   0.045       0   107.5     0.1       0
  207.54    0.06       0
Bank Sta=70,107.5
XS Rating Curve= 0 ,0
Exp/Cntr(USF)=0,0
Exp/Cntr=0.3,0.1

Type RM Length L Ch R = 1 ,26736   ,316.3,337.4,349.5
XS GIS Cut Line= 4
1607377.96359382430636.0636312351607379.08398405430678.638459636
1607390.28788626430853.9795292321607422.77920267430940.249576254
#Sta/Elev= 30
       0  859.92    16.5  855.06    20.5  853.25    36.5  840.54    40.5  838.64
    52.5  838.92    56.5  838.13    64.9  831.55    72.5  826.92    76.6  825.21
    96.6  821.55   112.6  822.61   136.7  821.26   143.3  821.42   172.8  820.85
   184.8  821.38   188.8   823.7   192.8  827.52   200.8  831.34   204.8   832.3
   212.8  832.17   216.8  833.89   225.3   836.3   233.8  840.31   242.4  843.45
   259.5  847.52     268  852.22   276.6  855.49   293.7  858.91   310.5  866.03
#Mann= 4, -1 ,  0
       0     0.1       0   143.3   0.045       0   184.8     0.1       0
  288.29    0.06       0
Bank Sta=143.3,184.8
XS Rating Curve= 0 ,0
Exp/Cntr(USF)=0,0
Exp/Cntr=0.3,0.1

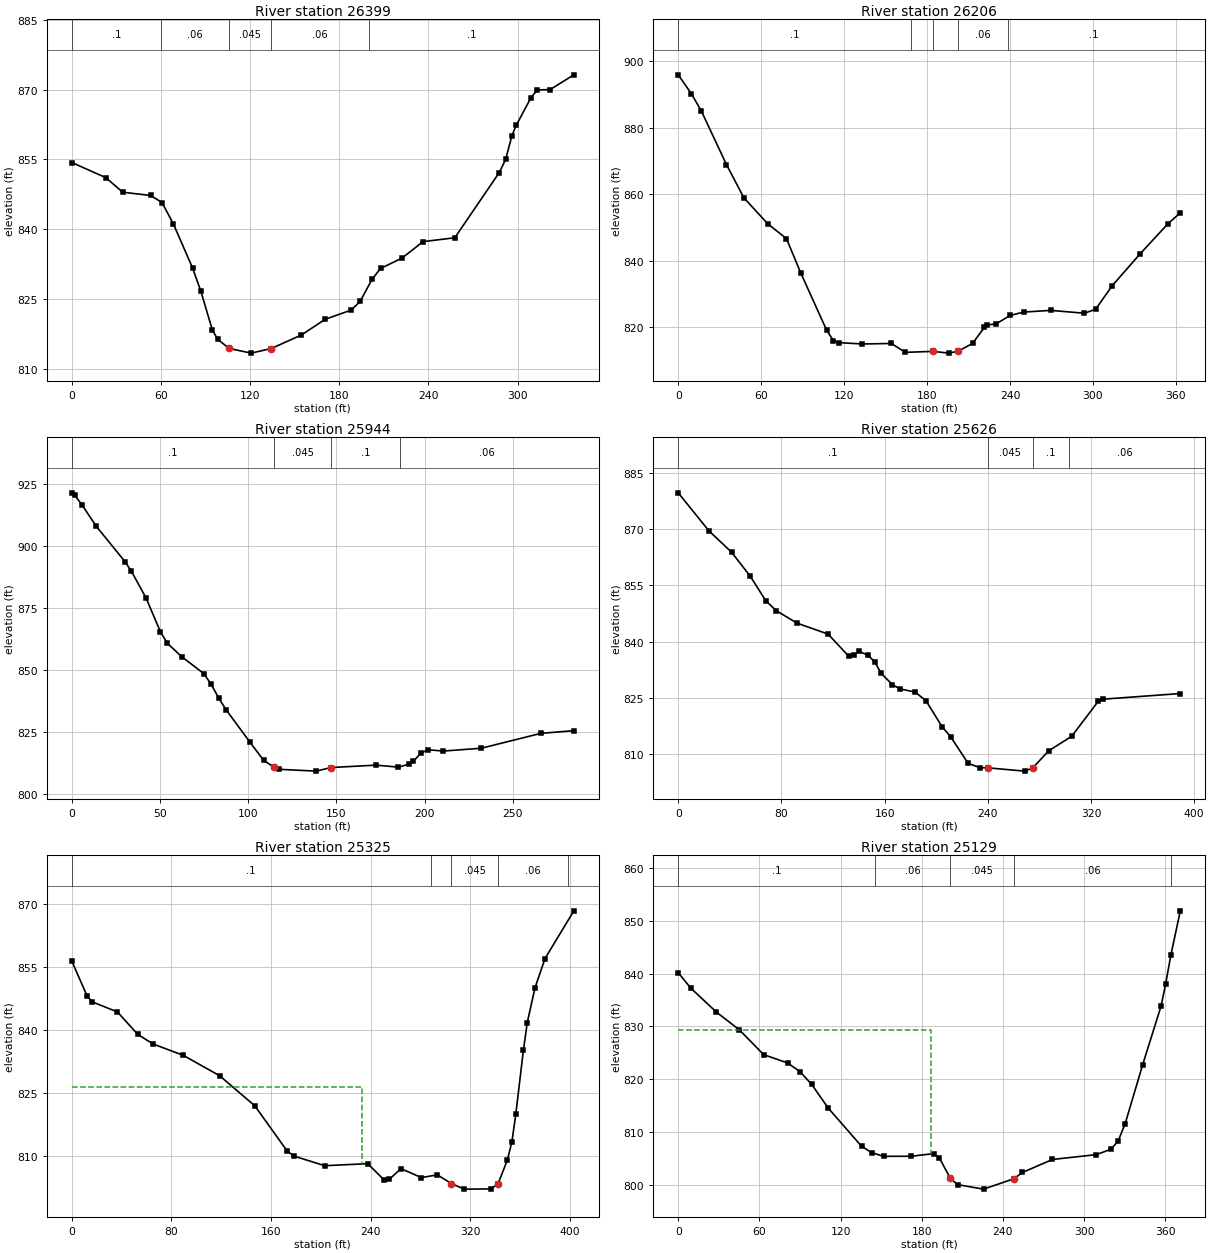
Type RM Length L Ch R = 1 ,26399   ,197,192.7,191
XS GIS Cut Line= 3
1607256.27627453430582.8707545821607095.81792712  430744.5003308
1607057.16737629430847.568466359
#Sta/Elev= 30
       0  854.33    22.9  851.08    34.3  847.94    53.1  847.24    60.7  845.73
    68.4  841.11    81.3  831.63    86.9  826.61    94.6   818.3    98.2  816.32
   105.9  814.35   120.7  813.35   134.2  814.34   154.5  817.25   170.6  820.64
     188   822.6     194  824.46   202.1  829.26   207.8  831.56   222.2  833.78
   236.3  837.32   257.7  838.15   287.6  852.16   291.9  854.98   296.1  860.06
     299  862.31     309  868.28   313.2  869.94   321.8     870   337.8  873.18
#Mann= 5, -1 ,  0
       0     0.1       0      60    0.06       0   105.9   0.045       0
   134.2    0.06       0     200     0.1       0
Bank Sta=105.9,134.2
XS Rating Curve= 0 ,0
Exp/Cntr(USF)=0,0
Exp/Cntr=0.3,0.1

Type RM Length L Ch R = 1 ,26206   ,280.7,262.6,251.8
XS GIS Cut Line= 4
1607118.07127457430435.5561971911607068.87966442430496.460095476
1606954.09924073430645.2061547491606968.15398648 430741.24691743
#Sta/Elev= 30
       0   895.9     9.5  890.23    16.7  885.03    34.9  868.91    47.5  858.91
    64.7  851.13    78.3  846.64    88.5  836.45   107.4  819.06   112.3  815.96
     116  815.39   133.1  814.97   154.2  815.12   164.3  812.45   184.3  812.75
   195.8  812.22   202.7 812.825   212.9  815.14   221.5  819.97   223.6  820.69
     230  821.03   240.1  823.55   249.8  824.56   269.5  825.07   293.8  824.22
   301.9   825.4     314  832.52   334.2  842.11   354.4  851.18   363.2  854.41
#Mann= 5, -1 ,  0
       0     0.1       0  168.29    0.06       0   184.3   0.045       0
   202.7    0.06       0  238.29     0.1       0
Bank Sta=184.3,202.7
XS Rating Curve= 0 ,0
Exp/Cntr(USF)=0,0
Exp/Cntr=0.3,0.1

Type RM Length L Ch R = 1 ,25944   ,349.2,317.3,294.5
XS GIS Cut Line= 3
1606735.93830559430346.8046067521606744.47656364 430412.26458512
1606817.52610472430618.131473612
#Sta/Elev= 30
       0   921.5     1.7  920.49     5.8  916.64    13.8  908.05    30.3  893.59
    33.8   889.8    42.1  879.04    50.2  865.42    54.2  860.71    62.3  855.33
    74.8   848.5      79  844.19    83.3  838.54    87.5  833.84   100.8  820.96
   108.7  813.47   114.7810.6264   117.2  809.85   138.5  809.11   146.9  810.56
   172.4  811.53   185.1  810.72   191.3  811.99   193.6  813.07   197.9  816.47
   202.1  817.72   210.6  817.22     232  818.35   265.8  824.36   284.5  825.45
#Mann= 4, -1 ,  0
       0     0.1       0   114.7   0.045       0   146.9     0.1       0
  186.01    0.06       0
Bank Sta=114.7,146.9
XS Rating Curve= 0 ,0
Exp/Cntr(USF)=0,0
Exp/Cntr=0.3,0.1

Type RM Length L Ch R = 1 ,25626   ,300.8,300.8,304.9
XS GIS Cut Line= 3
1606448.51398317430790.1429087881606600.77372888430774.916934217
1606809.25245763430663.650196965
#Sta/Elev= 30
       0  879.67    23.7  869.57    41.3  863.85    55.9   857.4    67.9  850.89
      76  848.25    92.1  844.92   116.2     842   132.3  836.06   136.3  836.31
   140.3   837.4   147.3  836.31   152.4  834.59   157.2  831.59   166.1   828.5
     172  827.37   183.6  826.56   192.1  824.23   204.5  817.35   211.2  814.63
   224.8  807.53   233.9  806.39     240  806.34   268.5  805.46   274.7  806.26
   287.3  810.89   305.1  814.76   325.8  824.14   329.1  824.64   389.3  826.15
#Mann= 4, -1 ,  0
       0     0.1       0     240   0.045       0   274.7     0.1       0
  303.02    0.06       0
Bank Sta=240,274.7
XS Rating Curve= 0 ,0
Exp/Cntr(USF)=0,0
Exp/Cntr=0.3,0.1

Type RM Length L Ch R = 1 ,25325   ,194.7,196,200.8
XS GIS Cut Line= 3
 1606547.9977087431072.7345226311606683.97737391431048.490086198
1606929.58405604430949.404128603
#Sta/Elev= 30
       0  856.37    12.3  848.08    16.4  846.68    36.7  844.27    52.9  838.97
    65.1   836.7    89.5  833.98   118.6  829.16   146.9  822.01   172.8  811.31
   178.1   810.1     203  807.79   237.5  808.27   250.4  804.51     255  804.57
   264.2   807.1   280.6  804.98   293.5  805.61   304.7  803.55   315.1  802.23
   336.7  802.28   342.2803.5474   349.6   809.1   353.3   813.5   356.4     820
   362.5  835.19   365.6  841.74   371.8  849.98   379.8  856.93     403  868.28
#Mann= 5, -1 ,  0
       0     0.1       0  288.12    0.06       0   304.7   0.045       0
   342.2    0.06       0  398.12     0.1       0
#XS Ineff= 2 , 0
          232.93  826.51
Permanent Ineff=
       F       F
Bank Sta=304.7,342.2
XS Rating Curve= 0 ,0
Exp/Cntr(USF)=0,0
Exp/Cntr=0.3,0.1

Type RM Length L Ch R = 1 ,25129   ,469.7,438.9,408.1
XS GIS Cut Line= 4
1606695.70590061431241.1445520981606781.08848109431198.453261858
1606985.05797891431151.9671902631607028.69796449431101.686337313
#Sta/Elev= 30
       0   840.2     9.4  837.23    28.2  832.73    45.2  829.36    63.1  824.67
      81  823.07    89.9  821.46    98.6  819.05   110.9  814.53   135.5  807.31
     143   806.1   151.9  805.39   172.4  805.41   188.8  805.91   192.9  805.16
   201.1  801.26   206.5  800.03   225.7  799.18   248.1  801.14   254.5  802.34
   276.7   804.8   309.2  805.72   319.8  806.73   325.1  808.24   330.4  811.55
   343.3   822.7   356.9   833.8   360.3  837.97   364.2   843.5   371.2  851.91
#Mann= 5, -1 ,  0
       0     0.1       0  145.46    0.06       0   201.1   0.045       0
   248.1    0.06       0  364.66     0.1       0
#XS Ineff= 2 , 0
          186.63  829.25
Permanent Ineff=
       F       F
Bank Sta=201.1,248.1
XS Rating Curve= 0 ,0
Exp/Cntr(USF)=0,0
Exp/Cntr=0.3,0.1

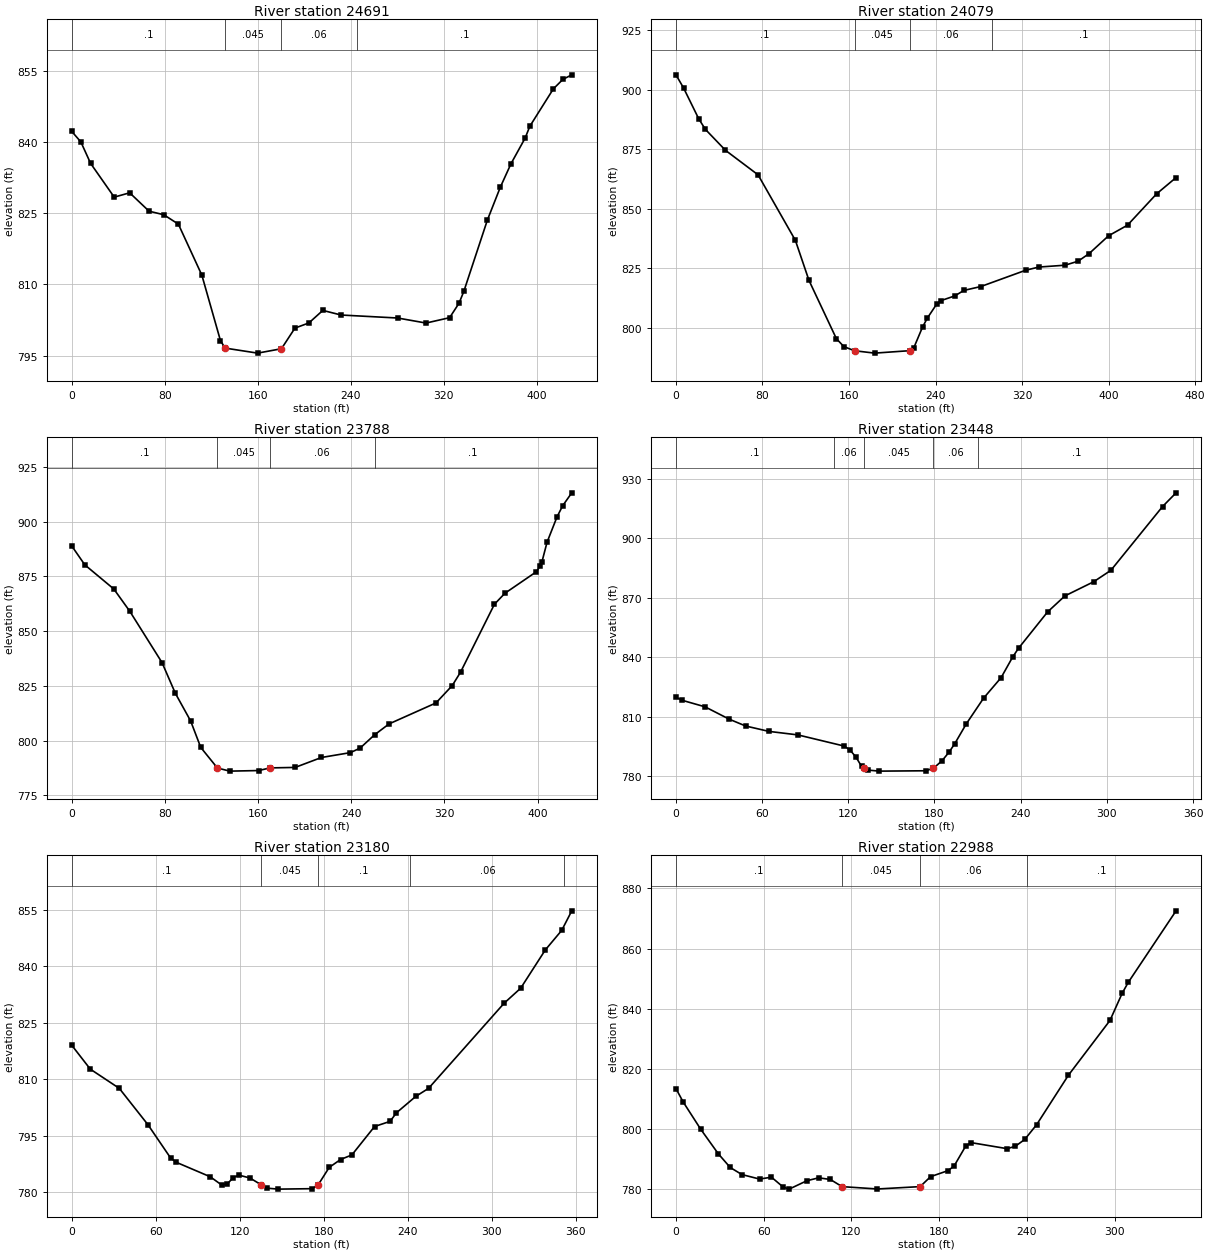
Type RM Length L Ch R = 1 ,24691   ,559.1,611.3,653.9
XS GIS Cut Line= 4
1607189.79535269431552.1199018071607218.35755512431461.077881578
1607225.49810572 431300.41549294 1607255.8454458431129.042278392
#Sta/Elev= 30
       0   842.2     7.9  839.97    16.3  835.45    36.6  828.35    49.9  829.26
    66.6  825.39    79.2  824.65    91.8  822.67     112  811.94     128  798.17
     132  796.58     160  795.52   180.5 796.445   192.1  800.79   204.1  801.87
   216.1  804.51   231.8  803.54   280.5  802.91   304.9  801.85   325.2  802.98
   333.3  806.03   337.4   808.5   357.7  823.53   368.8  830.43     378  835.38
   390.2  840.79   394.2  843.26   414.5  851.15   422.7  853.14   430.3  854.09
#Mann= 4, -1 ,  0
       0     0.1       0     132   0.045       0   180.5    0.06       0
  245.42     0.1       0
Bank Sta=132,180.5
XS Rating Curve= 0 ,0
Exp/Cntr(USF)=0,0
Exp/Cntr=0.3,0.1

Type RM Length L Ch R = 1 ,24079   ,292.1,291.4,290.2
XS GIS Cut Line= 4
1607341.53205307 431625.310545521607445.07003686431584.252379535
1607607.51756315431637.8065090811607786.03132831431661.013298551
#Sta/Elev= 30
       0  906.21     7.1  900.64    21.1  887.72    27.2  883.34    45.8  874.54
    75.9  864.27   110.4   836.8     123  819.98   148.3  795.58   155.2  792.23
   165.1  790.49   183.7  789.49   216.2  790.52   219.9  791.71     228  800.44
   232.5  804.23   240.9  809.94   245.2  811.54   257.8  813.49   266.2  815.79
   281.9  817.42   323.4  824.26   335.5  825.59   359.7  826.36   371.8  828.04
     382  831.23     400  838.71   417.5  843.15   444.4  856.29   462.4  863.12
#Mann= 4, -1 ,  0
       0     0.1       0   165.1   0.045       0   216.2    0.06       0
  292.43     0.1       0
Bank Sta=165.1,216.2
XS Rating Curve= 0 ,0
Exp/Cntr(USF)=0,0
Exp/Cntr=0.3,0.1

Type RM Length L Ch R = 1 ,23788   ,342.5,340.4,337.2
XS GIS Cut Line= 3
1607261.20085875431834.1716507511607523.61609353431905.577156812
1607662.85683035431978.767800525
#Sta/Elev= 30
       0  888.97    11.3  880.28    36.2  869.24    49.9  859.07    77.6  835.59
      89  821.59   102.1  808.98   110.8  796.87   125.1787.4557   135.7  786.03
   160.5  786.29   170.3787.5024   191.8  787.72   214.4  792.26   239.3  794.49
   247.6  796.55     260  802.62   272.5  807.62   312.7  817.18   326.7  825.13
   333.8  831.23   362.9  862.28   371.9   867.3   398.9  877.13   401.9  879.59
   403.6  881.48   408.1  890.65   416.7  902.29   421.6  907.38   429.3   913.2
#Mann= 4, -1 ,  0
       0     0.1       0   125.1   0.045       0   170.3    0.06       0
     260     0.1       0
Bank Sta=125.1,170.3
XS Rating Curve= 0 ,0
Exp/Cntr(USF)=0,0
Exp/Cntr=0.3,0.1

Type RM Length L Ch R = 1 ,23448   ,267.6,267.3,267.5
XS GIS Cut Line= 3
1607212.13860461 432186.391906851607475.62492198432224.950880123
1607557.56274018 432226.55750401
#Sta/Elev= 30
       0  819.82       4  818.32    20.2  814.97    37.1  808.71    48.5  805.27
    64.7  802.55    84.9  800.77   117.2  795.12   121.3  793.05   125.3  789.57
   129.3  784.82   131.2 783.985   133.4  783.01   141.5  782.47   173.8  782.65
   179.2783.8629   185.2  787.68     190  791.92     194  796.19   202.1   806.3
   214.2  819.35   226.4  829.71   234.4  840.08   238.5  844.53   258.7  862.86
   270.8  870.99   290.8  878.13   302.8   883.9   338.8  916.14   348.2  923.07
#Mann= 5, -1 ,  0
       0     0.1       0     110    0.06       0   131.2   0.045       0
   179.2    0.06       0     210     0.1       0
Bank Sta=131.2,179.2
XS Rating Curve= 0 ,0
Exp/Cntr(USF)=0,0
Exp/Cntr=0.3,0.1

Type RM Length L Ch R = 1 ,23180   ,191.8,191.8,191.2
XS GIS Cut Line= 4
1607183.17737671432446.3974361431607234.71144449432459.280953088
1607411.56699528432486.2192157911607525.17619016432433.513919198
#Sta/Elev= 30
       0  819.06    13.3  812.68      34  807.57    54.5  797.89    70.7  789.03
    74.8  787.88      99  784.04   107.1  781.87   111.2  782.13   115.2  783.74
   119.3  784.49   127.4  783.71   135.5  781.88   139.5  781.01   147.6  780.75
   171.9  780.87   175.9  781.77     184  786.53   192.1  788.63   200.2  789.85
   216.4  797.41   227.5  798.78     232  801.05   245.8  805.41     255  807.57
     309  830.23   320.8  834.21   338.4   844.4   350.1  849.59   357.3   854.8
#Mann= 5, -1 ,  0
       0     0.1       0   135.5   0.045       0   175.9     0.1       0
  242.02    0.06       0  352.02     0.1       0
Bank Sta=135.5,175.9
XS Rating Curve= 0 ,0
Exp/Cntr(USF)=0,0
Exp/Cntr=0.3,0.1

Type RM Length L Ch R = 1 ,22988   ,352.6,368.9,395.9
XS GIS Cut Line= 3
1607183.29626688432648.8400789471607437.14284093432679.365932788
1607519.08065914432706.678538857
#Sta/Elev= 30
       0  813.35     4.9  808.91    16.9  799.83      29   791.6    37.1  787.07
    45.1  784.71    57.2  783.21    65.3  783.84    73.3  780.56    77.4  779.86
    89.5  782.65    97.6  783.63   105.6  783.07   113.6  780.69   137.8  779.91
     167780.6971   174.1  784.01   186.1  786.03   190.2  787.55   198.2  794.25
   201.9  795.34   226.4  793.34     232   794.1   238.5   796.4   246.6  801.29
   268.4  817.81   296.8  836.04   305.2  845.15   309.4  848.79     342  872.55
#Mann= 4, -1 ,  0
       0     0.1       0   113.6   0.045       0     167    0.06       0
     240     0.1       0
Bank Sta=113.6,167
XS Rating Curve= 0 ,0
Exp/Cntr(USF)=0,0
Exp/Cntr=0.3,0.1

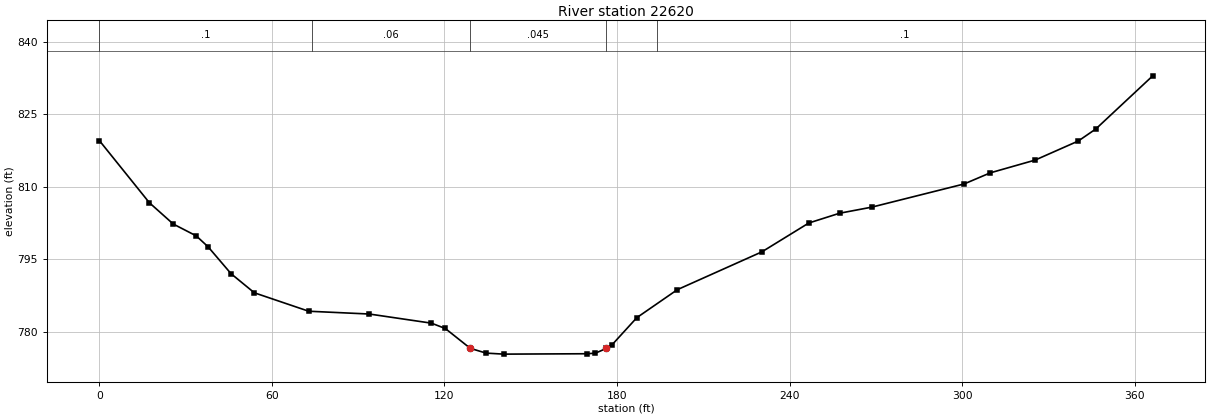
Type RM Length L Ch R = 1 ,22620   ,355.8,370.5,407.1
XS GIS Cut Line= 4
 1607086.3725627432819.0165182981607092.32302154432872.570647845
1607197.44779436433037.2000090421607249.01843762433142.324781855
#Sta/Elev= 30
       0  819.56    17.4   806.7    25.7   802.3    33.7  799.85    37.8   797.6
    45.8  792.03    53.9  788.08    72.8  784.27    93.9  783.69   115.5   781.8
   120.3   780.7     129  776.59   134.5  775.61   140.6   775.4   169.6  775.48
   172.5   775.6   176.3  776.58   178.3  777.34   186.9  782.94     201  788.73
   230.4  796.55   246.7  802.51   257.4  804.53   268.6  805.79   300.7  810.58
   309.8  812.88   325.4  815.52   340.4  819.46   346.5  821.95   366.3  832.94
#Mann= 5, -1 ,  0
       0     0.1       0   73.88    0.06       0     129   0.045       0
   176.3    0.06       0  193.88     0.1       0
Bank Sta=129,176.3
XS Rating Curve= 0 ,0
Exp/Cntr(USF)=0,0
Exp/Cntr=0.3,0.1