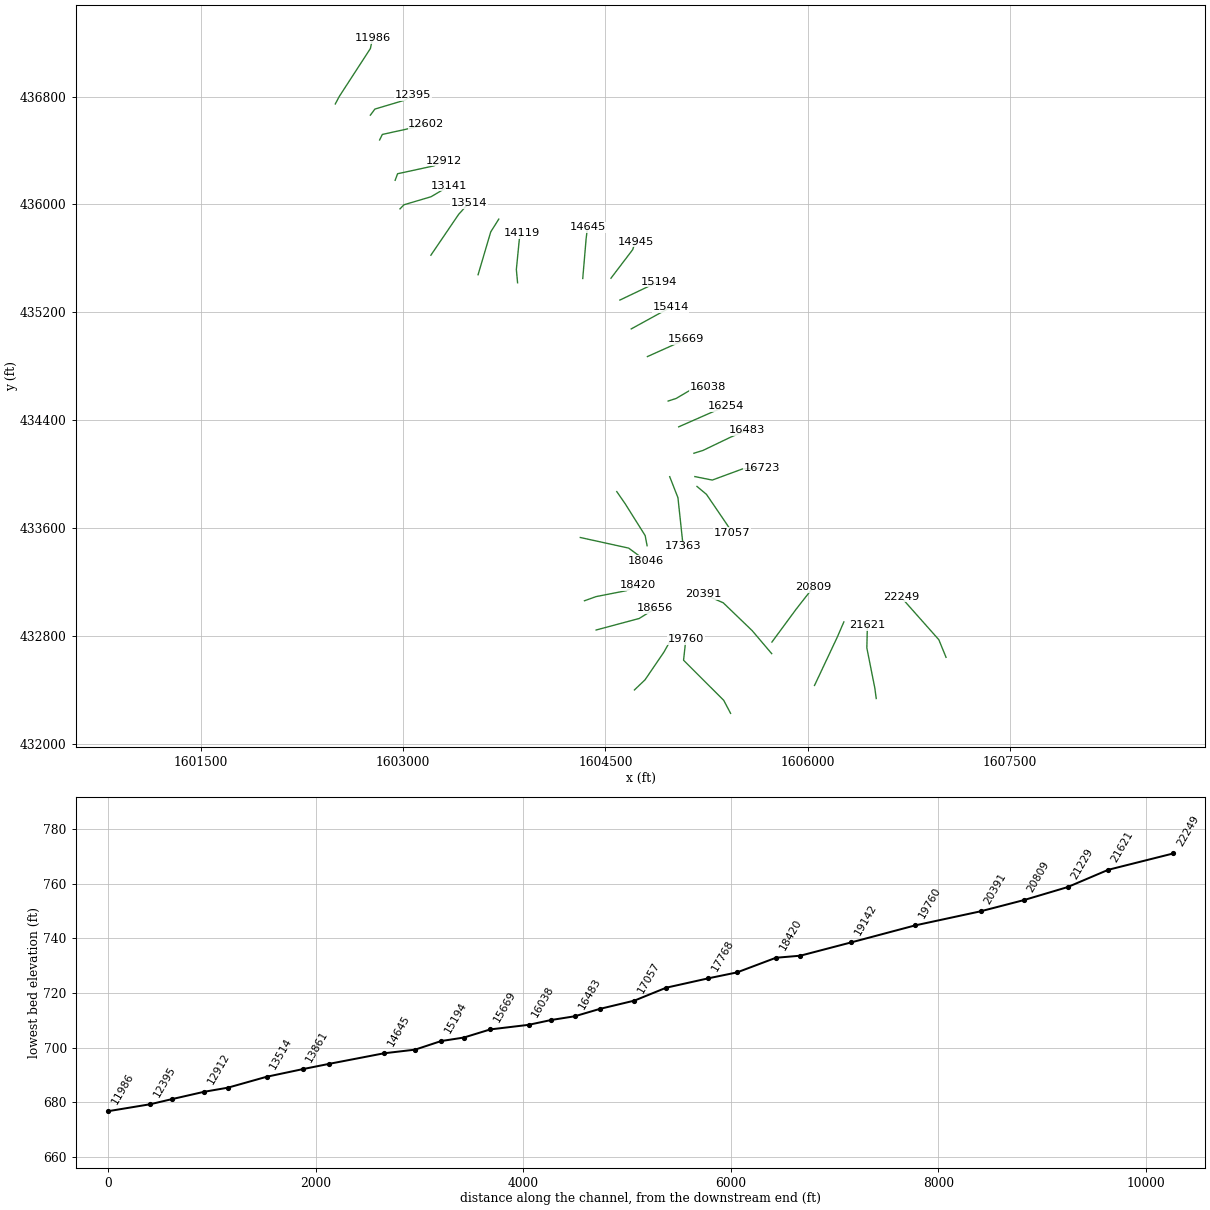
HEC-RAS study PROCTRCK.prj: PROCTRCK

--- PROCTRCK.g01 (geometry) --- (continued)

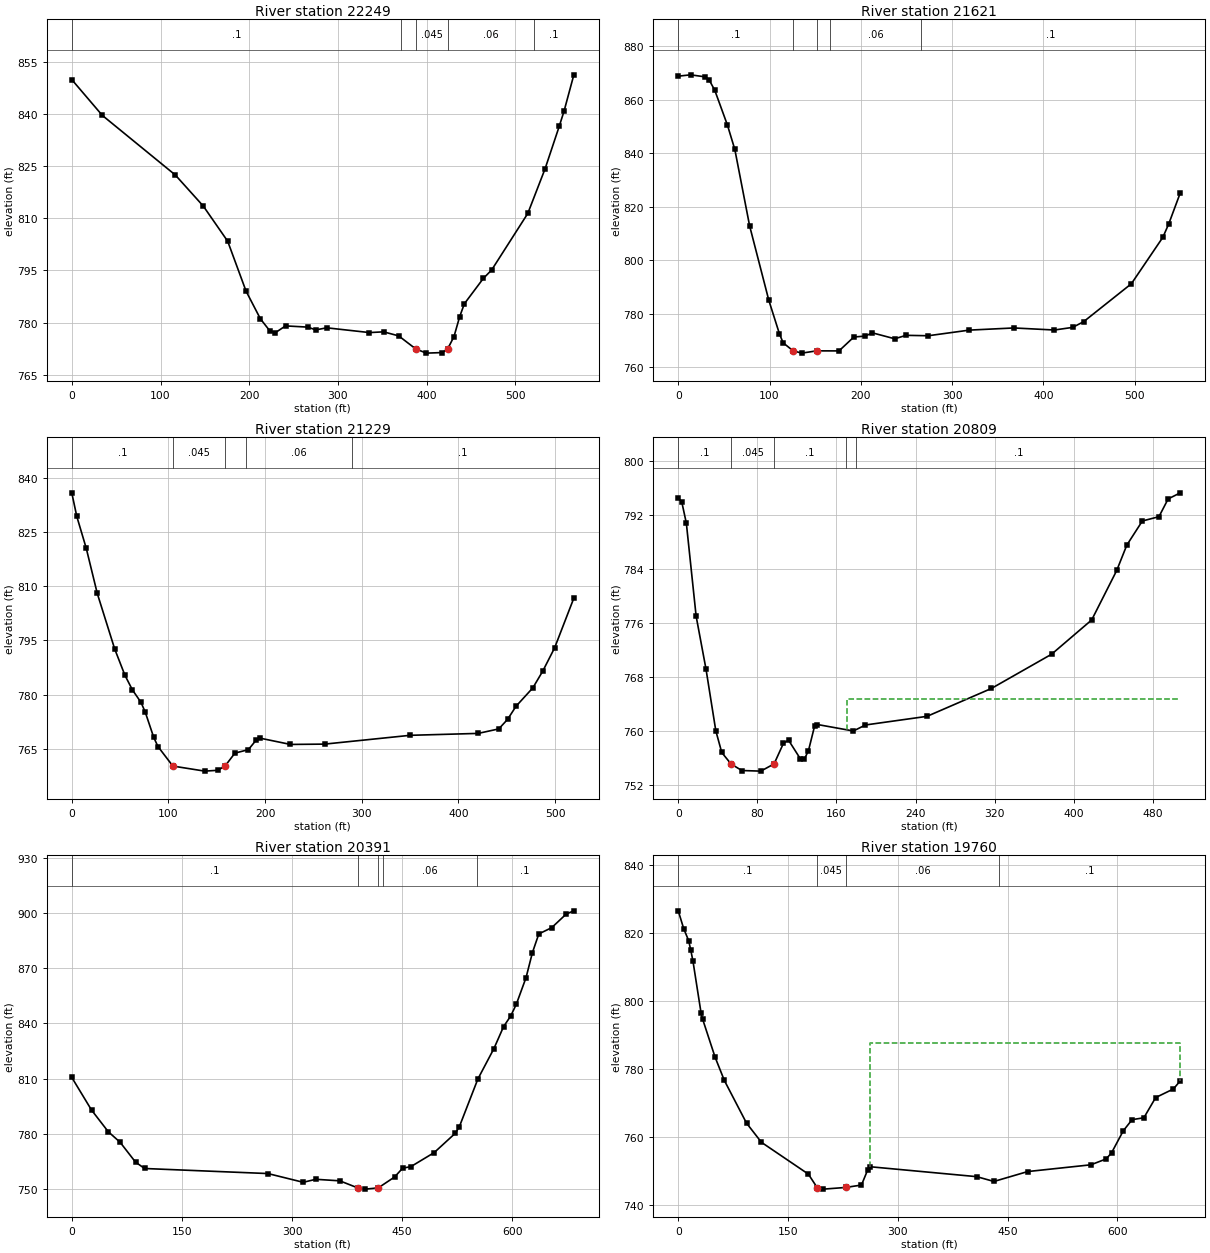
Type RM Length L Ch R = 1 ,22249   ,640.7,627.7,630.9
XS GIS Cut Line= 3
1607024.88448804432640.5027531441606971.33035849 432771.41284759
1606689.67530681433088.770652309
#Sta/Elev= 30
       0  849.88    34.4  839.59   116.7  822.44   148.3  813.48   175.7   803.4
   196.4  789.05   212.6  781.07   223.2  777.62   229.5  777.11   240.9  779.05
     266   778.7   274.9   777.9   287.3   778.5   335.5  777.13   351.4  777.34
   368.4  776.18   387.5772.4542   399.5  771.22   417.5  771.38   423.5  772.39
   430.7  775.96   437.1  781.67   442.4  785.41   463.8   792.7   473.2  795.14
   513.9  811.39   533.4  824.25   549.4   836.5   554.8  840.85   565.8  851.25
#Mann= 5, -1 ,  0
       0     0.1       0  371.44    0.06       0   387.5   0.045       0
   423.5    0.06       0  521.44     0.1       0
Bank Sta=387.5,423.5
XS Rating Curve= 0 ,0
Exp/Cntr(USF)=0,0
Exp/Cntr=0.3,0.1

Type RM Length L Ch R = 1 ,21621   ,407.2,392.5,385.4
XS GIS Cut Line= 4
1606507.19456909432335.045866102 1606497.2771377432410.418344723
1606437.77254931432709.9247729261606441.73952187432878.521106683
#Sta/Elev= 30
       0  868.74    13.6  869.24    29.7  868.47    33.8  867.37      40  863.48
    53.9  850.44      62  841.33    78.2  812.78    99.2  784.99   110.8  772.49
   114.9  769.07   125.8766.0778   135.3  765.21   151.6  766.06   176.1  766.04
   192.4  771.24   204.6  771.57   212.8  772.78   237.2  770.57   249.5  771.86
   273.9  771.71   318.8  773.81   367.7  774.62     412  773.85     432  774.83
     444  776.94   496.4  791.15   530.9  808.52   537.4  813.58     550  825.15
#Mann= 5, -1 ,  0
       0     0.1       0   125.8   0.045       0   151.6     0.1       0
  166.02    0.06       0  266.02     0.1       0
Bank Sta=125.8,151.6
XS Rating Curve= 0 ,0
Exp/Cntr(USF)=0,0
Exp/Cntr=0.3,0.1

Type RM Length L Ch R = 1 ,21229   ,426.5,419.4,415.4
XS GIS Cut Line= 3
1606049.73539827432431.7895704611606219.03159039432791.543978722
  1606267.401931432903.400391374
#Sta/Elev= 30
       0  835.79     5.2  829.26      15  820.44    26.4  807.96    44.4  792.63
      55  785.35    62.7  781.33    71.6  777.87      76  775.18    84.8  768.18
    89.2  765.64   104.6  760.25   137.6  758.85   151.1  759.08   158.7  760.29
   168.8  763.83   182.7  764.78   190.9  767.46   194.7  767.97   226.3  766.23
   261.7  766.32   350.1  768.75   420.5  769.28   441.8  770.52   450.9  773.15
   459.7  776.79   477.1  781.88   487.4  786.53   499.6  792.93   519.5  806.69
#Mann= 5, -1 ,  0
       0     0.1       0   104.6   0.045       0   158.7     0.1       0
     180    0.06       0     290     0.1       0
Bank Sta=104.6,158.7
XS Rating Curve= 0 ,0
Exp/Cntr(USF)=0,0
Exp/Cntr=0.3,0.1

Type RM Length L Ch R = 1 ,20809   ,406.7,418.5,445.6
XS GIS Cut Line= 3
 1605733.9941416432753.9263047831605910.84969238432994.028211484
1606039.68486183433159.171474142
#Sta/Elev= 30
       0  794.56     3.6  793.92     8.2   790.8    18.1  777.03    28.1  769.18
      38  760.07      44  756.86    53.4755.1575    64.3  754.19    83.5   754.1
   96.92  755.17   106.4  758.22   111.5  758.69   123.5  755.92   127.4  755.83
   131.7  757.14   137.8  760.72   140.7     761   177.1  760.04   189.3  760.93
   251.6  762.21   316.6  766.33   377.5   771.4   418.1  776.48   443.4   783.8
   453.6  787.55   469.3  791.12   486.1  791.76   495.4  794.39   507.7  795.29
#Mann= 5, -1 ,  0
       0     0.1       0    53.4   0.045       0   96.92     0.1       0
     170    0.06       0     180     0.1       0
#XS Ineff= 2 , 0
                          170.73           764.8
Permanent Ineff=
       F       F
Bank Sta=53.4,96.92
XS Rating Curve= 0 ,0
Exp/Cntr(USF)=0,0
Exp/Cntr=0.3,0.1

Type RM Length L Ch R = 1 ,20391   ,638.1,631.3,633.1
XS GIS Cut Line= 4
1605732.29574024432667.9945161831605587.50124184432838.574336219
1605373.28472366433044.8569092861605224.52325269433110.311956509
#Sta/Elev= 30
       0  810.68    26.9  792.95    49.7  781.17    65.8  775.45    86.8  764.66
    99.2  761.18   267.1  758.43   315.2  753.68   332.2  755.31     365  754.48
   389.3750.6583   399.6  749.97   417.3  750.63   439.5  756.54   450.6  761.36
   461.7  762.18   493.5  769.82   522.4  780.38   527.9     784     553  809.81
   574.9  826.38     588  838.27   597.7  844.04   605.4  850.47   618.6   864.9
   627.3  878.52     636  888.66   653.5  892.03   673.5  899.52   683.7   901.2
#Mann= 5, -1 ,  0
       0     0.1       0   389.3   0.045       0   417.3     0.1       0
  423.75    0.06       0  551.14     0.1       0
Bank Sta=389.3,417.3
XS Rating Curve= 0 ,0
Exp/Cntr(USF)=0,0
Exp/Cntr=0.3,0.1

Type RM Length L Ch R = 1 ,19760   ,649.9,617.4,600.3
XS GIS Cut Line= 4
1605427.62570221432224.8158461131605376.87245364432321.116881863
1605078.85978895 432619.129546551605095.77753848432773.992022958
#Sta/Elev= 30
       0  826.47     7.5  821.22    14.2  817.74    17.2  814.88    20.2   811.6
    31.3  796.34    33.3   794.7    50.4  783.49      63  776.69    93.3  764.17
   113.7  758.53   177.8   749.2   189.8745.2568   198.5  744.79   228.7  745.28
   250.4  745.99   258.9  750.44   262.7  751.35   407.9  748.45   431.4  747.04
   477.6  749.95   563.9  751.93   584.7  753.65   592.1  755.43   608.2  761.92
   620.2  765.18   636.3  765.73   652.4  771.66   676.6  774.18   686.1  776.58
#Mann= 4, -1 ,  0
       0     0.1       0   189.8   0.045       0   228.7    0.06       0
  438.86     0.1       0
#XS Ineff= 2 , 0
                          262.19          787.63
Permanent Ineff=
       F       F
Bank Sta=189.8,228.7
XS Rating Curve= 0 ,0
Exp/Cntr(USF)=0,0
Exp/Cntr=0.3,0.1

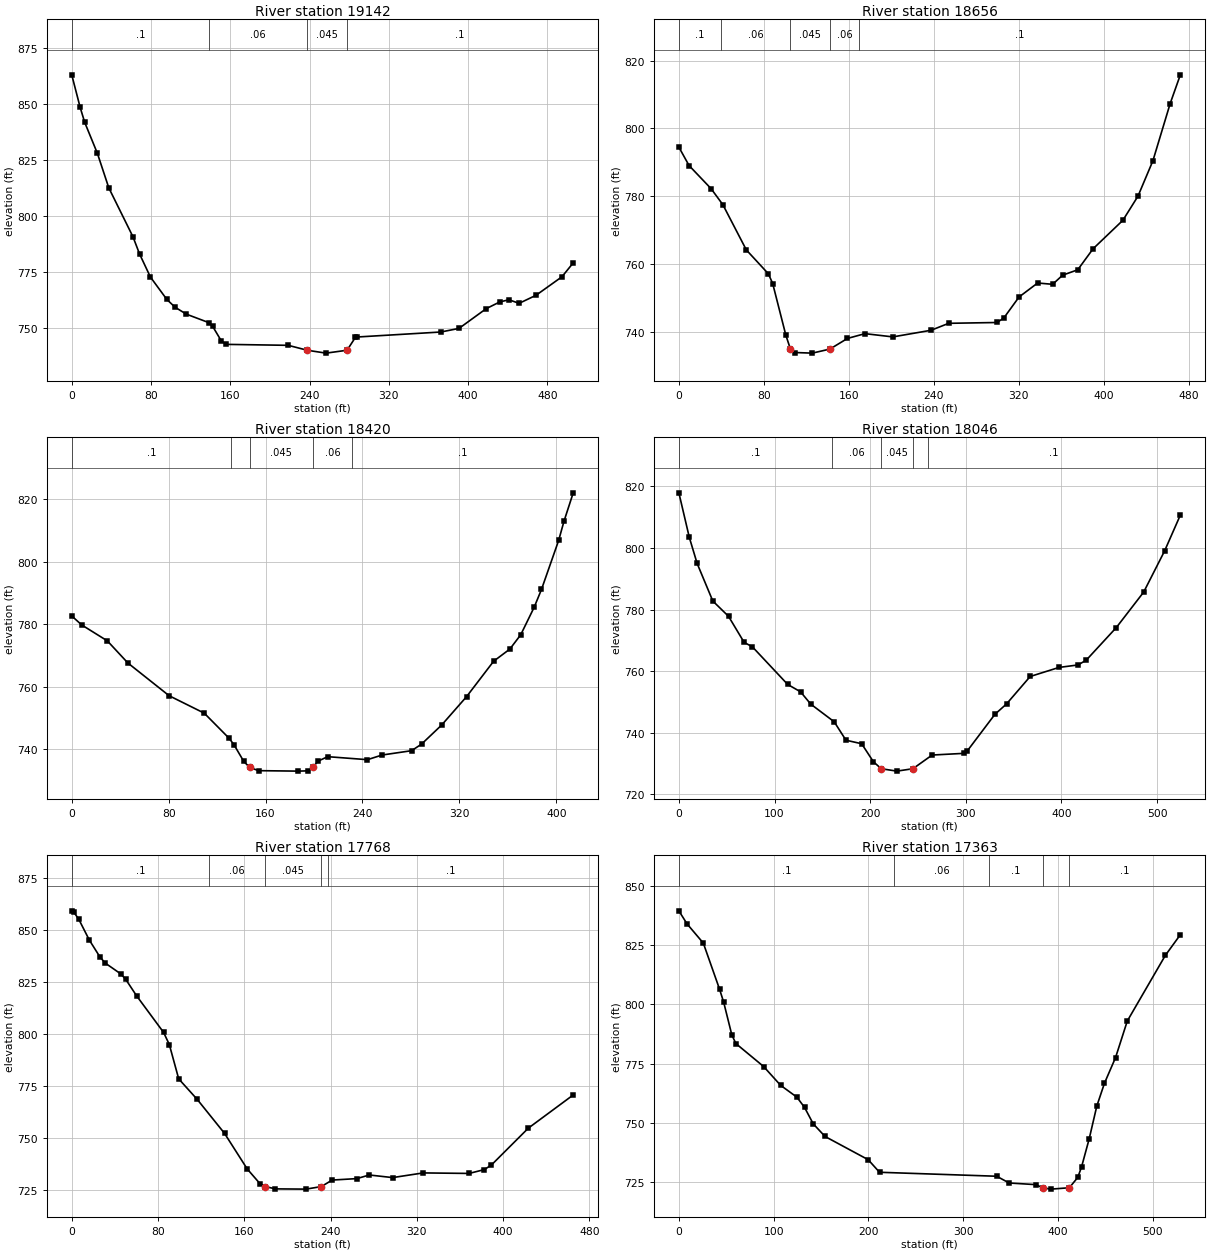
Type RM Length L Ch R = 1 ,19142   ,497.9,486.7,471.4
XS GIS Cut Line= 4
1604714.64675274432398.6882310631604793.19280941432473.664012427
1604934.21868388432680.7399800061605005.62418994432809.269890917
#Sta/Elev= 30
       0  863.05     8.5  848.48    13.1  841.77    25.9  827.91    37.4  812.49
    61.8  790.59    68.4  782.97    79.4  772.58      96  762.56   104.2  759.11
   115.6  755.99   138.7  752.13   142.2  750.55   150.8  744.14   155.6  742.46
   218.5  742.03   237.9  739.81   256.7  738.54   277.9739.8256   286.3  745.57
   288.4  745.76   372.6  747.99   390.9   749.6   418.4  758.44   432.1  761.45
   441.3  762.41   451.6  760.82   468.7  764.43   494.8  772.69   506.2  778.92
#Mann= 4, -1 ,  0
       0     0.1       0  138.59    0.06       0   237.9   0.045       0
   277.9     0.1       0
Bank Sta=237.9,277.9
XS Rating Curve= 0 ,0
Exp/Cntr(USF)=0,0
Exp/Cntr=0.3,0.1

Type RM Length L Ch R = 1 ,18656   ,236.3,235.4,234.2
XS GIS Cut Line= 3
1604430.80986614432843.1875062971604750.34950577432928.874113571
1604869.95372842433003.849894936
#Sta/Elev= 30
       0  794.49     9.6  789.05    30.3  782.24    41.4  777.51    63.5  764.15
    84.2  757.12    88.3  754.24   100.7  738.97   104.9  734.99     109  733.87
   125.6  733.69   142.2  734.89   158.7  738.03   175.2  739.44   201.4  738.48
   237.4  740.44     254  742.49   299.5  742.73   305.9  744.08   320.2  750.26
   337.7  754.39   351.8     754   361.2   756.7   375.4  758.28   389.9   764.5
   417.9  772.89   432.1     780   446.2  790.49   462.4  807.33     472  815.83
#Mann= 5, -1 ,  0
       0     0.1       0      40    0.06       0   104.9   0.045       0
   142.2    0.06       0     170     0.1       0
Bank Sta=104.9,142.2
XS Rating Curve= 0 ,0
Exp/Cntr(USF)=0,0
Exp/Cntr=0.3,0.1

Type RM Length L Ch R = 1 ,18420   ,386.4,374.5,368
XS GIS Cut Line= 4
1604344.40769358433060.1557426191604430.35876569433091.009973633
1604655.15387737433135.0874465111604738.90107583433176.961045744
#Sta/Elev= 30
       0  782.65     8.2  779.78    29.4  774.66    46.4  767.56    80.4  757.09
   109.4   751.5   129.8   743.5   133.9  741.42     142  736.06   146.9734.1004
   154.3  733.08   186.9  732.93     195  733.02   199.1  734.11   203.2   736.1
   211.3  737.56   244.1   736.6   256.2  738.09   280.6  739.48   288.8  741.59
   305.4   747.7   325.9  756.77   348.3  768.14   361.7  772.04   370.7  776.64
   381.8  785.47   387.8  791.14     402  806.88   406.4  813.02     414   822.1
#Mann= 5, -1 ,  0
       0     0.1       0  131.32    0.06       0   146.9   0.045       0
   199.1    0.06       0  231.32     0.1       0
Bank Sta=146.9,199.1
XS Rating Curve= 0 ,0
Exp/Cntr(USF)=0,0
Exp/Cntr=0.3,0.1

Type RM Length L Ch R = 1 ,18046   ,296.8,277.7,263.7
XS GIS Cut Line= 3
1604313.45649213433529.4375769781604671.73361879433450.713006545
1604798.65690582433357.528821135
#Sta/Elev= 30
       0  817.86    10.9  803.43    19.1  794.94    35.5  782.75    51.9   777.8
    68.2  769.35    76.9  767.88   113.8  755.68   127.2   753.3   137.9   749.3
   162.4  743.57   174.7  737.59   191.1  736.45   203.4   730.6   211.6  728.34
   227.9  727.56   244.7  728.34   264.8  732.78   297.6  733.32   301.7  734.18
   330.4  745.98   342.6  749.37   367.3  758.27   397.5  761.21   417.3  762.01
   425.9  763.56   457.4  774.16     486  785.67   507.8  798.98   524.3  810.64
#Mann= 5, -1 ,  0
       0     0.1       0     160    0.06       0   211.6   0.045       0
   244.7    0.06       0     260     0.1       0
Bank Sta=211.6,244.7
XS Rating Curve= 0 ,0
Exp/Cntr(USF)=0,0
Exp/Cntr=0.3,0.1

Type RM Length L Ch R = 1 ,17768   ,427.7,405.2,391.2
XS GIS Cut Line= 4
1604583.70078698433869.9632632741604644.75249467433781.598949523
 1604794.1685161433543.8186143371604808.62813108433468.307291677
#Sta/Elev= 30
       0  859.27     1.7  858.82     6.6  855.13    16.3  845.22      26   837.2
    30.9   834.2    45.5  828.91      50  826.36    60.1  818.42    85.2  800.76
    90.5  794.94    99.2  778.43   116.4  768.53   141.7  752.21   162.8  735.05
   174.8  727.88   179.5  726.62   188.9   725.5   217.3  725.38   231.5  726.61
   241.5  729.74   264.4  730.44     276  732.18   297.6  730.93     326  733.18
   368.5  732.93   382.7  734.78   389.3  737.02   423.5  754.73   465.1  770.68
#Mann= 5, -1 ,  0
       0     0.1       0   127.4    0.06       0   179.5   0.045       0
   231.5    0.06       0   237.4     0.1       0
Bank Sta=179.5,231.5
XS Rating Curve= 0 ,0
Exp/Cntr(USF)=0,0
Exp/Cntr=0.3,0.1

Type RM Length L Ch R = 1 ,17363   ,299.8,305.5,313.2
XS GIS Cut Line= 3
  1604976.169024433980.5750284611605037.22073168433824.732511482
1605075.77970496 433464.84876093
#Sta/Elev= 30
       0  839.51     8.6  834.01    25.8  825.88      43  806.34    47.3   800.9
    55.9  787.08    60.2  783.43    89.5  773.72   107.4  765.79   124.6  760.78
   132.7  756.43   141.8  749.53   154.3  744.18   199.8  734.38   211.8  729.06
   335.5  727.38   348.6  724.53   376.8  723.84   384.6  722.42   392.9  721.94
   412.1  722.52     421  726.86     425  731.28   433.1   743.2   441.1  756.98
   449.2  766.67   460.9   777.5   473.3  792.96   513.5   820.7   529.3  829.42
#Mann= 5, -1 ,  0
       0     0.1       0  227.37    0.06       0  327.37     0.1       0
   384.6   0.045       0   412.1     0.1       0
Bank Sta=384.6,412.1
XS Rating Curve= 0 ,0
Exp/Cntr(USF)=0,0
Exp/Cntr=0.3,0.1

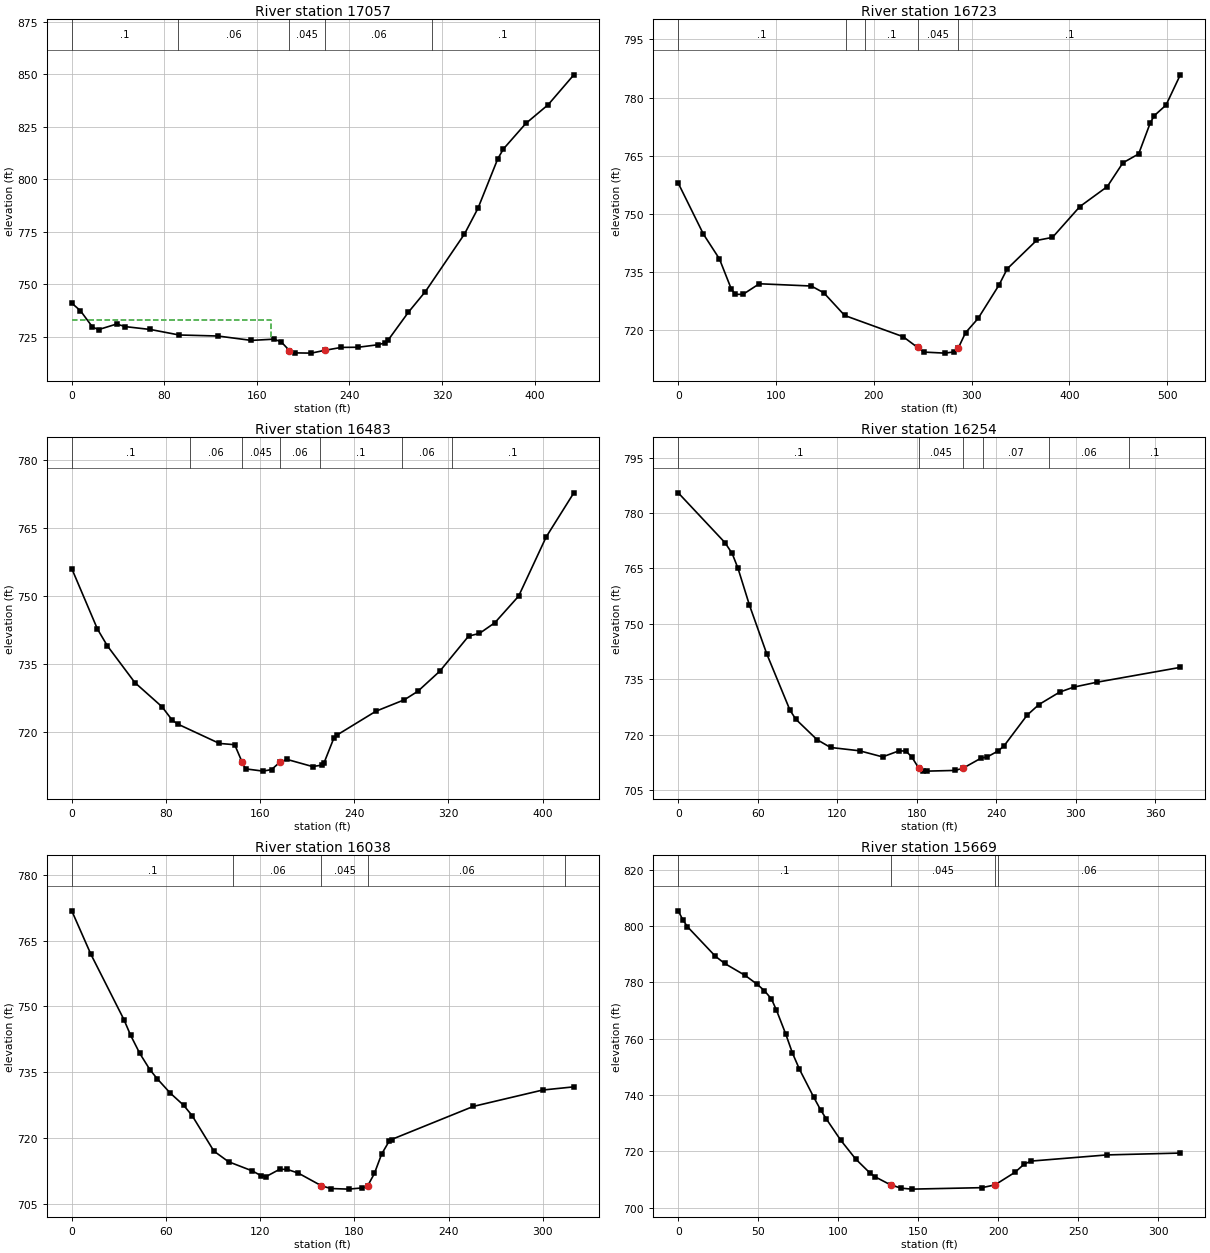
Type RM Length L Ch R = 1 ,17057   ,313.8,333.8,361.8
XS GIS Cut Line= 4
1605178.36816214433908.0950531081605248.64189093433849.533612449
1605383.33320445433651.595943022 1605440.7234163 433566.09623966
#Sta/Elev= 30
       0  741.04     7.5   737.4    17.9  729.65    23.1  728.41    38.7  731.06
    46.4  729.83      68  728.47    92.7  725.86   126.4  725.36   155.2  723.27
   174.9  723.87   181.1  722.51   188.1  718.44   192.6  717.33     207  717.21
   218.5  718.53     233  719.94   247.5  720.01   264.6   721.2   270.3  722.01
   273.2  723.26     291  736.76   305.6  746.54   339.4  773.98     351  786.17
   368.2  809.86   373.1  814.54   392.4  826.65   411.7  835.58   433.9  849.82
#Mann= 5, -1 ,  0
       0     0.1       0   91.48    0.06       0   188.1   0.045       0
   218.5    0.06       0  311.48     0.1       0
#XS Ineff= 2 , 0
          172.18  733.12
Permanent Ineff=
       F       F
Bank Sta=188.1,218.5
XS Rating Curve= 0 ,0
Exp/Cntr(USF)=0,0
Exp/Cntr=0.3,0.1

Type RM Length L Ch R = 1 ,16723   ,238.9,240,243.2
XS GIS Cut Line= 4
1605162.85674186 433981.219457441605291.78335003433955.434135806
1605517.90078589434038.7405595451605658.72831173434044.691018383
#Sta/Elev= 30
       0  757.95    25.8  744.79    42.1  738.45    54.3  730.65    58.4  729.31
    66.2   729.3    82.9  732.03   136.1  731.45   148.9  729.69   170.2  723.86
   229.9   718.4   244.7  715.63   251.2  714.43   272.5  714.16   282.1  714.47
   286.5715.5497   293.8  719.42   306.6  723.09   327.9  731.65   336.4  735.88
   366.3  743.18   382.7  743.98   410.7  751.92   438.7  757.06   454.7  763.19
   470.8  765.48   482.8  773.56   486.8  775.34   498.8  778.07   513.4  785.86
#Mann= 5, -1 ,  0
       0     0.1       0  171.48    0.06       0  191.48     0.1       0
   244.7   0.045       0   286.5     0.1       0
Bank Sta=244.7,286.5
XS Rating Curve= 0 ,0
Exp/Cntr(USF)=0,0
Exp/Cntr=0.3,0.1

Type RM Length L Ch R = 1 ,16483   ,230.8,229.7,229.7
XS GIS Cut Line= 4
1605155.29487893434154.3293880871605222.77308216 434175.21549861
1605423.60106796434271.6129317931605545.70448332434324.631520044
#Sta/Elev= 30
       0  756.08    21.8  742.77    30.2  739.08    53.6  730.97    76.6  725.66
    85.4  722.68    89.9  721.85   125.4  717.57   138.4  717.29   144.6  713.52
   147.6  711.97   162.6  711.47   169.7  711.82   177.3713.5475     183  714.04
   204.5  712.48   212.3  712.78   214.1  713.16   222.5  718.66   225.5  719.45
   258.4  724.67   282.5  727.18     294  729.06   312.7   733.5   337.1  741.21
   346.3   741.8   359.4  744.16   379.6  750.02     403  763.05   426.5  772.77
#Mann= 7, -1 ,  0
       0     0.1       0  100.64    0.06       0   144.6   0.045       0
   177.3    0.06       0  210.64     0.1       0  280.64    0.06       0
   323.4     0.1       0
Bank Sta=144.6,177.3
XS Rating Curve= 0 ,0
Exp/Cntr(USF)=0,0
Exp/Cntr=0.3,0.1

Type RM Length L Ch R = 1 ,16254   ,214.2,216,218
XS GIS Cut Line= 2
1605042.83120688434350.3375022261605389.86196634434502.966771433
#Sta/Elev= 30
       0  785.48    35.3  771.98    40.7  769.06    45.1  765.05    53.8  755.02
    66.9  741.79    84.4  726.57    88.8  724.13   104.8  718.61     115  716.49
   136.9  715.59   154.3  713.94   166.5  715.55   171.8  715.54   176.2  713.98
   181.7  710.85   184.7  710.13   187.8  710.08     209  710.27   215.1  710.88
   228.6  713.59   233.3  713.93   241.7  715.57   246.1  716.97   263.4  725.23
   272.3  728.11   287.9  731.47   298.5  732.83     316  734.16   379.1  738.19
#Mann= 6, -1 ,  0
       0     0.1       0   181.7   0.045       0   215.1     0.1       0
     230    0.07       0     280    0.06       0     340     0.1       0
Bank Sta=181.7,215.1
XS Rating Curve= 0 ,0
Exp/Cntr(USF)=0,0
Exp/Cntr=0.3,0.1

Type RM Length L Ch R = 1 ,16038   ,370.1,368.8,366.7
XS GIS Cut Line= 4
1604964.51279451434541.5373737831605024.37560052434561.057854003
1605154.51213532434637.838409534 1605259.9227285434644.345236274
#Sta/Elev= 30
       0   771.8    12.2  761.87    33.2     747    37.4  743.47    43.3  739.28
    49.7   735.6    54.3  733.54    62.7  730.23    71.2  727.46    76.6  725.11
    90.5  716.99    99.8  714.57     115  712.47   120.8  711.33   123.7  711.18
   132.3  712.83     137  712.84   144.2  711.98   158.8  709.12   164.8  708.46
   176.3  708.32   185.1   708.6   188.5709.1169   192.7  711.89   197.3  716.31
     202   719.2   203.6  719.64   255.7  727.19   299.8  730.92   319.7  731.65
#Mann= 5, -1 ,  0
       0     0.1       0  102.97    0.06       0   158.8   0.045       0
   188.5    0.06       0  314.06     0.1       0
Bank Sta=158.8,188.5
XS Rating Curve= 0 ,0
Exp/Cntr(USF)=0,0
Exp/Cntr=0.3,0.1

Type RM Length L Ch R = 1 ,15669   ,251.3,254.5,256.7
XS GIS Cut Line= 2
1604810.94704188434871.3703689431605097.24741844435000.060942243
#Sta/Elev= 30
       0  805.41     2.8   802.3     5.7   799.8    23.2   789.3      29  786.74
    41.9  782.46    49.5  779.27    53.9  777.05    58.3   774.1    61.4  770.17
    67.1  761.85    71.4  754.94    75.8  749.17    84.6  739.39      89  734.77
    92.5  731.61   101.6     724   110.9  717.35   119.7  712.45   122.8  711.09
   132.8  708.14   139.4  706.98     146  706.64   189.9  707.16     198  708.14
   210.5   712.6   216.2  715.47   220.6  716.59     268  718.78   313.9  719.44
#Mann= 4, -1 ,  0
       0     0.1       0   132.8   0.045       0     198     0.1       0
     200    0.06       0
Bank Sta=132.8,198
XS Rating Curve= 0 ,0
Exp/Cntr(USF)=0,0
Exp/Cntr=0.3,0.1

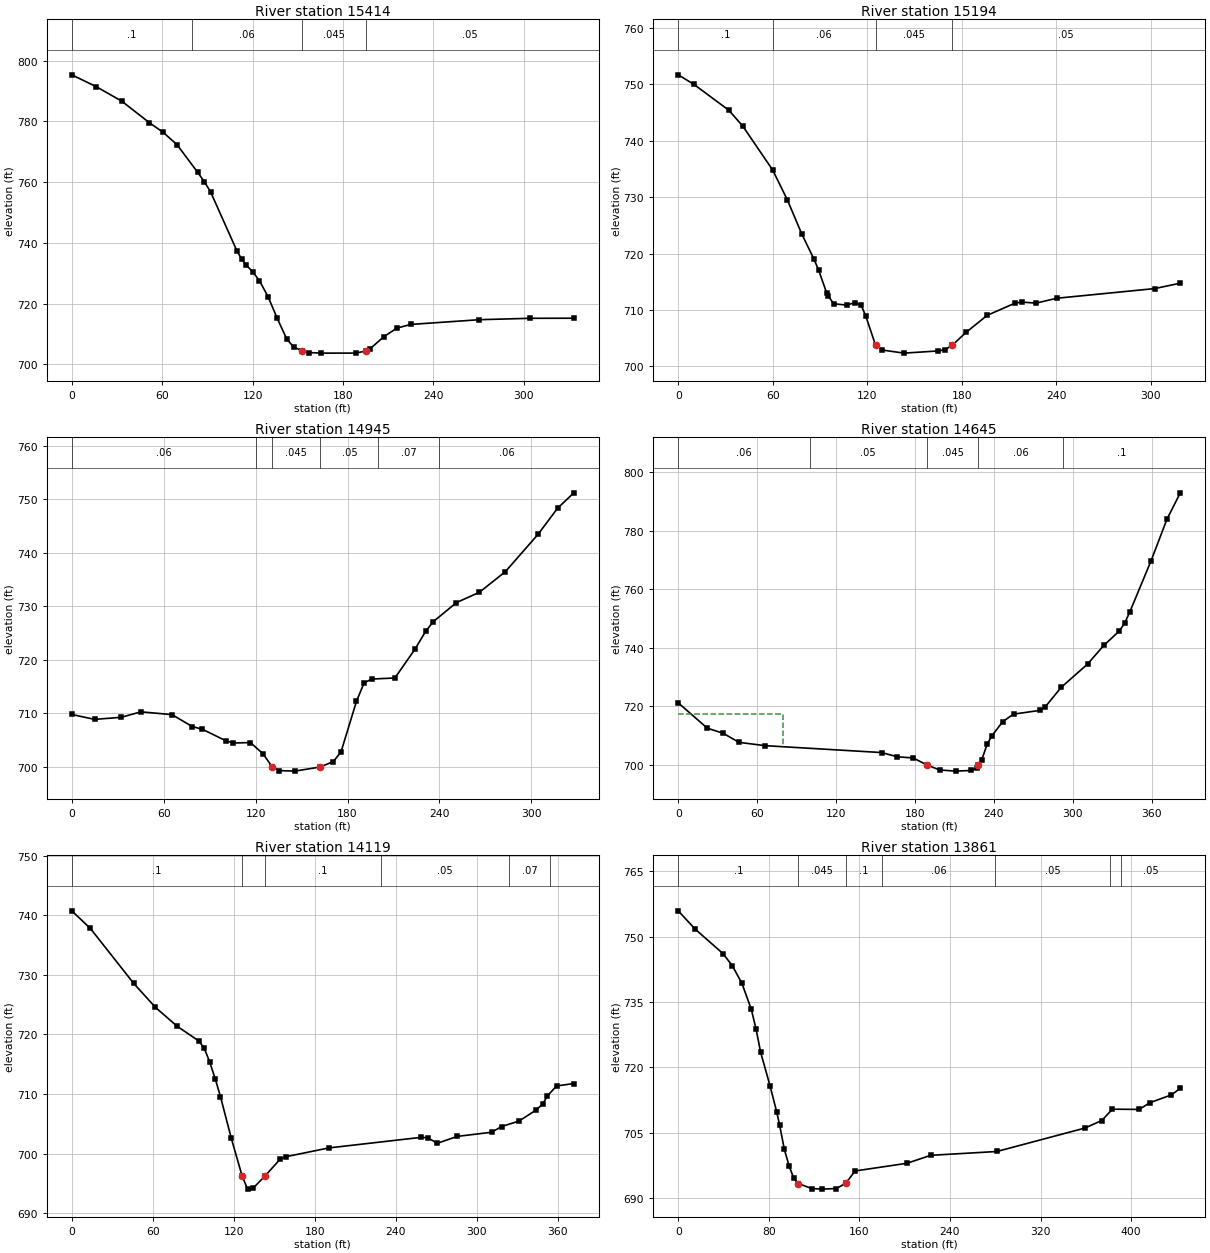
Type RM Length L Ch R = 1 ,15414   ,221.3,219.9,218.8
XS GIS Cut Line= 2
1604690.93223757435076.6969016231604983.01646012435237.198627874
#Sta/Elev= 30
       0  795.32    16.3  791.41    33.2  786.64    51.6  779.52    60.7  776.36
    69.8  772.35    83.5  763.27    88.1  760.04    92.1  756.82   109.7  737.26
   112.7  734.72   115.6  732.76     120  730.49   124.6  727.52   130.4  722.15
   136.2  715.32   142.8  708.21   147.4  705.63     153704.4121   157.5  703.85
   165.7  703.66   188.5  703.67   195.2  704.36   198.1  705.12   207.3  709.12
   215.8  711.89     225  713.11   270.6  714.67   304.1  715.13   333.3  715.16
#Mann= 4, -1 ,  0
       0     0.1       0      80    0.06       0     153   0.045       0
   195.2    0.05       0
Bank Sta=153,195.2
XS Rating Curve= 0 ,0
Exp/Cntr(USF)=0,0
Exp/Cntr=0.3,0.1

Type RM Length L Ch R = 1 ,15194   ,240.1,249.5,255.4
XS GIS Cut Line= 2
 1604607.0664707 435290.699203291604894.81280875435428.065545577
#Sta/Elev= 30
       0  751.69      10  749.99    32.2   745.4    41.1  742.56      60  734.81
    69.3  729.53    78.5  723.45    86.2  719.03    89.2  717.05    94.2  713.09
    95.2  712.54    98.7  711.11   107.2  710.87     112  711.31   116.2  710.85
   119.2  708.87   125.3  703.79   129.7   702.9   143.5  702.36   165.2  702.75
   169.6  702.99     174  703.75   182.9  706.06   196.2  709.05   213.9  711.22
   218.3  711.41   227.2  711.22   240.5  712.09   302.6   713.8   318.9  714.76
#Mann= 4, -1 ,  0
       0     0.1       0      60    0.06       0   125.3   0.045       0
     174    0.05       0
Bank Sta=125.3,174
XS Rating Curve= 0 ,0
Exp/Cntr(USF)=0,0
Exp/Cntr=0.3,0.1

Type RM Length L Ch R = 1 ,14945   ,289.4,300.1,308.8
XS GIS Cut Line= 3
 1604540.5522418435452.6468910381604701.05396805 435663.75726971
1604722.27408787435722.510663682
#Sta/Elev= 30
       0   709.8    14.9  708.88    32.3  709.27    45.1  710.29    65.4  709.77
    78.6  707.55    85.3  707.03   100.4  704.91   105.4  704.47   116.6  704.55
   124.9  702.44   130.9  699.98   135.5  699.32   145.6  699.22   162.3     700
   170.7  701.01   175.7  702.78   185.8  712.23   190.8   715.7   195.8  716.41
   210.9  716.61     224  721.98     231  725.34     236  727.14   251.1  730.69
     266   732.6     283  736.46   304.3  743.42   317.1  748.31   327.7  751.18
#Mann= 6, -1 ,  0
       0    0.06       0     120    0.05       0   130.9   0.045       0
   162.3    0.05       0     200    0.07       0     240    0.06       0
Bank Sta=130.9,162.3
XS Rating Curve= 0 ,0
Exp/Cntr(USF)=0,0
Exp/Cntr=0.3,0.1

Type RM Length L Ch R = 1 ,14645   ,522.1,526.1,529.7
XS GIS Cut Line= 3
1604331.45070321435450.5320702151604356.17664482435742.037908161
1604366.58756761435830.530751824
#Sta/Elev= 30
       0   721.2    22.1  712.54    34.1  710.82    46.2   707.7    66.2  706.57
   154.6  704.22   166.6  702.77   178.6  702.38   188.9700.0169   198.7  698.28
   210.8  697.88   222.8  698.11   226.8  698.86   228.2  699.93   230.8  701.81
   234.8  707.02   238.3  709.85   246.7  714.78   254.9  717.34     275  718.62
     279  719.81   291.1  726.46   311.2  734.44   323.6  740.82   335.3  745.71
   339.4   748.4   343.4  752.33   359.4  769.63   371.6  783.94   381.7   792.9
#Mann= 5, -1 ,  0
       0    0.06       0     100    0.05       0   188.9   0.045       0
   228.2    0.06       0  292.55     0.1       0
#XS Ineff= 2 , 0
           79.84  717.38
Permanent Ineff=
       F       F
Bank Sta=188.9,228.2
XS Rating Curve= 0 ,0
Exp/Cntr(USF)=0,0
Exp/Cntr=0.3,0.1

Type RM Length L Ch R = 1 ,14119   ,259.7,257.2,254.4
XS GIS Cut Line= 4
1603848.33150469435418.8178789981603839.22194725435517.721645444
1603861.34515817435741.5564852961603879.56427304435785.802907127
#Sta/Elev= 30
       0  740.74    13.8  737.78    45.9  728.56      62  724.54      78  721.38
    94.1   718.9    98.1  717.71   102.2  715.37   106.4  712.48   110.2  709.55
   118.2  702.58   126.3  696.19   130.3  694.02   134.3  694.16     143  696.17
   154.4  699.04   158.4  699.45   190.6  700.94   258.9  702.71   263.7  702.64
     271  701.72   285.6  702.87   311.2  703.57   318.5  704.52   331.5  705.45
     344  707.28   349.1  708.32   352.5  709.67   359.3  711.34   372.1  711.75
#Mann= 6, -1 ,  0
       0     0.1       0   126.3   0.045       0     143     0.1       0
  229.32    0.05       0  324.25    0.07       0  354.25    0.06       0
Bank Sta=126.3,143
XS Rating Curve= 0 ,0
Exp/Cntr(USF)=0,0
Exp/Cntr=0.3,0.1

Type RM Length L Ch R = 1 ,13861   ,352.4,347.4,343.2
XS GIS Cut Line= 3
1603555.52430139435478.6806850051603649.22260645435796.213829911
1603709.08541245435891.213500313
#Sta/Elev= 30
       0  755.95    14.9  751.76    39.5  746.14    47.8  743.33    56.2  739.33
    64.5  733.36    68.7  728.84    72.8  723.46    81.2  715.65    86.9  709.84
    89.5  706.83    93.7  701.18    97.9   697.4     102  694.57   106.2  693.33
   117.9  692.19   127.1  692.06   139.6   692.2   147.9  693.38   156.2  696.23
   202.1     698     223  699.82   281.4   700.7     359  706.07     374  707.81
   383.5  710.41   407.1  710.36   416.6  711.91   435.5  713.69   443.4   715.2
#Mann= 7, -1 ,  0
       0     0.1       0   106.2   0.045       0   147.9     0.1       0
     180    0.06       0     280    0.05       0  381.07    0.07       0
  391.07    0.05       0
Bank Sta=106.2,147.9
XS Rating Curve= 0 ,0
Exp/Cntr(USF)=0,0
Exp/Cntr=0.3,0.1

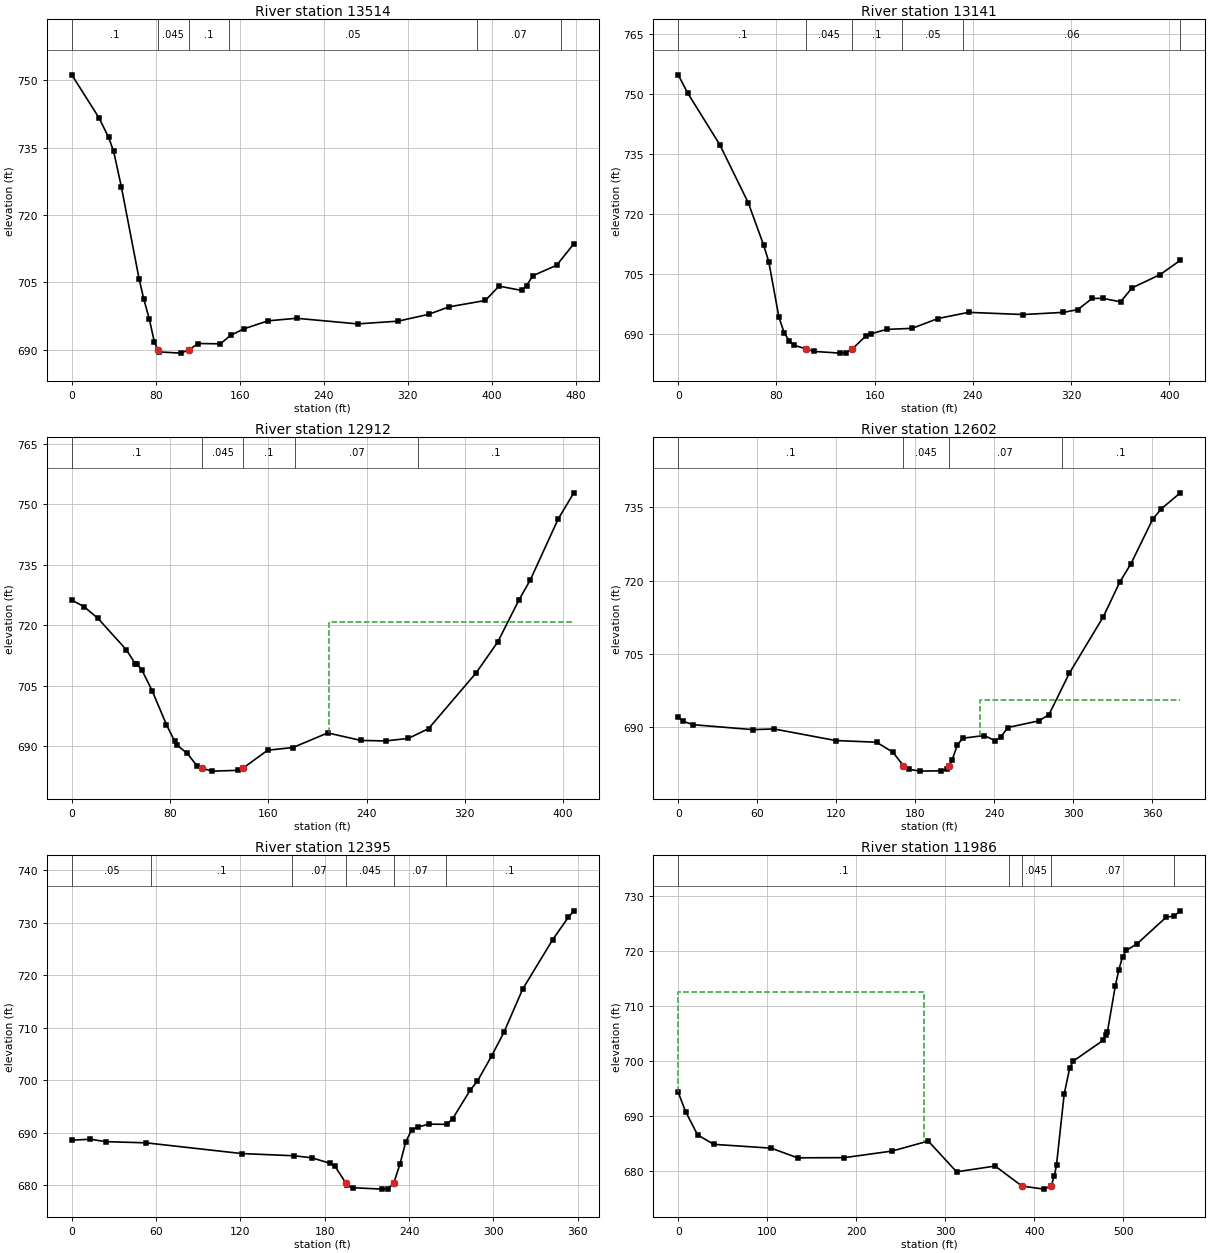
Type RM Length L Ch R = 1 ,13514   ,383.8,372.8,362.1
XS GIS Cut Line= 3
1603205.61620668435623.4944091421603410.94273937435925.700362172
1603486.13273725436009.566129041
#Sta/Elev= 30
       0  751.23    25.8   741.7    35.1  737.29    39.9  734.16    47.2   726.3
    64.1  705.79    68.5  701.34    73.8  696.84    78.6   691.8    81.9690.0233
    83.5  689.52   104.1  689.26   111.2  690.01   120.6   691.4   141.5  691.33
   151.2  693.22   163.8  694.66   186.8  696.45     214  697.02   272.1  695.77
   310.7  696.38   339.8   697.9   359.1  699.56   393.7  700.98   406.8  704.18
   428.3  703.21     433   704.3     439   706.5   461.7  708.84     478  713.62
#Mann= 6, -1 ,  0
       0     0.1       0    81.9   0.045       0   111.2     0.1       0
     150    0.05       0  385.36    0.07       0  465.36    0.06       0
Bank Sta=81.9,111.2
XS Rating Curve= 0 ,0
Exp/Cntr(USF)=0,0
Exp/Cntr=0.3,0.1

Type RM Length L Ch R = 1 ,13141   ,230.5,229.3,227.8
XS GIS Cut Line= 4
1602976.61060177435967.0611470721603006.02015727 435997.41939791
1603207.14356907436057.1872042461603341.86981317436137.276860119
#Sta/Elev= 30
       0  754.73     7.6  750.23    33.8   737.3      57   722.8    69.5  712.26
    73.7   708.1      82   694.2    86.2   690.4    90.4  688.28    94.5  687.21
   104.4  686.29   110.8  685.68   132.1  685.26   136.3  685.34   141.7  686.28
   152.9  689.59   157.1  690.09   169.6  691.18   190.5  691.45   211.4  693.89
   236.4  695.44   281.1  694.89   313.6  695.44   325.3  696.11     337  698.91
   345.7  698.94   360.2  698.06   369.5  701.54   392.4  704.87   408.8  708.42
#Mann= 6, -1 ,  0
       0     0.1       0   104.4   0.045       0   141.7     0.1       0
  182.27    0.05       0  232.27    0.06       0  408.82     0.1       0
Bank Sta=104.4,141.7
XS Rating Curve= 0 ,0
Exp/Cntr(USF)=0,0
Exp/Cntr=0.3,0.1

Type RM Length L Ch R = 1 ,12912   ,309.9,309.7,310.2
XS GIS Cut Line= 4
1602940.77147097436179.2648844731602958.69127181436227.753757338
1603227.48828444 436285.72958359 1603299.1674878436325.785609001
#Sta/Elev= 30
       0   726.2     9.9  724.63    21.2  721.72    44.3  713.94    51.7  710.43
    53.1  710.38    57.2  708.79    65.4  703.75    77.1  695.28    83.8  691.15
    85.9  690.17    94.1  688.13   102.3  684.93   106.3  684.43   114.5  683.75
     135  683.94   139.1  684.41   159.5  688.95     180   689.6   208.4  693.24
   235.3  691.38   255.5  691.24   274.1  691.89   290.5   694.3   329.2  708.14
   346.8  715.81     364  726.19   373.4  731.27   396.1  746.41   408.8  752.87
#Mann= 5, -1 ,  0
       0     0.1       0   106.3   0.045       0   139.1     0.1       0
  181.69    0.07       0  281.69     0.1       0
#XS Ineff= 2 , 0
                          209.56          720.83
Permanent Ineff=
       F       F
Bank Sta=106.3,139.1
XS Rating Curve= 0 ,0
Exp/Cntr(USF)=0,0
Exp/Cntr=0.3,0.1

Type RM Length L Ch R = 1 ,12602   ,205.9,207.1,208.4
XS GIS Cut Line= 4
 1602825.5497077436478.1615136211602845.46059752436519.154522083
1603085.56250422436571.859818676 1603172.2334364436596.455623753
#Sta/Elev= 30
       0  692.15     3.7  691.24    11.5  690.55    56.5  689.55    72.9  689.68
   119.5  687.32   150.7  686.97     163  684.95   171.1  682.18   175.2  681.46
   183.4  681.06   199.8  681.13   203.9  681.42   205.6682.1586     208  683.26
   212.1  686.41   216.2  687.79   232.6  688.34   240.8  687.27   244.9  687.94
   250.4  689.98     274  691.34   281.7  692.61   297.2  701.09   323.1  712.68
   335.6  719.78   343.9  723.42   360.6  732.61   367.1  734.71   381.5  737.97
#Mann= 4, -1 ,  0
       0     0.1       0   171.1   0.045       0   205.6    0.07       0
  291.39     0.1       0
#XS Ineff= 2 , 0
                          228.99          695.57
Permanent Ineff=
       F       F
Bank Sta=171.1,205.6
XS Rating Curve= 0 ,0
Exp/Cntr(USF)=0,0
Exp/Cntr=0.3,0.1

Type RM Length L Ch R = 1 ,12395   ,399.4,409.5,423
XS GIS Cut Line= 4
1602756.73054319436662.0017616071602790.46193301436707.328316677
1603012.87828463436773.7369903841603070.85411088436810.630697999
#Sta/Elev= 30
       0  688.53    13.1  688.72    24.2  688.26      53  688.03   120.8  685.99
   158.5  685.56   170.9  685.17   183.5  684.15   187.4  683.53   194.9  680.41
     196  679.99   200.2  679.47     221   679.2   225.2  679.26   229.2  680.41
   233.6  684.02   237.7  688.24   241.9   690.5   246.1  691.05   254.4   691.6
   266.9  691.56     271  692.61   283.6  698.11   288.6  699.77   298.8  704.62
   307.5   709.1   320.9  717.37   342.2  726.78   353.4  731.07   357.3   732.3
#Mann= 6, -1 ,  0
       0    0.05       0    56.5     0.1       0   156.5    0.07       0
   194.9   0.045       0   229.2    0.07       0   266.5     0.1       0
Bank Sta=194.9,229.2
XS Rating Curve= 0 ,0
Exp/Cntr(USF)=0,0
Exp/Cntr=0.3,0.1

Type RM Length L Ch R = 1 ,11986   ,394.9,403.6,417.5
XS GIS Cut Line= 4
1602496.85109644436745.247300251 1602525.7703264436799.872512388
1602757.12416604437156.543015167 1602773.1904049437232.054337827
#Sta/Elev= 30
       0  694.28     8.2  690.77    21.8  686.51    39.9  684.79   104.5  684.09
   134.1  682.33   186.6  682.36   240.4  683.57   280.9  685.39   312.7  679.78
   356.1  680.83     386677.1945   410.6  676.62   418.9  677.19   422.6  679.05
     425  681.04   433.6  693.93   439.9  698.75     444  699.99   477.4  703.76
   480.4  704.65   482.2  705.31     491  713.62   495.1  716.67   499.2     719
   503.3  720.15   515.6  721.37   548.3  726.24   556.9   726.4   564.1  727.38
#Mann= 5, -1 ,  0
       0     0.1       0  371.81    0.07       0     386   0.045       0
   418.9    0.07       0  556.94    0.05       0
#XS Ineff= 2 , 0
          275.63   712.6
Permanent Ineff=
       F       F
Bank Sta=386,418.9
XS Rating Curve= 0 ,0
Exp/Cntr(USF)=0,0
Exp/Cntr=0.3,0.1