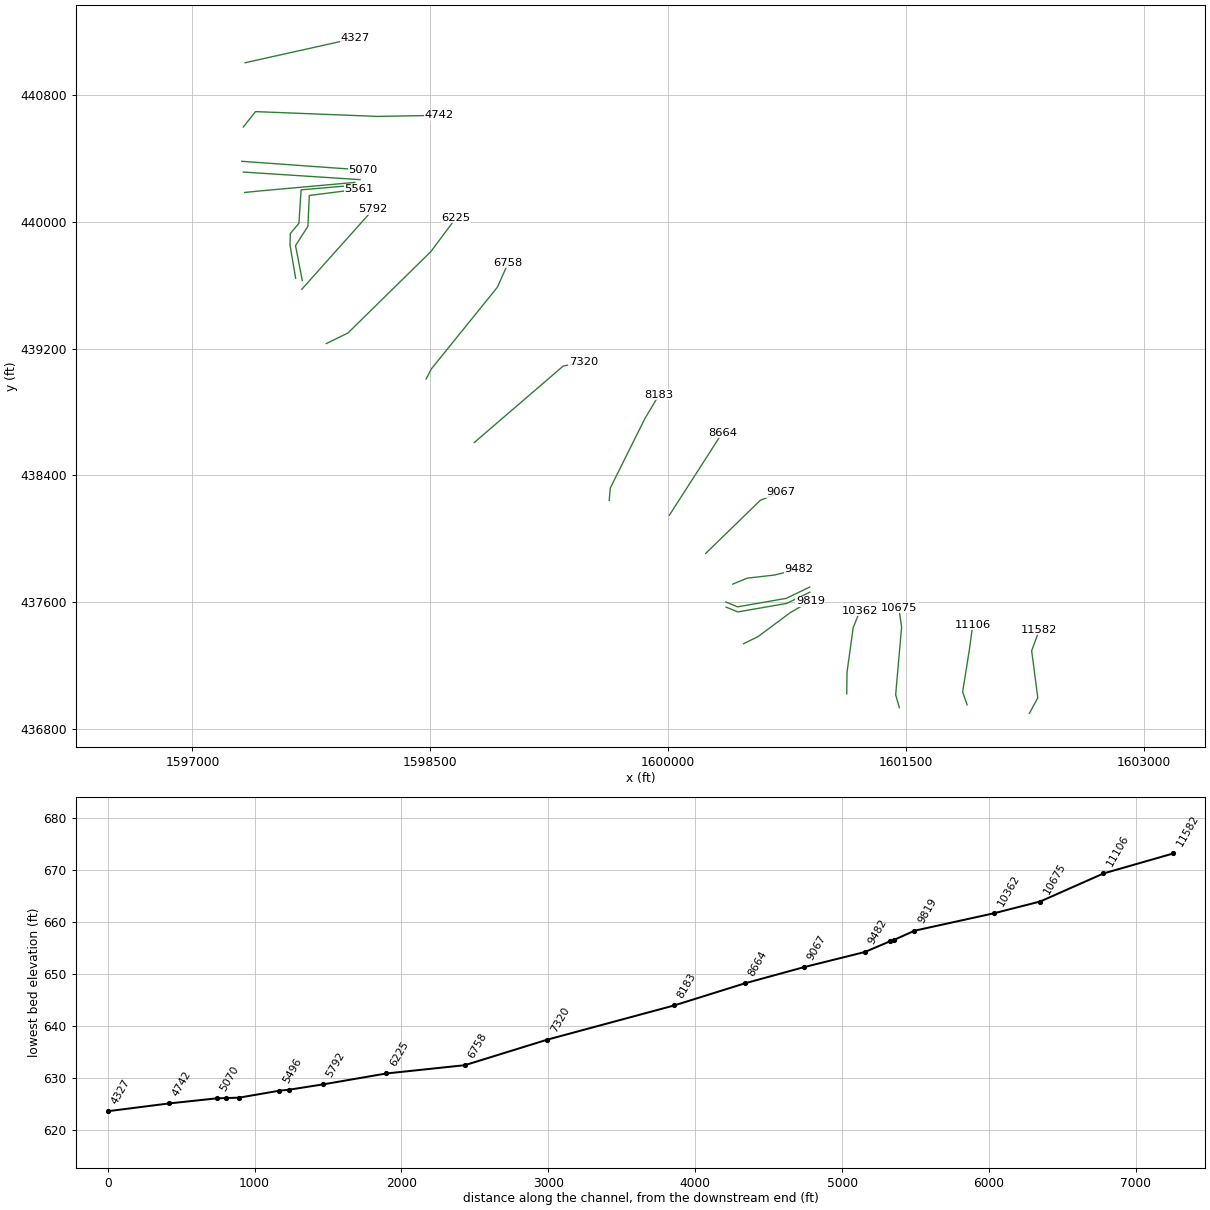
HEC-RAS study PROCTRCK.prj: PROCTRCK

--- PROCTRCK.g01 (geometry) --- (continued)

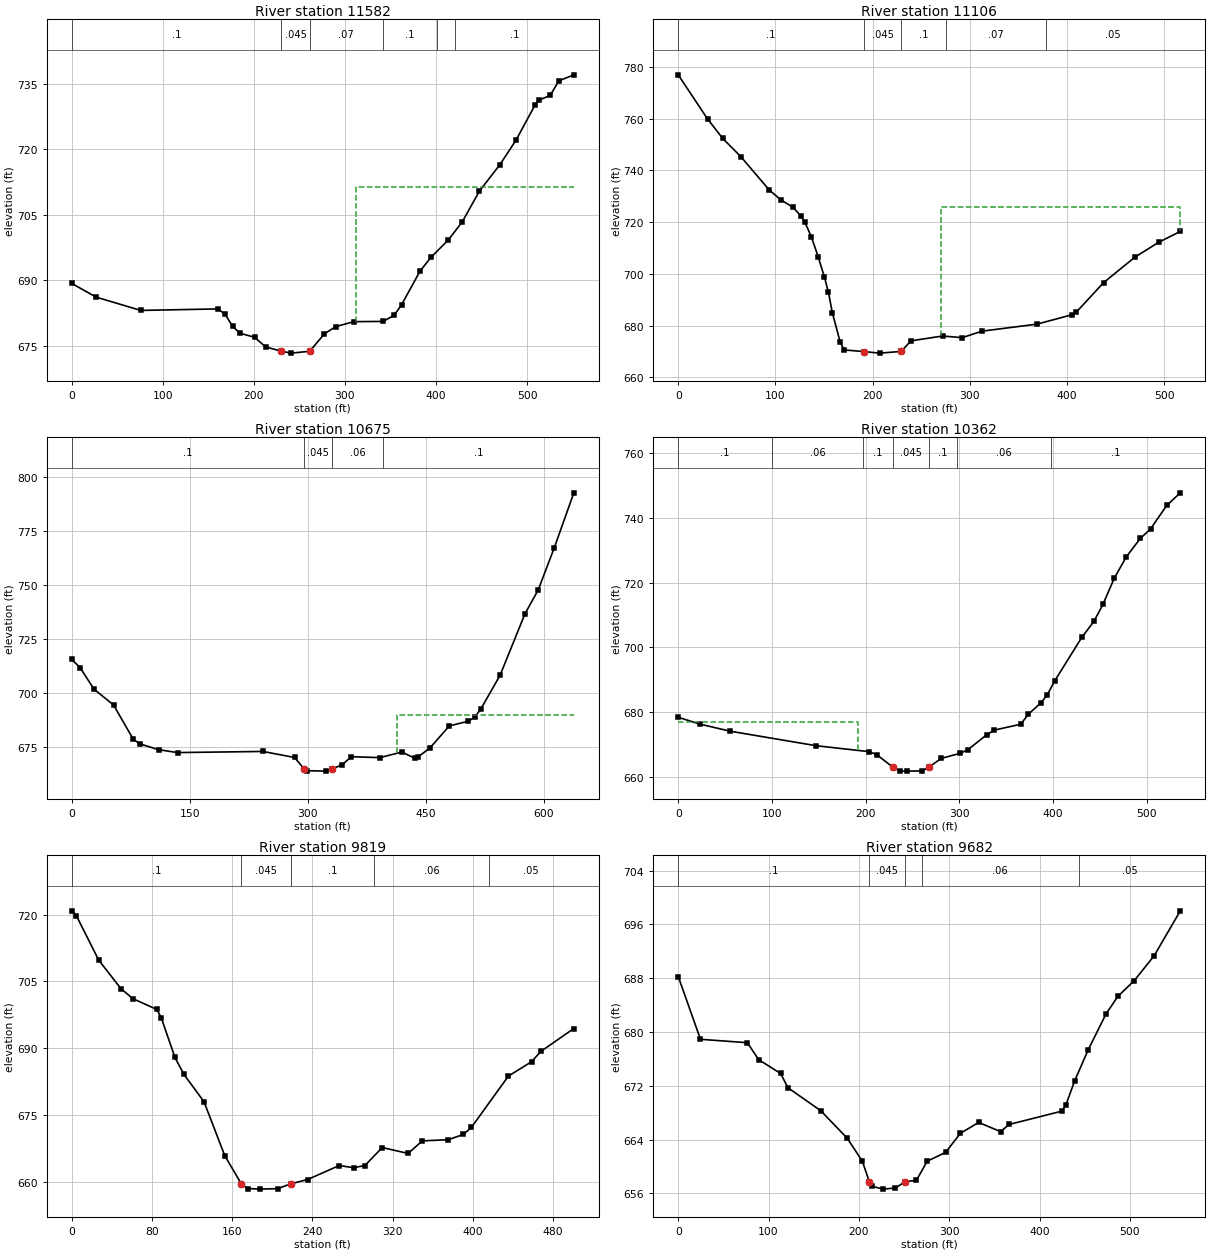
Type RM Length L Ch R = 1 ,11582   ,478.7,476.2,469.5
XS GIS Cut Line= 4
1602278.35024789436897.8765694581602331.36883614436995.880626527
1602292.80986287 437293.106045511602341.00857946437424.849204194
#Sta/Elev= 30
       0  689.25    26.9   686.1    75.8  683.06   160.5  683.41   168.6  682.13
   176.6  679.41   184.7  677.84   200.8  676.89   212.9  674.68   230.2673.7051
   241.2  673.26   261.3  673.69   277.5   677.7   289.9  679.34   309.7  680.48
     342  680.54   354.1  681.96   362.2  684.36   382.3  692.02   394.4  695.24
   413.3  699.17   428.9   703.4   447.6  710.42   470.2  716.51   488.1  722.21
   508.5  730.11   512.8  731.29   525.5  732.41   534.9  735.75   551.4  737.13
#Mann= 6, -1 ,  0
       0     0.1       0   230.2   0.045       0   261.3    0.07       0
  341.43     0.1       0  401.43    0.05       0  421.14     0.1       0
#XS Ineff= 2 , 0
                          311.86          711.32
Permanent Ineff=
       F       F
Bank Sta=230.2,261.3
XS Rating Curve= 0 ,0
Exp/Cntr(USF)=0,0
Exp/Cntr=0.3,0.1

Type RM Length L Ch R = 1 ,11106   ,430.2,431.1,432.6
XS GIS Cut Line= 4
1601885.87781777436951.7568723031601857.31561535437032.088066623
1601900.15891898437301.643852006 1601921.5805708437458.735965342
#Sta/Elev= 30
       0  776.97    30.2  759.89    45.8  752.38    64.5  745.31    93.8  732.41
     106  728.53   118.1  725.79   126.2  722.41   130.3  719.98     137  714.38
     144  706.65   150.5  698.75   154.6  692.85   158.6     685   166.7  673.61
   170.8  670.64     191     670   207.2   669.4   229.3670.0423   239.6  674.15
     272  676.02   292.3  675.38   312.5  677.89   369.2   680.6   405.5  684.26
   409.6  685.22   437.8  696.67   470.1  706.53   494.3  712.21   516.7  716.44
#Mann= 5, -1 ,  0
       0     0.1       0     191   0.045       0   229.3     0.1       0
  275.26    0.07       0   378.2    0.05       0
#XS Ineff= 2 , 0
                          270.88          726.04
Permanent Ineff=
       F       F
Bank Sta=191,229.3
XS Rating Curve= 0 ,0
Exp/Cntr(USF)=0,0
Exp/Cntr=0.3,0.1

Type RM Length L Ch R = 1 ,10675   ,313.5,312.8,311.5
XS GIS Cut Line= 4
1601458.19409844436933.4426823231601434.98730897437015.559014294
1601472.47519965437442.2069130131601454.62382313 437565.38141097
#Sta/Elev= 30
       0  715.64    10.7  711.82    28.2  701.91    53.1  694.59      78  678.84
    86.3  676.63   110.4  673.91   134.5  672.58   242.9   673.1   283.1  670.31
   295.1  665.13   299.1   664.2   323.2     664   331.3  665.14   343.3  666.85
   355.3  670.68   391.5  670.24   419.6  672.84   435.7  669.97   439.7  670.49
     455  674.62   479.8   684.9   503.9  687.09   512.2  688.94     520  692.83
   544.3  708.29     576  736.77   592.8  747.79     613  767.07   638.1   792.7
#Mann= 4, -1 ,  0
       0     0.1       0   295.1   0.045       0   331.3    0.06       0
  395.33     0.1       0
#XS Ineff= 2 , 0
                          413.33          689.91
Permanent Ineff=
       F       F
Bank Sta=295.1,331.3
XS Rating Curve= 0 ,0
Exp/Cntr(USF)=0,0
Exp/Cntr=0.3,0.1

Type RM Length L Ch R = 1 ,10362   ,560.8,542.8,523.4
XS GIS Cut Line= 4
1601126.50870232437021.1636862141601128.29383998437158.619285383
1601167.56686831437440.6710343271601210.41017195437545.994155768
#Sta/Elev= 30
       0  678.39    23.4  676.26    55.4  674.09   147.5  669.59     204  667.76
   212.1   666.8   229.1  662.96   236.3  661.78   244.4  661.75   260.6  661.81
  267.42  662.97   280.8  665.69   300.9  667.26   309.2  668.37   329.2  672.98
   337.5  674.44   365.6  676.24   373.6  679.32   387.2  682.86   393.8   685.3
   401.9  689.67   430.7  703.07   443.7  708.04   453.3  713.25   465.3   721.3
   478.2  727.95   493.2  733.67   504.1  736.58   521.4  743.86   535.9  747.76
#Mann= 7, -1 ,  0
       0     0.1       0     100    0.06       0  197.47     0.1       0
   229.1   0.045       0  267.42     0.1       0  297.47    0.06       0
  397.47     0.1       0
#XS Ineff= 2 , 0
          191.76  676.91
Permanent Ineff=
       F       F
Bank Sta=229.1,267.42
XS Rating Curve= 0 ,0
Exp/Cntr(USF)=0,0
Exp/Cntr=0.3,0.1

Type RM Length L Ch R = 1 ,9819    ,148.9,137.5,128
XS GIS Cut Line= 4
1600475.93567455 437337.543788251600567.03124891 437382.36859468
1600770.91182009437534.194551944 1600896.7104704437606.492626832
#Sta/Elev= 30
       0  720.84     4.7  719.69    26.9  709.77    49.2  703.33    61.1  701.11
    84.9   698.7    89.4  696.76   102.9  687.93   111.9  684.12   131.9  677.99
   152.7  665.84  169.15  659.58   175.3  658.52   187.7  658.38   205.6  658.49
   218.2  659.56   235.3  660.54   266.8  663.68   281.1  663.18   292.4  663.68
   309.7  667.72   335.4  666.39   349.7  669.21   375.6  669.47   390.6  670.66
   398.6  672.23   435.5  683.74   458.6  686.97   467.8  689.27   500.8  694.43
#Mann= 5, -1 ,  0
       0     0.1       0  169.15   0.045       0   218.2     0.1       0
  301.53    0.06       0  415.73    0.05       0
Bank Sta=169.15,218.2
XS Rating Curve= 0 ,0
Exp/Cntr(USF)=0,0
Exp/Cntr=0.3,0.1

Type RM Length L Ch R = 1 ,9682    ,32.9,32.3,33.4
XS GIS Cut Line= 4
1600365.42564554437568.7846119271600439.16182596437538.102143216
1600747.80290388437591.9784888841600894.13748012437662.963951606
#Sta/Elev= 30
       0  688.26    24.6  678.92    76.6  678.41      89  675.89   113.3  673.84
   121.4  671.72     158  668.27   187.1  664.19   203.8  660.79  211.48  657.75
   214.8  657.05     227  656.63   240.4   656.8   251.4  657.76   263.6  657.92
   275.7   660.8     296  662.09   312.3  664.93   332.6  666.55   356.9  665.18
   366.3  666.25   424.6  668.23   429.1  669.14   438.7  672.69   453.7  677.32
   473.5  682.68   486.6  685.29   504.9  687.66   526.9  691.36   555.8  698.03
#Mann= 5, -1 ,  0
       0     0.1       0  211.48   0.045       0   251.4     0.1       0
  269.87    0.06       0  443.17    0.05       0
Bank Sta=211.48,251.4
XS Rating Curve= 0 ,0
Exp/Cntr(USF)=0,0
Exp/Cntr=0.3,0.1

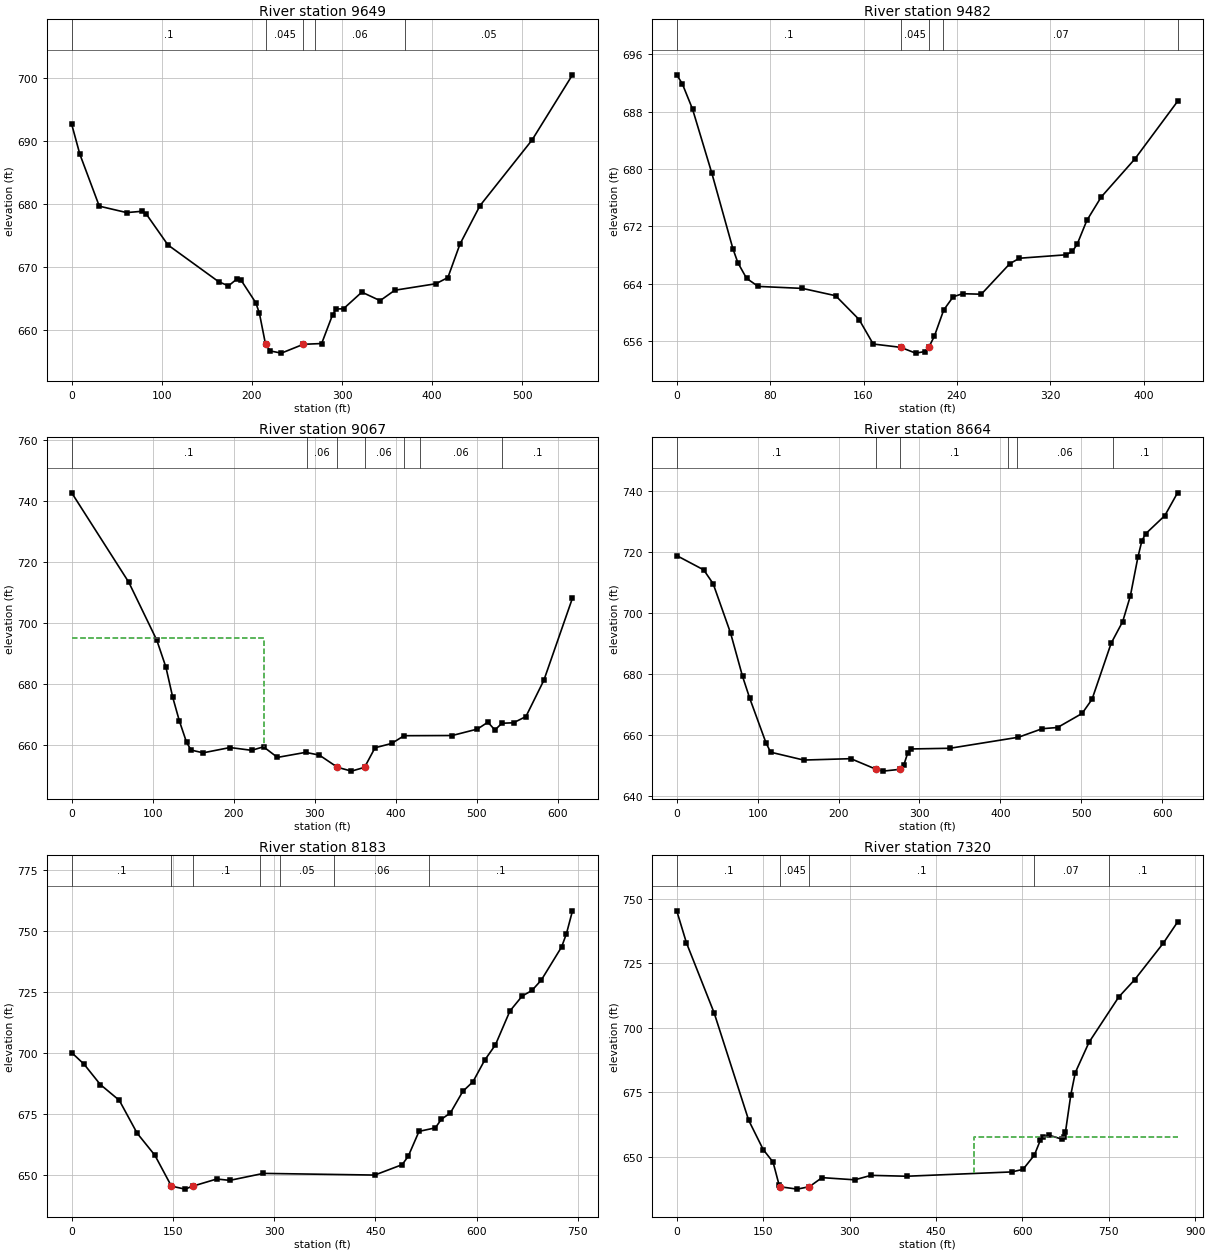
Type RM Length L Ch R = 1 ,9649    ,170.1,166.9,164.2
XS GIS Cut Line= 4
1600363.81937845437600.9100261271600437.55555886437570.227557416
1600746.19663678437624.1039030851600892.53121302437695.089365806
#Sta/Elev= 30
       0  692.58       9  687.86    30.6  679.61      61  678.59    78.3   678.8
    82.5  678.41   106.8  673.46   163.1  667.63     174  666.97     184  668.14
     188  667.87   204.3   664.3   208.3  662.64  215.16  657.69   220.5  656.65
   232.7  656.31   257.1  657.71   277.4  657.83   289.5  662.38   293.6   663.3
   301.7  663.35     322  665.98   342.3  664.63   358.6  666.28   404.2  667.31
   417.5  668.29   430.9  673.59   453.1  679.68   510.9  690.09   555.8  700.43
#Mann= 5, -1 ,  0
       0     0.1       0  215.16   0.045       0   257.1     0.1       0
  269.87    0.06       0  369.87    0.05       0
Bank Sta=215.16,257.1
XS Rating Curve= 0 ,0
Exp/Cntr(USF)=0,0
Exp/Cntr=0.3,0.1

Type RM Length L Ch R = 1 ,9482    ,405.3,415.2,425.9
XS GIS Cut Line= 4
1600407.66264721437713.7525462021600498.70466744437751.240436884
1600670.07788199437770.8769510511600823.59972002437808.364841734
#Sta/Elev= 30
       0  693.12     4.8  691.86    13.5  688.35    30.1  679.37    48.1  668.86
    52.4  666.89    59.8  664.73    69.7   663.6   107.7  663.32   136.1   662.3
   156.2  658.98   168.3  655.56   191.8   655.1   204.6  654.29   212.6  654.51
  215.88   655.1   220.7  656.65   228.7  660.31   236.8  662.15   244.8  662.58
   260.9  662.51   285.4  666.78   293.6  667.53   333.6  668.01   338.9  668.48
     343  669.47   351.3   672.8   363.6  676.07   392.5  681.39     429  689.41
#Mann= 5, -1 ,  0
       0     0.1       0   191.8   0.045       0  215.88     0.1       0
  228.46    0.07       0  428.99    0.08       0
Bank Sta=191.8,215.88
XS Rating Curve= 0 ,0
Exp/Cntr(USF)=0,0
Exp/Cntr=0.3,0.1

Type RM Length L Ch R = 1 ,9067    ,399.4,403,406.9
XS GIS Cut Line= 3
1600236.75087288437907.3995478011600582.17500845438243.183940057
1600708.91978171438294.595904421
#Sta/Elev= 30
       0  742.59    70.5  713.27   105.1  694.29   116.3  685.49   124.8  675.54
     133  667.79   141.8  660.85   147.4  658.28   162.3  657.37   195.5   659.1
   222.3  658.19   236.9  659.34   254.1  655.87   288.9  657.52   305.9  656.62
   328.2  652.63   345.5  651.37   361.7  652.61   374.6  659.02   395.2  660.45
   410.5  662.98   469.9  663.04   501.1  665.16     514  667.41   522.7  664.85
   531.3  667.06   545.7  667.22     561  669.26   583.1  681.12   618.5  708.11
#Mann= 7, -1 ,  0
       0     0.1       0     290    0.06       0   328.2   0.045       0
   361.7    0.06       0     410    0.07       0     430    0.06       0
  531.74     0.1       0
#XS Ineff= 2 , 0
          237.53  695.03
Permanent Ineff=
       F       F
Bank Sta=328.2,361.7
XS Rating Curve= 0 ,0
Exp/Cntr(USF)=0,0
Exp/Cntr=0.3,0.1

Type RM Length L Ch R = 1 ,8664    ,483.4,480.8,485.8
XS GIS Cut Line= 3
 1600007.7994809438148.5410294581600261.28902742 438543.05645045
1600341.62022174 438669.80122371
#Sta/Elev= 30
       0  718.89    33.3  714.22      45  709.68    66.6  693.45    81.3  679.33
    90.3  672.06   110.2   657.6     116  654.46   156.9  651.88   215.2  652.33
   246.2648.8842     255  648.25   276.4648.8569   280.5  650.13   285.3  654.03
     290  655.52   337.6  655.74   422.4  659.36   451.8  662.16   470.7  662.55
     501  667.15   513.3  671.78     537   690.2   551.2  697.26   560.7  705.68
   570.1  718.48   574.9   723.7   579.6  726.05   603.3     732     619  739.47
#Mann= 6, -1 ,  0
       0     0.1       0   246.2   0.045       0   276.4     0.1       0
     410    0.07       0     420    0.06       0  538.93     0.1       0
Bank Sta=246.2,276.4
XS Rating Curve= 0 ,0
Exp/Cntr(USF)=0,0
Exp/Cntr=0.3,0.1

Type RM Length L Ch R = 1 ,8183    ,874,863,851.8
XS GIS Cut Line= 4
1599628.32672191 438242.308506761599635.46727251438320.854563428
  1599853.254066438758.2132880571599942.51094858438908.164850787
#Sta/Elev= 30
       0   700.1    18.3  695.36    42.4     687    70.5  680.51      97  666.97
   123.2  657.94   147.7  645.23   167.9     644     179645.1838   214.9  648.16
   234.2   647.6   284.1  650.47     449  649.78   489.6  654.06   498.6  657.49
   514.6  667.74   538.8  669.19   547.7  672.72   561.1  675.33   579.5  684.19
   594.6  688.17   611.9  697.02   627.8   703.3   649.3  717.23   667.5  723.39
   681.9  725.66   695.8  729.94   725.9  743.57   733.1  749.07     742  758.41
#Mann= 7, -1 ,  0
       0     0.1       0   147.7   0.045       0     179     0.1       0
  278.87    0.08       0  308.87    0.05       0  388.87    0.06       0
  528.87     0.1       0
Bank Sta=147.7,179
XS Rating Curve= 0 ,0
Exp/Cntr(USF)=0,0
Exp/Cntr=0.3,0.1

Type RM Length L Ch R = 1 ,7320    ,558.4,562.1,564.6
XS GIS Cut Line= 3
1598777.45079953438607.4695716851599338.21420448439089.873024847
1599465.54912612439114.360509779
#Sta/Elev= 30
       0  745.36    16.8  732.96      65  705.72   124.9  664.12   150.1  652.77
   167.2   647.9   177.6  639.08   179.5  638.33   209.3  637.42   230.4  638.38
   252.2  641.88     309  641.03   337.3  642.76   399.2  642.42   581.5  644.09
   601.1  645.07   620.9  650.63   631.4   656.5   635.2  657.48   646.5  658.35
   668.3  656.81     672  657.59   674.9  659.65   684.2  674.08   691.9  682.61
   715.8   694.4   767.5  711.98   794.9  718.62   844.7  732.82   869.4     741
#Mann= 5, -1 ,  0
       0     0.1       0   179.5   0.045       0   230.4     0.1       0
     620    0.07       0  749.71     0.1       0
#XS Ineff= 2 , 0
                          515.33          657.52
Permanent Ineff=
       F       F
Bank Sta=179.5,230.4
XS Rating Curve= 0 ,0
Exp/Cntr(USF)=0,0
Exp/Cntr=0.3,0.1

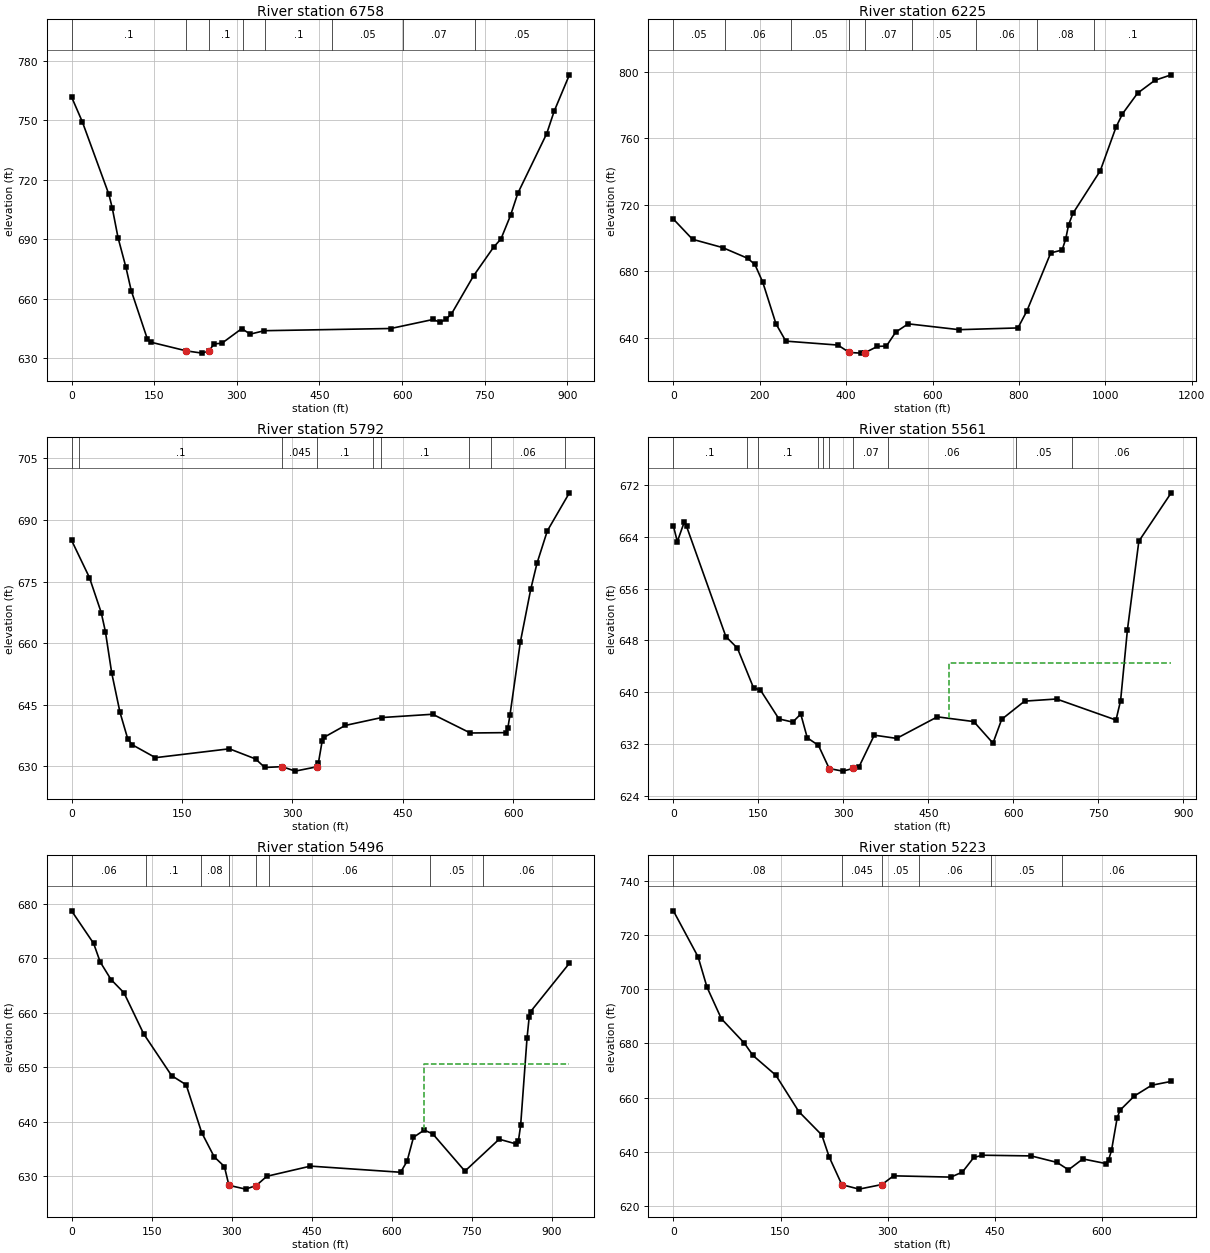
Type RM Length L Ch R = 1 ,6758    ,532.7,533.7,529.1
XS GIS Cut Line= 4
1598473.80598638439008.3297000231598506.86409103439072.242035696
1598923.39620973439587.9484683651598991.71629269439742.219623437
#Sta/Elev= 30
       0   761.7    19.7  749.05    67.8  712.51    73.9  705.67    84.4   690.7
    98.7  675.76   108.3  664.02   137.6  639.61   144.2     638   208.6633.6176
   236.9   632.5   249.4  633.61   258.6  637.13   272.9   637.5   308.9  644.84
   324.3  642.09     350  643.81   579.4  644.92   656.2  649.47   668.8  648.05
   679.1   649.5   689.3  652.14   729.6  671.47   766.1  685.96   779.3  690.03
   796.8  701.98   809.9  713.06   862.4  743.19   875.9  754.46   903.6  772.85
#Mann= 8, -1 ,  0
       0     0.1       0   208.6   0.045       0   249.4     0.1       0
  311.96    0.08       0  351.96     0.1       0  471.96    0.05       0
  601.96    0.07       0  731.96    0.05       0
Bank Sta=208.6,249.4
XS Rating Curve= 0 ,0
Exp/Cntr(USF)=0,0
Exp/Cntr=0.3,0.1

Type RM Length L Ch R = 1 ,6225    ,429.9,432.4,433
XS GIS Cut Line= 4
1597844.33540537439231.8541533671597980.37698833439298.363371701
1598503.38129614439812.298240645 1598663.6080494440026.941627087
#Sta/Elev= 30
       0  711.46    44.3  699.31     114  694.33   171.7  687.92   188.8  684.17
   207.1   673.4   237.6  648.48   260.3  638.12     381  635.75   407.3   631.3
   434.2  630.91   444.1  631.24   472.4  634.95   493.2  635.16   514.8  643.54
   543.6  648.51   661.4     645   797.7  646.05   818.4  656.24   873.6  691.12
     900  692.86   908.2  699.41   914.9  707.95   924.9  714.84   988.3  740.48
  1024.7  766.65  1039.7  774.69  1074.7   787.1  1114.6   794.8  1152.5  798.12
#Mann= 9, -1 ,  0
       0    0.05       0     120    0.06       0  271.43    0.05       0
   407.3   0.045       0   444.1    0.07       0  551.43    0.05       0
  701.43    0.06       0  841.43    0.08       0  974.68     0.1       0
Bank Sta=407.3,444.1
XS Rating Curve= 0 ,0
Exp/Cntr(USF)=0,0
Exp/Cntr=0.3,0.1

Type RM Length L Ch R = 1 ,5792    ,228.4,231.4,236.1
XS GIS Cut Line= 2
1597689.27462591439574.4295902961598139.84434867440078.871779901
#Sta/Elev= 30
       0  685.04    24.3  675.96    40.3  667.43      46  662.77    54.5  652.78
    65.8  643.13    76.3  636.68    82.3  635.24     114  632.08   214.4  634.24
     250  631.77   262.5  629.69   286.3629.8896   303.8   628.8   333.2629.8529
   335.4  630.81   340.6  636.24   343.5  637.09   371.8  639.93   421.2  641.85
   490.6  642.66   541.8  638.09   589.9  638.18   592.8  639.33   595.6  642.41
   609.7  660.19   623.9  673.14   632.4  679.46   646.4  687.34   676.4  696.61
#Mann= 9, -1 ,  0
       0    0.06       0      10     0.1       0   286.3   0.045       0
   333.2     0.1       0     410    0.05       0     420     0.1       0
     540    0.05       0     570    0.06       0     670     0.1       0
Bank Sta=286.3,333.2
XS Rating Curve= 0 ,0
Exp/Cntr(USF)=0,0
Exp/Cntr=0.3,0.1

Type RM Length L Ch R = 1 ,5561    ,67.8,65.3,62.8
XS GIS Cut Line= 5
1597692.71504931439629.645565609  1597649.900396439850.309980525
1597728.00964555439971.6375732821597736.75872478440166.330938898
1598048.77408062440206.386964308
#Sta/Elev= 30
       0  665.69       7  663.26    19.2  666.28    23.3  665.61    92.6  648.59
     113  646.79   141.5  640.65   153.7   640.3   186.3  635.85   210.7  635.36
   224.8   636.6   236.3  632.93     256  631.76     275  628.18   298.8  627.78
   317.5  628.19   327.3  628.39   354.5  633.34     394  632.84   465.8  636.17
   530.1  635.44     564   632.1   579.4  635.79   619.8   638.6   676.2  638.93
   781.1  635.68   789.2  638.69   801.2  649.59   821.4  663.32   878.5   670.8
#Mann= 10, -1 ,  0
       0     0.1       0     130    0.06       0     150     0.1       0
  254.78    0.08       0  264.78    0.07       0     275   0.045       0
   317.5    0.07       0  379.08    0.06       0  603.97    0.05       0
  703.97    0.06       0
#XS Ineff= 2 , 0
                          487.08          644.47
Permanent Ineff=
       F       F
Bank Sta=275,317.5
XS Rating Curve= 0 ,0
Exp/Cntr(USF)=0,0
Exp/Cntr=0.3,0.1

Type RM Length L Ch R = 1 ,5496    ,292.2,272.4,252.7
XS GIS Cut Line= 6
1597650.78326547439643.7251752871597615.02361332  439854.0042326
1597617.22311211439926.3110182121597671.29874641439990.822301242
1597685.10753412440202.1705405811598035.17121116440232.062195311
#Sta/Elev= 30
       0  678.76    41.4  672.76    53.6  669.37    73.9  666.13    98.2  663.69
   135.2  656.13   187.5  648.46   214.8  646.77   243.8     638   267.3  633.53
   286.4  631.75   294.9  628.29   326.2  627.59   346.1  628.25   365.9  629.95
   447.7  631.82   616.7  630.69   628.8  632.72   640.8  637.12   660.9  638.45
     677  637.74   737.2   630.9   801.4  636.77   833.5  635.89   837.5  636.51
   841.6  639.29   853.6  655.36   857.6  659.18   860.3  660.23     933  669.12
#Mann= 8, -1 ,  0
       0    0.06       0     140     0.1       0   243.3    0.08       0
   294.9   0.045       0   346.1    0.08       0  369.82    0.06       0
  671.61    0.05       0  771.61    0.06       0
#XS Ineff= 2 , 0
                          660.52          650.65
Permanent Ineff=
       F       F
Bank Sta=294.9,346.1
XS Rating Curve= 0 ,0
Exp/Cntr(USF)=0,0
Exp/Cntr=0.3,0.1

Type RM Length L Ch R = 1 ,5223    ,90.7,87.8,82.1
XS GIS Cut Line= 3
1597329.27974292440185.4243478251597413.14550979440194.100116812
1598023.34126185440249.046653727
#Sta/Elev= 30
       0  728.83    34.6  711.87    47.1  700.68    67.2  689.06    99.3  680.08
   111.4  675.53   143.5  668.23   175.7  654.82   207.8  646.22   218.2  638.09
   235.9   627.9     260  626.26   292.1  627.96   308.2  631.16   388.5  630.69
   404.6  632.53   420.6  637.93   432.7  638.76     501   638.5   537.1  636.11
   553.2  633.38   573.3  637.39   605.4  635.69   609.4  637.08   613.4   640.5
   621.4   652.6   625.5  655.38   645.5   660.6   669.6  664.54     697  665.97
#Mann= 6, -1 ,  0
       0    0.08       0   235.9   0.045       0   292.1    0.05       0
  344.31    0.06       0  444.31    0.05       0  544.31    0.06       0
Bank Sta=235.9,292.1
XS Rating Curve= 0 ,0
Exp/Cntr(USF)=0,0
Exp/Cntr=0.3,0.1

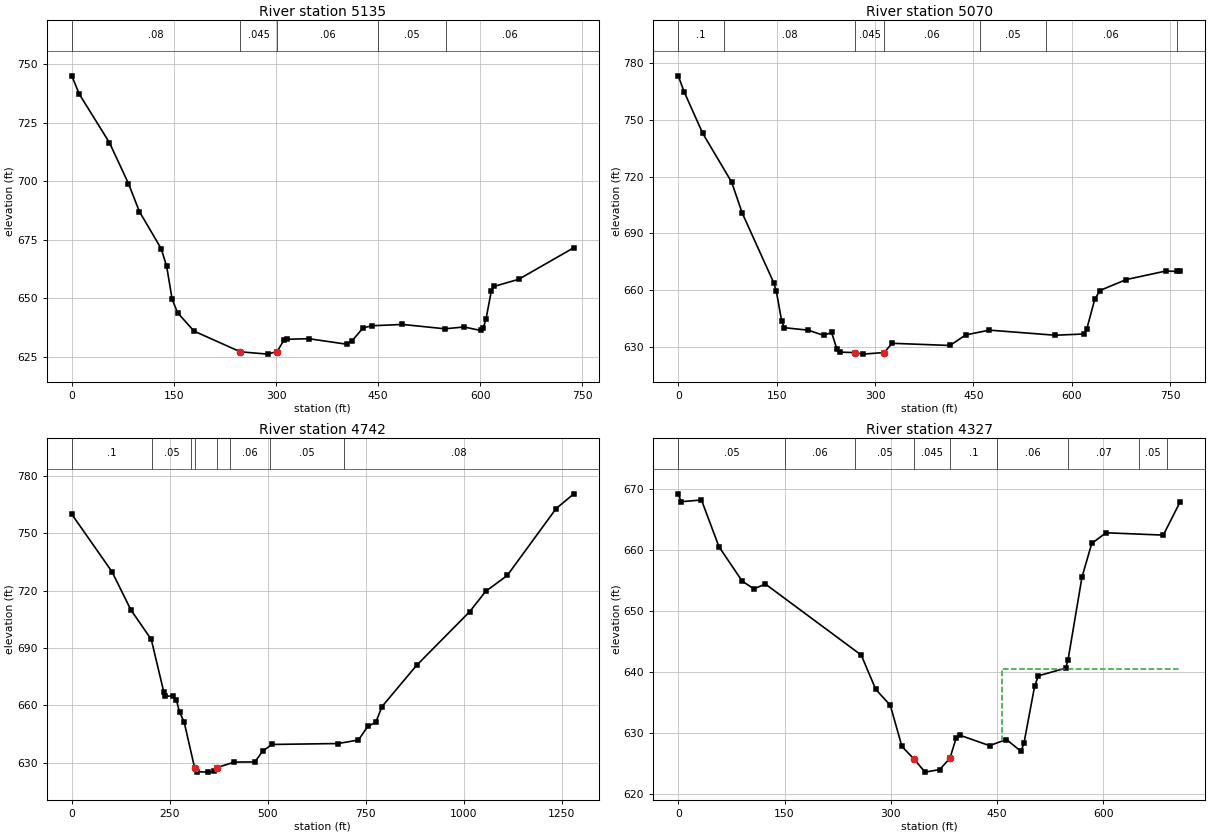
Type RM Length L Ch R = 1 ,5135    ,65.7,65.4,65
XS GIS Cut Line= 2
1597321.01774741 440314.275088911598057.01214977440266.558359484
#Sta/Elev= 30
       0  745.07    11.1  737.22    55.2  716.58    83.3  699.06    99.3   687.1
   131.4   671.2   139.4  663.64   147.4  649.68   155.4  643.87   179.5  636.02
   247.6  627.17   287.7  626.18   301.5  627.27   311.7  632.13   315.8  632.51
   347.8  632.78   403.9  630.41     412  631.96     428  637.42   441.2   638.3
   485.8  638.86   548.2     637   576.3  637.78   600.4   636.3   604.4  637.47
   608.4  641.05   616.4  653.34   620.4  655.11   656.5  658.15   737.5  671.64
#Mann= 5, -1 ,  0
       0    0.08       0   247.6   0.045       0   301.5    0.06       0
     450    0.05       0     550    0.06       0
Bank Sta=247.6,301.5
XS Rating Curve= 0 ,0
Exp/Cntr(USF)=0,0
Exp/Cntr=0.3,0.1

Type RM Length L Ch R = 1 ,5070    ,326.7,328.1,327.9
XS GIS Cut Line= 2
1597310.89601693440382.2352793041598074.36368774440327.288742389
#Sta/Elev= 30
       0  773.31     9.2  764.69    37.3   742.9    81.4   717.1    97.5  700.74
   145.6  663.87   149.6  659.34   157.6  643.76   161.6  640.11   198.3  638.78
   221.8  636.03   233.8   637.6   241.8  628.84   245.9  627.19   269.9  626.92
   281.9  626.12     314  626.97   326.1  631.85   414.3  630.69   438.3  636.28
   474.4  638.81   574.7  636.11   618.8  636.78   622.8  639.38   634.9  655.07
   642.9  659.77     683  665.56   743.1  670.06     760  669.85   765.4  670.29
#Mann= 7, -1 ,  0
       0     0.1       0      70    0.08       0   269.9   0.045       0
     314    0.06       0     460    0.05       0     560    0.06       0
     760     0.1       0
Bank Sta=269.9,314
XS Rating Curve= 0 ,0
Exp/Cntr(USF)=0,0
Exp/Cntr=0.3,0.1

Type RM Length L Ch R = 1 ,4742    ,407.7,414.7,417.3
XS GIS Cut Line= 4
1597320.44986494440598.3829138391597397.70804785440695.795405339
1598166.93082555 440665.563942461598553.22174012440672.282045322
#Sta/Elev= 30
       0  759.86   102.5  729.86   150.8  709.89   202.8  694.43   234.8   666.9
   238.8  664.76   258.8  664.92   266.8  662.78   274.9  656.53   286.9  651.09
   313.1 627.533   318.9  625.32   346.9  625.13   362.9  625.53   369.2 627.464
     415  630.38     467  630.45     487  636.15     511  639.59   679.2  640.07
   731.2  641.91   755.2  649.13   775.2  651.08   791.3   659.4   879.3  680.89
  1014.5  708.88  1055.5  719.55  1110.6  727.86  1235.4  762.85  1280.5  770.53
#Mann= 8, -1 ,  0
       0     0.1       0  204.33    0.05       0  304.33     0.1       0
   313.1   0.045       0   369.2     0.1       0  404.33    0.06       0
  504.33    0.05       0  694.33    0.08       0
Bank Sta=313.1,369.2
XS Rating Curve= 0 ,0
Exp/Cntr(USF)=0,0
Exp/Cntr=0.3,0.1

Type RM Length L Ch R = 1 ,4327    ,66.4,64.8,63.9
XS GIS Cut Line= 2
1597332.09152861441004.3867051561598023.58501991441158.286171208
#Sta/Elev= 30
       0  669.22     4.1  667.93    32.8  668.21    57.4  660.57    90.2  654.93
   106.6  653.66     123  654.44   258.2  642.81   278.7  637.19   299.2  634.59
   315.6  627.85     332  625.86   348.3  623.64   368.9  624.06   383.4625.9244
   392.3   629.3   397.5  629.68   439.2  627.98   463.1  628.98   483.6  627.04
   487.7  628.33   502.9  637.75   508.2  639.42   546.5  640.66   549.9  641.95
   569.6  655.54   583.4  661.09   603.5  662.84   684.4  662.46   708.4  667.96
#Mann= 9, -1 ,  0
       0    0.05       0     150    0.06       0     250    0.05       0
     332   0.045       0   383.4     0.1       0     450    0.06       0
     550    0.07       0     650    0.05       0     690    0.07       0
#XS Ineff= 2 , 0
                          456.58          640.46
Permanent Ineff=
       F       F
Bank Sta=332,383.4
XS Rating Curve= 0 ,0
Exp/Cntr(USF)=0,0
Exp/Cntr=0.3,0.1