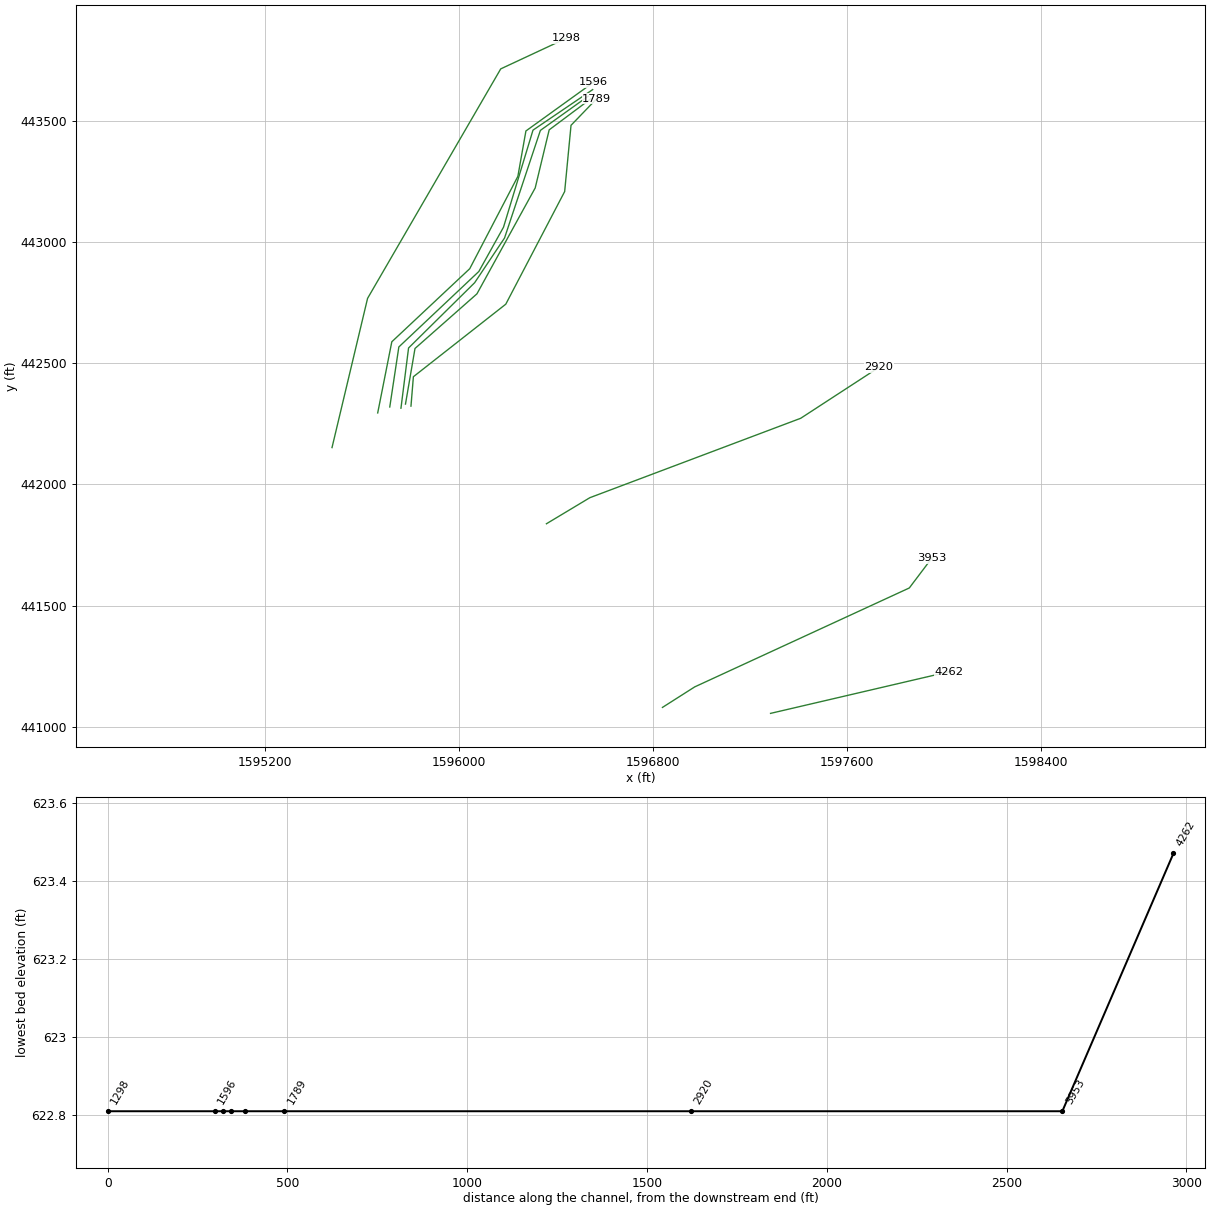
HEC-RAS study PROCTRCK.prj: PROCTRCK

--- PROCTRCK.g01 (geometry) --- (continued)

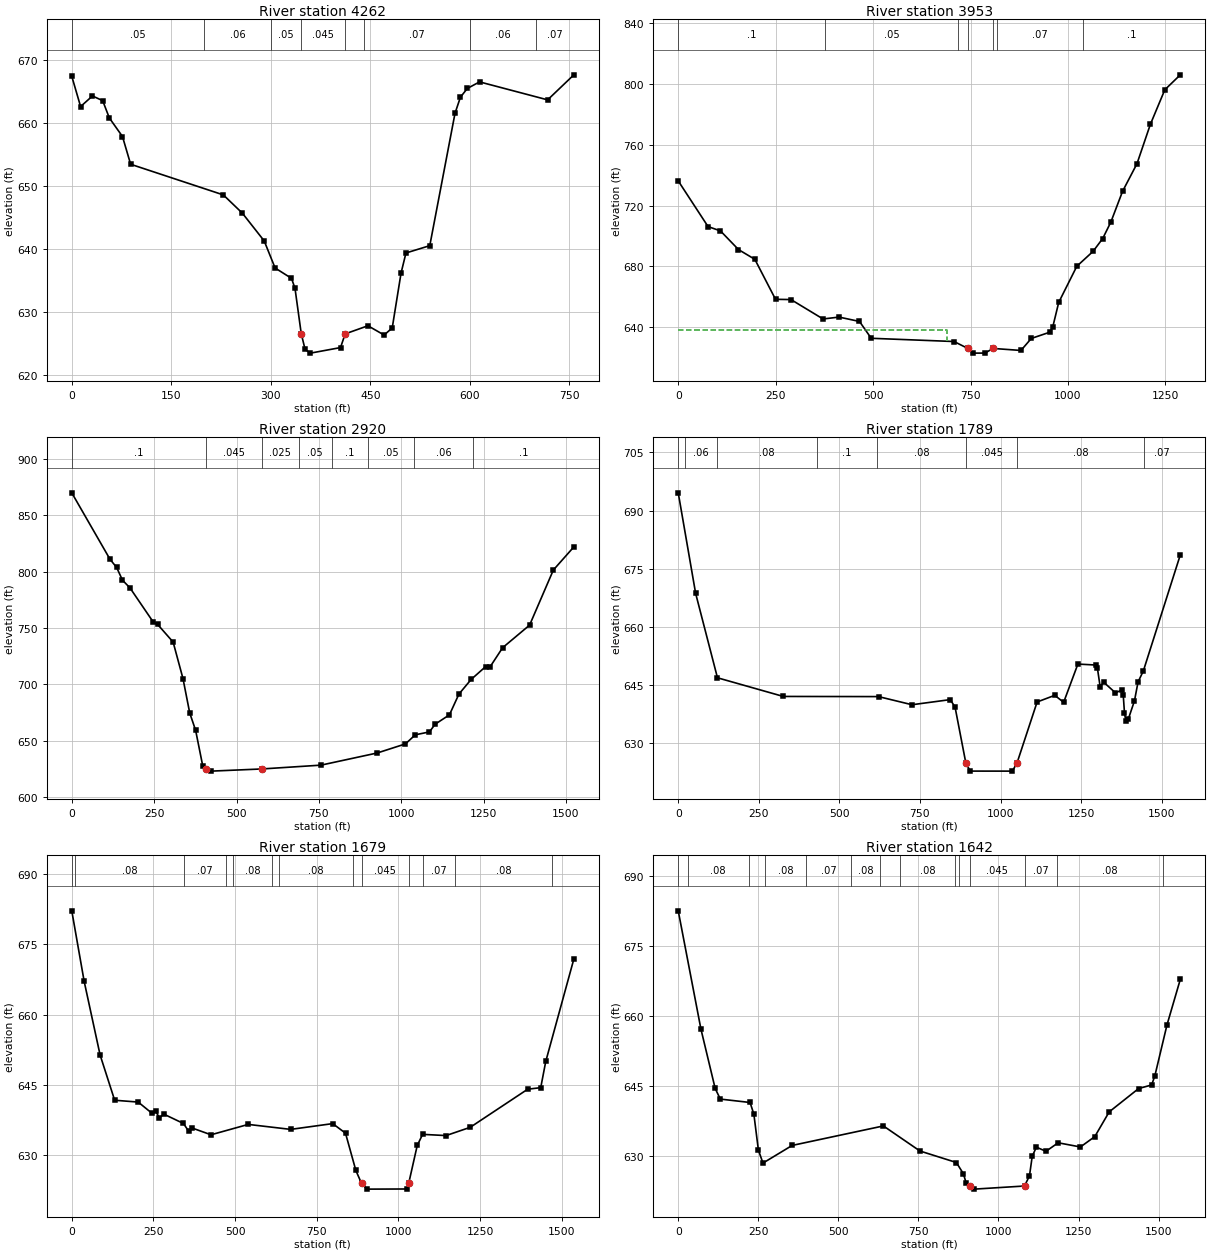
Type RM Length L Ch R = 1 ,4262    ,301.1,309,315.2
XS GIS Cut Line= 2
1597285.71086761441054.9837898851598022.53091398441226.803056779
#Sta/Elev= 30
       0  667.37    13.3  662.57    31.2  664.25    46.6   663.5    56.6  660.76
    76.4  657.82    88.7  653.42   228.4  648.56   257.1  645.66     290  641.26
   306.4  636.97   331.1  635.33   336.4  633.74   345.8 626.554   351.6  624.06
   359.7  623.47     405  624.35     412  626.52   446.3  627.81   470.7  626.34
   482.9  627.46   496.2  636.16   503.6  639.35   539.5  640.51   577.5  661.49
   585.7  664.06   596.1  665.44   614.5  666.48   717.1  663.63   756.6   667.6
#Mann= 8, -1 ,  0
       0    0.05       0     200    0.06       0     300    0.05       0
   345.8   0.045       0     412     0.1       0     440    0.07       0
     600    0.06       0     700    0.07       0
Bank Sta=345.8,412
XS Rating Curve= 0 ,0
Exp/Cntr(USF)=0,0
Exp/Cntr=0.3,0.1

Type RM Length L Ch R = 1 ,3953    ,1040.9,1033.5,968.9
XS GIS Cut Line= 4
1596839.55626623441079.600898311 1596972.5747029441164.248994372
1597858.35656525 441572.373743241597952.07410018441696.322741044
#Sta/Elev= 30
       0  736.28    76.5  706.19   108.3  703.35   154.6  691.04   196.6  684.61
   249.6  658.27   289.3   658.1   371.6  645.31   412.6  646.56   465.1  643.68
   495.2  632.59   707.7  630.46   742.9  625.93   756.1  622.81     787  622.84
  807.92   625.9   879.4  624.57   905.9  632.48   954.3  636.68   961.3  640.34
   976.3  656.23  1022.8  680.06  1064.4  689.85  1089.2  698.33  1110.3   709.3
    1140  729.36  1177.2  747.68  1211.4  773.51  1248.5  796.32  1288.3  806.18
#Mann= 7, -1 ,  0
       0     0.1       0  377.67    0.05       0  717.67     0.1       0
   742.9   0.045       0  807.92     0.1       0  817.67    0.07       0
 1037.67     0.1       0
#XS Ineff= 2 , 0
          690.55  638.25
Permanent Ineff=
       F       F
Bank Sta=742.9,807.92
XS Rating Curve= 0 ,0
Exp/Cntr(USF)=0,0
Exp/Cntr=0.3,0.1

Type RM Length L Ch R = 1 ,2920    ,1076.2,1131,1187.8
XS GIS Cut Line= 4
1596360.60944287 441837.346840161596539.79981032441944.861060631
1597410.15302366442272.5234468291597732.69568507442482.432162987
#Sta/Elev= 30
       0  870.12     116   811.1   136.1  803.82   153.9   792.5   176.7  785.62
   247.8  755.08   260.6  753.15   307.6   737.5   337.5  705.07     358  674.49
     376  658.94   397.4  627.59   405.9  624.71     423  622.81   576.9  624.74
   756.4  628.13   927.3  638.95  1012.8  647.02  1042.7   655.1  1085.5  657.64
  1102.6  664.46  1146.2  672.83  1175.1  691.32  1212.3  704.35  1255.8  715.63
  1270.2  715.76  1307.6  732.47  1389.5  752.56  1461.6  801.53  1523.8  822.07
#Mann= 8, -1 ,  0
       0     0.1       0   405.9   0.045       0   576.9   0.025       0
  688.97    0.05       0  788.97     0.1       0  898.97    0.05       0
 1038.97    0.06       0 1218.96     0.1       0
Bank Sta=405.9,576.9
XS Rating Curve= 0 ,0
Exp/Cntr(USF)=0,0
Exp/Cntr=0.3,0.1

Type RM Length L Ch R = 1 ,1789    ,104.2,109.5,112.4
XS GIS Cut Line= 6
1595801.44871799 442322.690272461595811.41295113442443.975659437
1596192.74961722442743.245018674 1596435.8202938443208.021756223
1596462.08598126443481.3339211911596567.90697842 443590.84986186
#Sta/Elev= 30
       0  694.58      54  668.64   121.7  646.88     326  642.07   621.4  642.03
   725.3  639.93     844  641.25   858.9  639.32  892.21  624.96   905.8  622.82
  1036.8  622.81  1051.5     625  1113.5  640.64  1168.3  642.36  1195.8  640.55
    1240  650.42  1295.7  650.17  1300.3  649.53    1309  644.61  1320.3  645.72
  1356.5  643.01  1376.6  643.72  1380.6  642.56  1384.6  637.81  1388.6  635.83
  1396.7  636.28  1415.5  640.93  1426.7  645.81  1443.2  648.67  1557.8  678.58
#Mann= 8, -1 ,  0
       0     0.1       0      20    0.06       0     120    0.08       0
  431.69     0.1       0  616.44    0.08       0  892.21   0.045       0
  1051.5    0.08       0 1445.51    0.07       0
Bank Sta=892.21,1051.5
XS Rating Curve= 0 ,0
Exp/Cntr(USF)=0,0
Exp/Cntr=0.3,0.1

Type RM Length L Ch R = 1 ,1679    ,33.2,37.8,49.6
XS GIS Cut Line= 6
1595778.77388514442331.0962733181595818.06106455  442560.4759583
 1596073.7002423442785.9020261571596314.20897307443222.859645805
1596371.90136264 443462.594260181596545.38929734443591.922038637
#Sta/Elev= 30
       0  682.11      38  667.06    86.7   651.4   131.3  641.75   203.4  641.36
   245.6  638.97   256.9  639.49   268.2  637.93   281.2  638.81   341.9   636.8
   358.1  635.13   367.4  635.86   426.3  634.39   540.3   636.6   670.2  635.54
   798.9  636.77   838.1  634.73   869.8  626.78   887.3  624.01   904.6  622.81
  1027.8  622.84  1031.6  624.05  1057.7  632.11  1074.2  634.48  1145.9  634.22
  1219.9  635.98  1395.9   644.1  1435.8  644.43  1451.2  650.02  1537.2  671.84
#Mann= 13, -1 ,  0
       0     0.1       0      10    0.08       0  342.72    0.07       0
  472.72     0.1       0  492.72    0.08       0  613.55     0.1       0
  633.55    0.08       0  860.96     0.1       0   887.3   0.045       0
  1031.6     0.1       0  1074.2    0.07       0  1174.2    0.08       0
 1470.78    0.07       0
Bank Sta=887.3,1031.6
XS Rating Curve= 0 ,0
Exp/Cntr(USF)=0,0
Exp/Cntr=0.3,0.1

Type RM Length L Ch R = 1 ,1642    ,20.8,22.3,24
XS GIS Cut Line= 6
1595760.11006113442314.1537916651595791.49089908 442562.51326116
1596064.31625609442831.9073454411596187.64665013443016.375883526
1596335.59326943443460.2518025531596532.98837183 443601.55698664
#Sta/Elev= 30
       0  682.62    70.9  657.19   115.3  644.45   131.4  642.16   224.3  641.43
   236.2   638.9   250.3  631.19   264.6  628.41   355.7   632.2   640.6  636.39
   754.8     631   868.5  628.53   890.2  626.13   899.3  624.08     912  623.49
   924.6  622.81  1081.2  623.48  1096.7  625.66  1105.3  629.86  1118.2  631.83
  1148.3  630.94  1186.3  632.77  1255.8  631.87  1300.7   634.1  1345.6  639.41
  1437.4  644.42  1478.1   645.2    1488   647.1  1526.2  658.13  1567.7   667.9
#Mann= 14, -1 ,  0
       0     0.1       0      30    0.08       0     220    0.07       0
  270.33    0.08       0  400.33    0.07       0  540.33    0.08       0
  630.33    0.07       0  693.75    0.08       0  865.65   0.025       0
  875.65     0.1       0     912   0.045       0  1081.2    0.07       0
 1182.73    0.08       0 1514.98    0.07       0
Bank Sta=912,1081.2
XS Rating Curve= 0 ,0
Exp/Cntr(USF)=0,0
Exp/Cntr=0.3,0.1

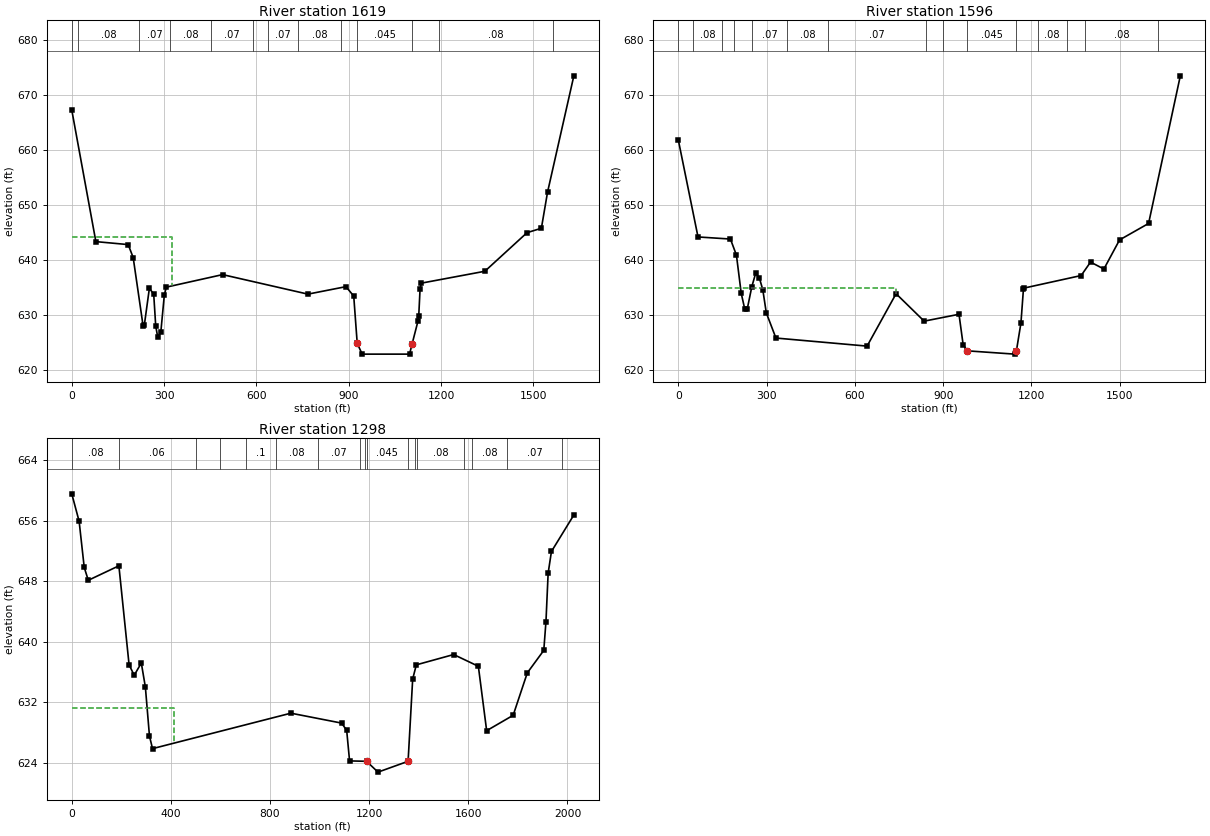
Type RM Length L Ch R = 1 ,1619    ,29.8,23.3,19.8
XS GIS Cut Line= 6
1595713.93670435442319.1583500891595751.36108625442566.782390184
1596081.59890409442878.2106206381596183.36253561443060.865287525
1596305.14132028443461.4230313661596551.35929709 443628.51849493
#Sta/Elev= 30
       0   667.2    78.3  643.27   183.4  642.73   199.6  640.36     232  627.87
     236  628.18   252.2  634.78   266.3  633.71   272.8  627.93   279.3  625.91
   289.3  626.77   300.7  633.51   307.2  634.99   490.1  637.27   767.4  633.72
     891  635.08   916.3  633.37   927.6  624.77   943.7  622.81  1097.7  622.81
  1106.2  624.71  1125.5  628.91  1127.6   629.8  1131.9  634.71  1136.1  635.72
  1342.4  637.88  1479.5   644.9  1526.1   645.7  1546.1  652.26  1631.6  673.42
#Mann= 13, -1 ,  0
       0     0.1       0      20    0.08       0     220    0.07       0
  320.44    0.08       0  453.61    0.07       0  588.07    0.08       0
  638.07    0.07       0  735.04    0.08       0  875.04   0.025       0
   927.6   0.045       0  1106.2    0.07       0 1192.44    0.08       0
    1564    0.07       0
#XS Ineff= 2 , 0
          325.46  644.09
Permanent Ineff=
       F       F
Bank Sta=927.6,1106.2
XS Rating Curve= 0 ,0
Exp/Cntr(USF)=0,0
Exp/Cntr=0.3,0.1

Type RM Length L Ch R = 1 ,1596    ,307.7,297.7,286.6
XS GIS Cut Line= 6
1595664.12039956442294.6447446451595722.33100889442588.128035305
1596044.02053487442889.6844520911596242.64124599443270.600884386
1596275.86059995443457.909344927 1596555.5932863443659.339037288
#Sta/Elev= 30
       0   661.9    67.2  644.16   177.3  643.78   197.7  640.85     214  633.89
   226.2  630.97   234.4  631.01     250  635.11   262.9  637.51   275.2  636.77
   287.3  634.54   299.2  630.33   331.9  625.74   641.6  624.27   740.1  633.82
   835.5  628.82   953.9  630.07   967.9  624.56   981.9  623.41  1142.9  622.81
 1148.98  623.42  1164.3  628.47  1172.8  634.65  1176.3  634.86  1368.9  637.13
  1400.8  639.58  1446.2  638.32  1499.4  643.62    1598  646.62  1705.8  673.52
#Mann= 15, -1 ,  0
       0    0.07       0      50    0.08       0     150    0.05       0
     190    0.08       0     250    0.07       0   369.2    0.08       0
   509.2    0.07       0  840.13    0.08       0  900.13   0.025       0
   981.9   0.045       0 1148.98    0.07       0 1220.84    0.08       0
 1320.84     0.1       0 1381.07    0.08       0 1631.07    0.07       0
#XS Ineff= 2 , 0
          739.81  634.86
Permanent Ineff=
       F       F
Bank Sta=981.9,1148.98
XS Rating Curve= 0 ,0
Exp/Cntr(USF)=0,0
Exp/Cntr=0.3,0.1

Type RM Length L Ch R = 1 ,1298    ,,,
XS GIS Cut Line= 4
 1595475.5211797442151.6090460921595622.29162768442767.247027425
1596171.89962285443714.0964448441596442.07739037443840.130264797
#Sta/Elev= 30
       0  659.54    29.7  655.91    50.3  649.82    66.7  648.13   190.1  650.04
   231.2  636.99   251.8  635.59   280.6  637.21     297  634.03   313.5  627.57
   325.8  625.91   884.1  630.59  1088.8  629.28  1109.2  628.33  1120.9  624.29
  1189.4  624.24  1235.6  622.81 1357.01  624.24  1375.5  635.09  1390.2  636.97
  1540.9  638.33  1640.5  636.78    1674  628.28  1780.9  630.31    1838  635.91
  1904.5  638.88  1913.3  642.68  1922.1  649.07  1935.4  651.93  2025.8  656.75
#Mann= 17, -1 ,  0
       0    0.08       0     190    0.06       0     500    0.05       0
     600    0.08       0  702.89     0.1       0  822.89    0.08       0
  992.89    0.07       0 1162.89   0.025       0 1182.89     0.1       0
  1189.4   0.045       0 1357.01   0.025       0 1382.89     0.1       0
 1392.89    0.08       0 1582.89     0.1       0 1612.89    0.08       0
 1757.69    0.07       0 1977.69    0.08       0
#XS Ineff= 2 , 0
          412.05  631.33
Permanent Ineff=
       F       F
Bank Sta=1189.4,1357.01
XS Rating Curve= 0 ,0
Exp/Cntr(USF)=0,0
Exp/Cntr=0.3,0.1
LCMann Table=0

Chan Stop Cuts=-1
Use User Specified Reach Order=0
Composite Channel Slope=5